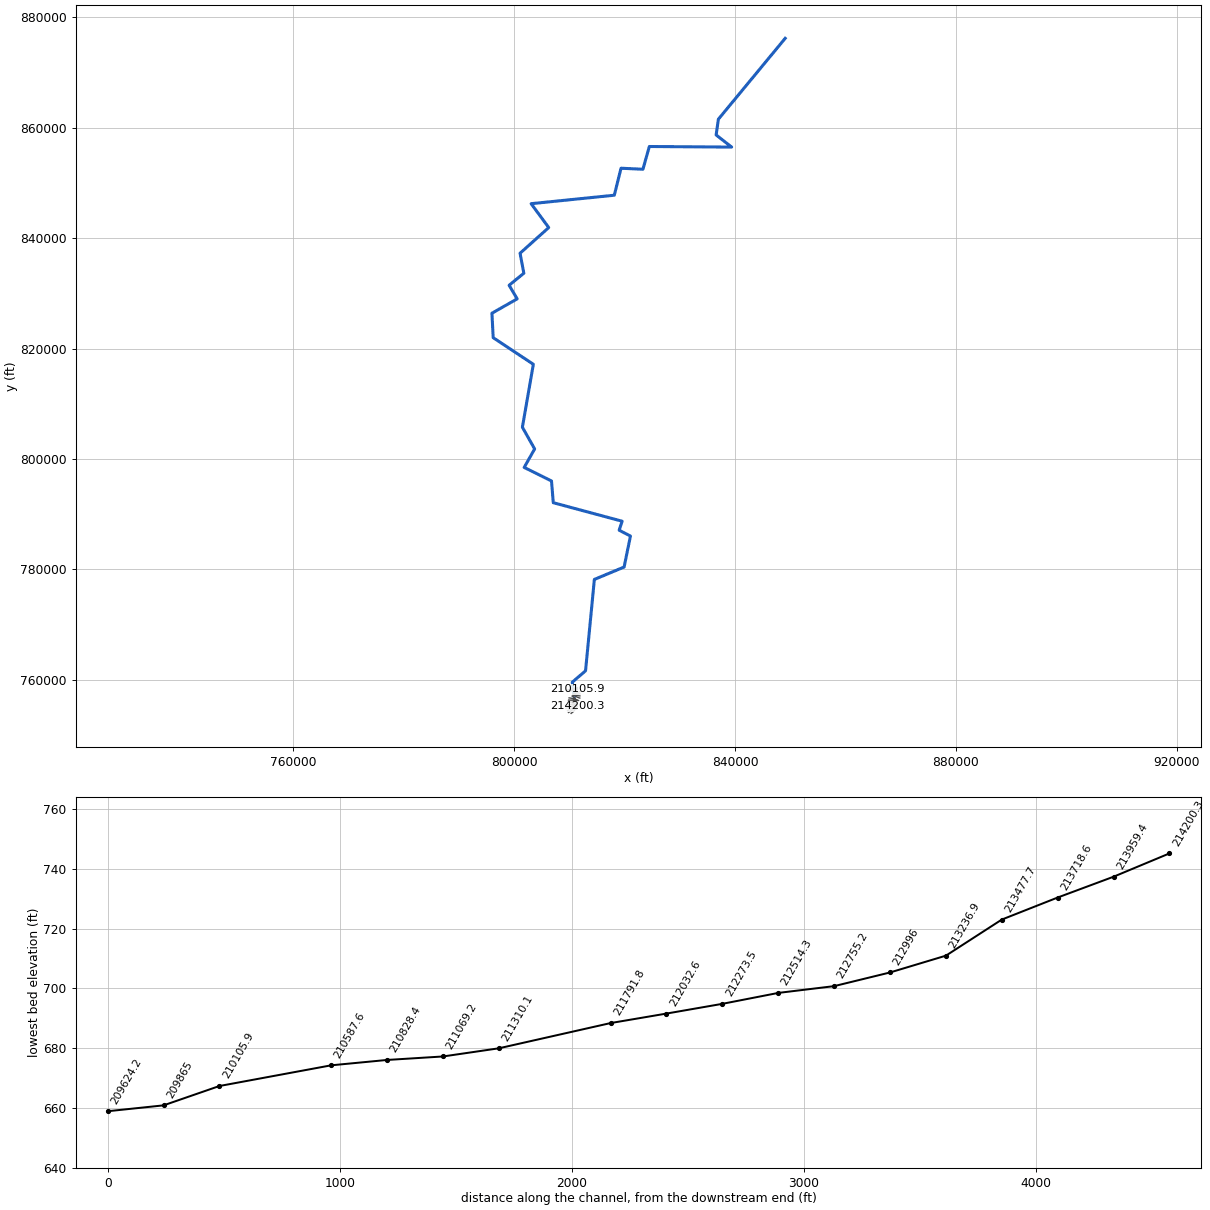
--- 17203_ras.prj (project) ---

Proj Title=17203
Current Plan=p01
Default Exp/Contr=0.3,0.1
English Units
Geom File=g01
Flow File=f01
Plan File=p01
Y Axis Title=Elevation
X Axis Title(PF)=Main Channel Distance
X Axis Title(XS)=Station
BEGIN DESCRIPTION:
RFD model 17203 exported to HEC-RAS
END DESCRIPTION:

--- 17203_ras.p01 (plan) ---

Plan Title=Plan 01
Program Version=4.10
Short Identifier=Plan 01
Geom File=g01
Flow File=f01
Subcritical Flow
Calc Critical at every XS
Secant Critical Depth

--- 17203_ras.f01 (steady flow) ---

Flow Title=Flow 01
Program Version=5.01
Number of Profiles= 6
Profile Names=10yr,25yr,50yr,100yr,100plus,500yr
River Rch & RM=17203,208,214200.3
 1940.63 3006.35 3982.23 4821.75 7039.76 8327.84
River Rch & RM=17203,208,213959.4
 2090.76 3234.21 4280.28 5177.81  7559.6 8834.08
River Rch & RM=17203,208,213718.6
 2096.85 3243.46 4292.36 5192.24 7580.67 8854.47
River Rch & RM=17203,208,213477.7
 2101.98 3251.24 4302.53 5204.39  7598.4 8871.63
River Rch & RM=17203,208,213236.9
 2103.26 3253.18 4305.07 5207.42 7602.84 8875.92
River Rch & RM=17203,208,  212996
 3040.53 4715.59 6253.37 7574.1511058.2612275.75
River Rch & RM=17203,208,212755.2
 3052.95 4734.46 6278.09 7603.6911101.3912315.37
River Rch & RM=17203,208,212514.3
 3058.56 4742.99 6289.26 7617.0511120.8912333.27
River Rch & RM=17203,208,212273.5
 3063.88 4751.06 6299.84 7629.6911139.3512350.22
River Rch & RM=17203,208,212032.6
 3073.58 4765.83 6319.19 7652.8411173.1412381.28
River Rch & RM=17203,208,211791.8
 3077.99 4772.54 6327.98 7663.3511188.4912395.38
River Rch & RM=17203,208,211310.1
  3968.5 6120.78 8089.39 9763.4614254.6615141.83
River Rch & RM=17203,208,211069.2
 3974.91 6130.55 8102.21 9778.8114277.0715161.81
River Rch & RM=17203,208,210828.4
 3978.26 6135.65 8108.91 9786.8314288.7715172.24
River Rch & RM=17203,208,210587.6
 4085.07 6298.09  8321.810041.37 14660.415501.71
River Rch & RM=17203,208,210105.9
 4097.21 6316.61 8346.1310070.5214702.9715539.58
River Rch & RM=17203,208,  209865
 4100.51 6321.65 8352.7510078.4614714.5415549.91
River Rch & RM=17203,208,209624.2
 4111.23 6338.01 8374.2610104.24 14752.215583.43
River Rch & RM=17203,208,209383.3
 5064.24 7834.6610377.4112545.5418316.4918843.23
River Rch & RM=17203,208,209142.5
 5067.39 7839.4710383.7312553.1318327.57 18852.8
River Rch & RM=17203,208,208901.6
 5094.36 7880.72   1043812618.2118422.5918934.87
River Rch & RM=17203,208,208179.1
 5159.63 7980.5610569.3912775.8418652.7219133.47
River Rch & RM=17203,208,207845.3
  5163.8 7986.9410577.7812785.9118667.4319146.16
River Rch & RM=17203,208,207595.4
 5166.67 7991.3310583.5512792.8318677.5419154.88
River Rch & RM=17203,208,206758.9
 9131.5314280.3619058.8923179.8533842.5932334.62
River Rch & RM=17203,208,206595.9
 9135.21   1428619066.3323188.7933855.6332344.94
River Rch & RM=17203,208,  206346
 9139.3514292.35 19074.723198.84 33870.332356.55
River Rch & RM=17203,208,206111.7
 9152.23 14312.119100.74 23230.133915.9532392.66
River Rch & RM=17203,208,205877.3
 9156.8314319.1619110.0423241.2633932.2432405.55
River Rch & RM=17203,208,205596.4
 9187.3914366.0219171.8323315.4534040.5632491.24
River Rch & RM=17203,208,205096.6
 9197.48 14381.519192.2423339.9634076.3532519.57
River Rch & RM=17203,208,203951.5
 9250.0814462.1419298.5723467.6134262.7132666.85
River Rch & RM=17203,208,203018.6
10012.8115624.7220825.3425293.6236928.6934740.63
River Rch & RM=17203,208,202597.8
10017.9815632.6520835.8125306.2136947.0734755.06
River Rch & RM=17203,208,  202348
10022.24 15639.220844.4725316.6236962.2634766.97
River Rch & RM=17203,208,202098.1
10027.1815646.7920854.4825328.6536979.8434780.77
River Rch & RM=17203,208,201848.2
10031.22   1565320862.6825338.5136994.2234792.05
River Rch & RM=17203,208,201540.3
 10057.315693.0420915.5425402.0237086.9534864.73
River Rch & RM=17203,208,201297.1
10061.7815699.9320924.6425412.9637102.9334877.26
River Rch & RM=17203,208,201053.9
10192.1315900.2121189.0925730.8637567.05   35241
River Rch & RM=17203,208,200810.7
 10196.615907.0721198.1525741.7537582.9635253.48
River Rch & RM=17203,208,200567.4
 10199.515911.5321204.0425748.8437593.3135261.59
River Rch & RM=17203,208,200324.2
10319.0116094.7421445.5926038.7838016.6235591.48
River Rch & RM=17203,208,  200081
10351.6716144.9621511.9626118.63 38133.235682.76
River Rch & RM=17203,208,199837.8
10353.8916148.3821516.4826124.0638141.1335688.97
River Rch & RM=17203,208,199594.6
10366.7916168.2121542.6826155.5738187.1435724.96
River Rch & RM=17203,208,199351.4
10397.0916214.7821604.18 26229.538295.0735809.29
River Rch & RM=17203,208,199108.1
10399.7516218.8821609.5926236.0138304.5735816.73
River Rch & RM=17203,208,198864.9
10431.1916267.2521673.5426312.9638416.9335904.69
River Rch & RM=17203,208,198621.7
10432.7416269.6421676.6926316.7638422.4635909.03
River Rch & RM=17203,208,198378.5
11438.2617828.2323746.9228818.8742075.5538783.77
River Rch & RM=17203,208,198135.3
   1144517838.5923760.6328835.3642099.6338802.39
River Rch & RM=17203,208,197892.1
11452.1117849.5623775.1528852.8642125.1838822.21
River Rch & RM=17203,208,197648.9
11455.76 17855.223782.6228861.8742138.3238832.41
River Rch & RM=17203,208,197405.6
11461.5617864.1523794.4728876.16 42159.238848.62
River Rch & RM=17203,208,197162.4
11479.6717892.0823831.4528920.7142224.2338899.04
River Rch & RM=17203,208,196919.2
11484.1817899.0423840.6728931.8342240.4738911.63
River Rch & RM=17203,208,  196676
11486.9717903.3523846.3828938.7142250.5138919.43
River Rch & RM=17203,208,196432.8
11492.1117911.28 23856.928951.3942269.0438933.82
River Rch & RM=17203,208,196189.6
 11493.817913.9123860.38 28955.642275.1838938.63
River Rch & RM=17203,208,195946.3
11499.0817922.0923871.2628968.7442294.3738953.62
River Rch & RM=17203,208,195703.1
11501.1917925.36 23875.628973.9942302.0238959.61
River Rch & RM=17203,208,195459.9
11664.8818178.5924211.53 29379.542894.0739420.26
River Rch & RM=17203,208,195367.2
11665.9218180.2124213.6929382.1242897.8939423.24
River Rch & RM=17203,208,194638.3
11996.3518690.6624890.2630198.0944089.2140345.32
River Rch & RM=17203,208,193909.3
12020.9818729.12 24941.630260.4244180.2240416.87
River Rch & RM=17203,208,193180.4
12078.4218818.4725060.5530404.4944390.5640581.04
River Rch & RM=17203,208,192937.4
12080.2518821.3225064.3730409.1244397.3240586.36
River Rch & RM=17203,208,192694.4
12082.0818824.1825068.1830413.7544404.0740591.66
River Rch & RM=17203,208,192451.4
 12288.319147.2625500.3430939.3745171.4841196.46
River Rch & RM=17203,208,192208.4
12290.3119150.3925504.5430944.4845178.9441202.32
River Rch & RM=17203,208,191965.5
12292.0819153.1825508.2830949.04 45185.6 41207.6
River Rch & RM=17203,208,191722.5
12341.5119230.6325611.8831075.0545369.5841352.38
River Rch & RM=17203,208,191479.5
12345.0619236.2125619.3731084.1745382.8941362.93
River Rch & RM=17203,208,191236.5
12349.7819243.6425629.3331096.3445400.6541376.98
River Rch & RM=17203,208,190993.5
12392.5719310.8525719.3931206.02 45560.8 41503.4
River Rch & RM=17203,208,190496.1
12407.8119334.9525751.83 31245.745618.7241549.59
River Rch & RM=17203,208,189998.8
12496.9919476.1225941.92 31478.345958.3241820.53
River Rch & RM=17203,208,189501.4
12525.06 19520.726002.0831552.05   46066 41906.8
River Rch & RM=17203,208,  189004
12532.79   1953326018.6931572.4446095.7641930.69
River Rch & RM=17203,208,188506.6
 14339.122392.8729870.63 36286.252977.8547361.23
River Rch & RM=17203,208,188009.2
14350.5922411.3429895.7436317.1853023.0947397.32
River Rch & RM=17203,208,187511.8
14358.6522424.3329913.4236339.0353054.9847422.86
River Rch & RM=17203,208,187014.4
14362.8422431.0929922.6336350.4153071.6147436.18
River Rch & RM=17203,208,186517.1
14378.4122456.3429957.1636393.2453134.1347486.68
River Rch & RM=17203,208,186019.7
14387.1922470.7129976.9236417.88 53170.147516.07
River Rch & RM=17203,208,185522.3
14411.3422510.1930031.1636485.4253268.7147596.47
River Rch & RM=17203,208,185024.9
14426.9522535.7130066.2536529.1353332.5447648.56
River Rch & RM=17203,208,184030.1
14490.46 22640.130210.1436708.8653594.9447863.89
River Rch & RM=17203,208,183035.4
14503.7422662.2930241.0436747.7953651.7747911.45
River Rch & RM=17203,208,181543.2
16390.4625728.2834439.3141960.8461262.8254005.61
River Rch & RM=17203,208,179553.7
16504.2325921.5134710.9742305.9261766.6454426.92
River Rch & RM=17203,208,177564.1
16595.2126074.1934924.1742575.1762159.7554750.98
River Rch & RM=17203,208,  176072
 24420.238112.8350843.5761715.5190104.6574553.54
River Rch & RM=17203,208,174579.8
 24553.538336.94 51156.862111.0790682.16 75004.7
River Rch & RM=17203,208,174082.4
24558.9538346.2651169.9662127.8290706.6275024.16
River Rch & RM=17203,208,172590.3
24827.5238805.2751817.5662952.1391910.1275979.96
River Rch & RM=17203,208,172386.1
24829.0438807.8851821.2762956.8791917.03 75985.5
River Rch & RM=17203,208,171936.2
24850.83 38845.451874.4363024.79 92016.276064.81
River Rch & RM=17203,208,171486.3
24857.8838857.5751891.6963046.8792048.4376090.63
River Rch & RM=17203,208,171036.3
24865.4938870.74 51910.463070.82 92083.476118.75
River Rch & RM=17203,208,170586.4
24871.2338880.6851924.52 63088.9 92109.876139.95
River Rch & RM=17203,208,170455.7
24871.9838881.9751926.3663091.2592113.2376142.72
River Rch & RM=17203,208,168965.3
26869.6342189.5656509.1668836.09100500.782525.68
River Rch & RM=17203,208,167971.7
26885.5142217.0456548.2268886.12100573.782583.72
River Rch & RM=17203,208,166978.2
27076.6942546.2957015.0469482.85  10144583272.29
River Rch & RM=17203,208,  164991
27103.8542593.3657082.0169568.71101570.383371.94
River Rch & RM=17203,208,164747.1
 27105.342595.8857085.5969573.31  10157783377.27
River Rch & RM=17203,208,163422.9
27130.1242638.9157146.8369651.83101691.783468.42
River Rch & RM=17203,208,162981.5
27965.7944040.25 59103.772121.59105297.586227.23
River Rch & RM=17203,208,162540.1
28085.48 44245.859394.77 72493.3105840.286652.55
River Rch & RM=17203,208,162098.7
28088.9744251.8559403.3672504.31105856.386665.26
River Rch & RM=17203,208,161657.3
28134.56 44330.559515.0172647.22106064.986829.45
River Rch & RM=17203,208,161215.9
28145.5244349.4659541.9872681.77106115.486869.28
River Rch & RM=17203,208,160999.6
28147.5744353.0259547.0372688.23106124.886876.73
River Rch & RM=17203,208,160013.6
28223.8644484.5559733.7172927.09106473.687150.93
River Rch & RM=17203,208,159520.5
28349.3544698.5160035.4373311.11107034.287586.27
River Rch & RM=17203,208,159027.5
28367.3544729.46 60079.373367.17107116.187650.38
River Rch & RM=17203,208,158041.5
28381.3844753.6260113.5473410.96  10718087700.52
River Rch & RM=17203,208,157548.5
28416.3844813.1360197.3473517.48107335.587820.82
River Rch & RM=17203,208,157055.5
 28421.744822.2460210.2373533.91107359.587839.55
River Rch & RM=17203,208,156562.4
28438.8344851.4360251.3873586.26107435.987898.81
River Rch & RM=17203,208,156069.4
28634.0445183.8560719.8474182.18  10830688572.54
River Rch & RM=17203,208,155576.4
28691.7945280.9760855.7574354.01108556.988763.99
River Rch & RM=17203,208,155083.4
28803.91 45467.261114.3974678.94109031.2 89120.4
River Rch & RM=17203,208,154590.4
28808.8145475.5461126.1474693.91109053.189137.29
River Rch & RM=17203,208,154097.4
28849.8645545.8861225.62 74820.8109238.489281.51
River Rch & RM=17203,208,153604.3
28909.9345649.1661371.9875007.88109511.589494.84
River Rch & RM=17203,208,153111.3
28922.6945670.9161402.6775046.93109568.589538.96
River Rch & RM=17203,208,152618.3
28941.8745703.8661449.3375106.53109655.589606.84
River Rch & RM=17203,208,151139.3
29080.5745936.0861773.4175515.38110252.490059.03
River Rch & RM=17203,208,150153.2
29095.9945962.2161810.1375561.95110320.490111.24
River Rch & RM=17203,208,148674.2
29183.7846110.6362018.4675826.09110706.190406.54
River Rch & RM=17203,208,148181.2
29211.4946158.3362086.12 75912.6110832.490505.18
River Rch & RM=17203,208,147688.1
29218.4346170.3262103.1475934.42110864.390530.15
River Rch & RM=17203,208,146209.1
29310.2946329.4162329.54 76224.8111288.290863.19
River Rch & RM=17203,208,  144730
30440.2348217.2464961.1479541.42116130.594505.34
River Rch & RM=17203,208,  144237
30448.3548231.3664981.28 79567.3116168.394534.98
River Rch & RM=17203,208,  143744
30460.7748253.0765012.3679607.37116226.894581.12
River Rch & RM=17203,208,  142265
30551.2848410.1265236.1579894.71116646.394909.34
River Rch & RM=17203,208,139306.9
40820.7566299.4290819.05112858.9164774.1131874.5
River Rch & RM=17203,208,137827.8
40911.04 66457.291045.34113151.3  165201132196.7
River Rch & RM=17203,208,137334.8
40917.9666469.4591063.01113174.3165234.5132222.3
River Rch & RM=17203,208,136841.8
40921.82 66476.391072.92113187.2165253.3132236.8
River Rch & RM=17203,208,136348.8
40935.6266500.7791108.32113233.3165320.6132288.4
River Rch & RM=17203,208,135855.7
40956.6466538.1791162.53113303.9165423.7132367.8
River Rch & RM=17203,208,135362.7
41230.0267013.1891841.51114178.7  166701133324.8
River Rch & RM=17203,208,134869.7
41235.9567023.7691856.87114198.8166730.2133347.4
River Rch & RM=17203,208,133883.7
41248.9367047.0791890.81114243.2166795.1133397.7
River Rch & RM=17203,208,133751.2
 41251.367051.3391897.02114251.4  166807133406.9
River Rch & RM=17203,208,130211.2
41348.5767226.3692152.25114585.7167295.2133786.4
River Rch & RM=17203,208,129921.7
41352.0467232.6892161.53  114598  167313133800.5
River Rch & RM=17203,208,  125973
41601.9267682.3792817.34115457.3168567.7134775.2
River Rch & RM=17203,208,123998.6
46002.7375680.33104552.7130916.1191137.5152348.6
River Rch & RM=17203,208,122024.2
47969.6479227.81109739.8137731.7201088.2159959.7
River Rch & RM=17203,208,120049.8
48008.9879299.28109844.7137870.1201290.3160114.9
River Rch & RM=17203,208,119062.6
75193.93122501.6168233.3  209345305643.7224699.1
River Rch & RM=17203,208,118075.4
75253.08122610.2168393.6209556.9305953.1224924.2
River Rch & RM=17203,208,117088.2
75571.53123171.3169202.7210606.4307485.4225992.3
River Rch & RM=17203,208,  116101
75579.24123185.4169223.4210633.7307525.2226021.2
River Rch & RM=17203,208,115113.8
75708.43123410.4169545.8211049.6308132.4226438.9
River Rch & RM=17203,208,114126.6
75882.63  123729  170015211668.7309036.3  227093
River Rch & RM=17203,208,113139.4
75978.86123897.7170257.6211982.6309494.6227410.4
River Rch & RM=17203,208,112152.2
76026.66123983.4170382.3212145.7309732.8227579.2
River Rch & RM=17203,208,  111165
76034.89123998.3170404.2212174.6309774.9227609.5
River Rch & RM=17203,208,110177.8
76076.02  124073170513.8212318.8309985.5227760.9
River Rch & RM=17203,208,109190.6
76103.59124123.3170587.7212416.2310127.6227863.4
River Rch & RM=17203,208,108203.4
78879.95128996.1177600.4221497.1323385.8237028.8
River Rch & RM=17203,208,  106229
78917.91129064.2177699.6  221627323575.4237162.7
River Rch & RM=17203,208,105241.8
79048.05129288.1  178018222035.2324171.3237563.7
River Rch & RM=17203,208,103267.4
79096.55129373.7178141.7222195.8324405.8237726.4
River Rch & RM=17203,208,  101293
79393.01129890.1178881.6223150.5325799.8238678.4
River Rch & RM=17203,208,100305.8
79399.33129900.9178897.1223170.3325828.7238697.9
River Rch & RM=17203,208,99318.64
79413.53129925.2178931.5223214.2325892.8238740.5
River Rch & RM=17203,208,97344.25
79508.95130085.8179156.8223499.7326309.6239012.9
River Rch & RM=17203,208,95369.86
79627.42130284.5  179435223851.5326823.2239346.9
River Rch & RM=17203,208,93395.46
79735.73130469.5179697.3224186.6327312.5  239673
River Rch & RM=17203,208,92408.26
79753.98130500.6179741.1224242.5  327394239727.1
River Rch & RM=17203,208,91421.07
80299.34131426.9181048.5225907.3329824.7241333.5
River Rch & RM=17203,208,90433.87
80304.88131436.2181061.7225924.1329849.2241349.6
River Rch & RM=17203,208,89446.67
80315.87131454.9  181088225957.6329898.1241381.8
River Rch & RM=17203,208,88459.48
80349.64131512.4181169.3226061.1330049.3  241482
River Rch & RM=17203,208,88328.94
80351.12131514.9181172.8226065.7330055.9241486.4
River Rch & RM=17203,208,86345.81
80500.55  131768181529.6226519.4330718.3241922.3
River Rch & RM=17203,208,82875.49
80619.74131972.3181819.5226890.3331259.8  242284
River Rch & RM=17203,208,79968.42
80783.77  132255182221.9227406.6332013.6242790.7
River Rch & RM=17203,208,77623.55
80847.46132365.2182379.4227609.3332309.6242990.9
River Rch & RM=17203,208,74229.97
81742.37133886.5184527.8230346.3336305.7245628.3
River Rch & RM=17203,208,71525.23
81818.45134019.3184718.3230592.5336665.1245873.2
River Rch & RM=17203,208,71286.89
81819.61134021.4184721.3230596.3336670.6  245877
River Rch & RM=17203,208,66126.99
86464.18  141655195275.4243787.7  355930257929.6
River Rch & RM=17203,208,61347.96
86840.48142300.3196191.7244960.5357642.3  259062
River Rch & RM=17203,208,54629.96
87144.09142813.4196913.8245877.6358981.3259930.2
River Rch & RM=17203,208,54265.41
87148.32142820.7196924.2  245891359000.9259943.2
River Rch & RM=17203,208,49842.55
87456.05143352.1197681.9246864.4  360422260890.1
River Rch & RM=17203,208,46604.32
91597.45149952.2206622.6257826.2376426.2  270316
River Rch & RM=17203,208,46361.27
91601.35149958.8206631.9257838.1376443.6270327.2
River Rch & RM=17203,208,37265.49
92285.18151111.1208250.4  259890379439.4  272247
River Rch & RM=17203,208,32555.71
92561.87151575.3208900.8260712.5380640.3273011.3
River Rch & RM=17203,208,32384.15
92563.19151577.5208903.9260716.4  380646273014.9
River Rch & RM=17203,208,26134.82
100006.3163140.9224294.7279266.6407729.2288067.1
River Rch & RM=17203,208,   21598
  110101177680.3242588.8300074.4438108.7301914.6
River Rch & RM=17203,208,21457.71
110103.6177684.8  242595300082.3438120.2301921.9
River Rch & RM=17203,208,19200.09
110158.9177777.9242725.8300247.8438361.8302073.2
River Rch & RM=17203,208,14491.43
110274.7177973.8243001.5300597.8438872.7302395.3
River Rch & RM=17203,208, 1033.33
  112956  182588249563.1  309000  451140310271.9
Boundary for River Rch & Prof#=17203,208,1
Up Type= 0
Dn Type= 2
Boundary for River Rch & Prof#=17203,208,2
Up Type= 0
Dn Type= 2
Boundary for River Rch & Prof#=17203,208,2
Up Type= 0
Dn Type= 2
Boundary for River Rch & Prof#=17203,208,2
Up Type= 0
Dn Type= 2
Boundary for River Rch & Prof#=17203,208,2
Up Type= 0
Dn Type= 2
Boundary for River Rch & Prof#=17203,208,2
Up Type= 0
Dn Type= 2

--- 17203_ras.g01 (geometry) ---

Geom Title=17203
Program Version=4.10

River Reach=17203,208
Reach XY= 30
 811104.46755642754854.236246985810520.572581054759582.612147129
812925.154212059761638.714687386814522.814327479778194.980661135
819911.087194921780439.997219058821056.938850941 786049.77110586
819016.336964222787112.266314219819553.137013915788739.137951907
807080.778122816792094.012818139806757.547142956796031.118295595
801811.809727608798483.629751106 803704.58095375801831.450148361
 801485.51188648 805762.88912892803471.188969881817166.968990018
796196.883414298821982.507184498795969.018830987826413.930795601
800539.331330958829013.757184497799083.499188246831479.231937803
801750.268831018833657.854406697801064.226877421837280.577358845
806257.668050557841929.595868188803069.183608293 846253.89236493
 818134.23291111847786.734449084 819353.60268602852677.903193806
823319.526580902852491.657859383824481.640880405 856612.36499936
839386.154769364856506.028193802836579.507345261858707.257981906
836988.585324883861559.413610456849084.690206409 876205.66582063

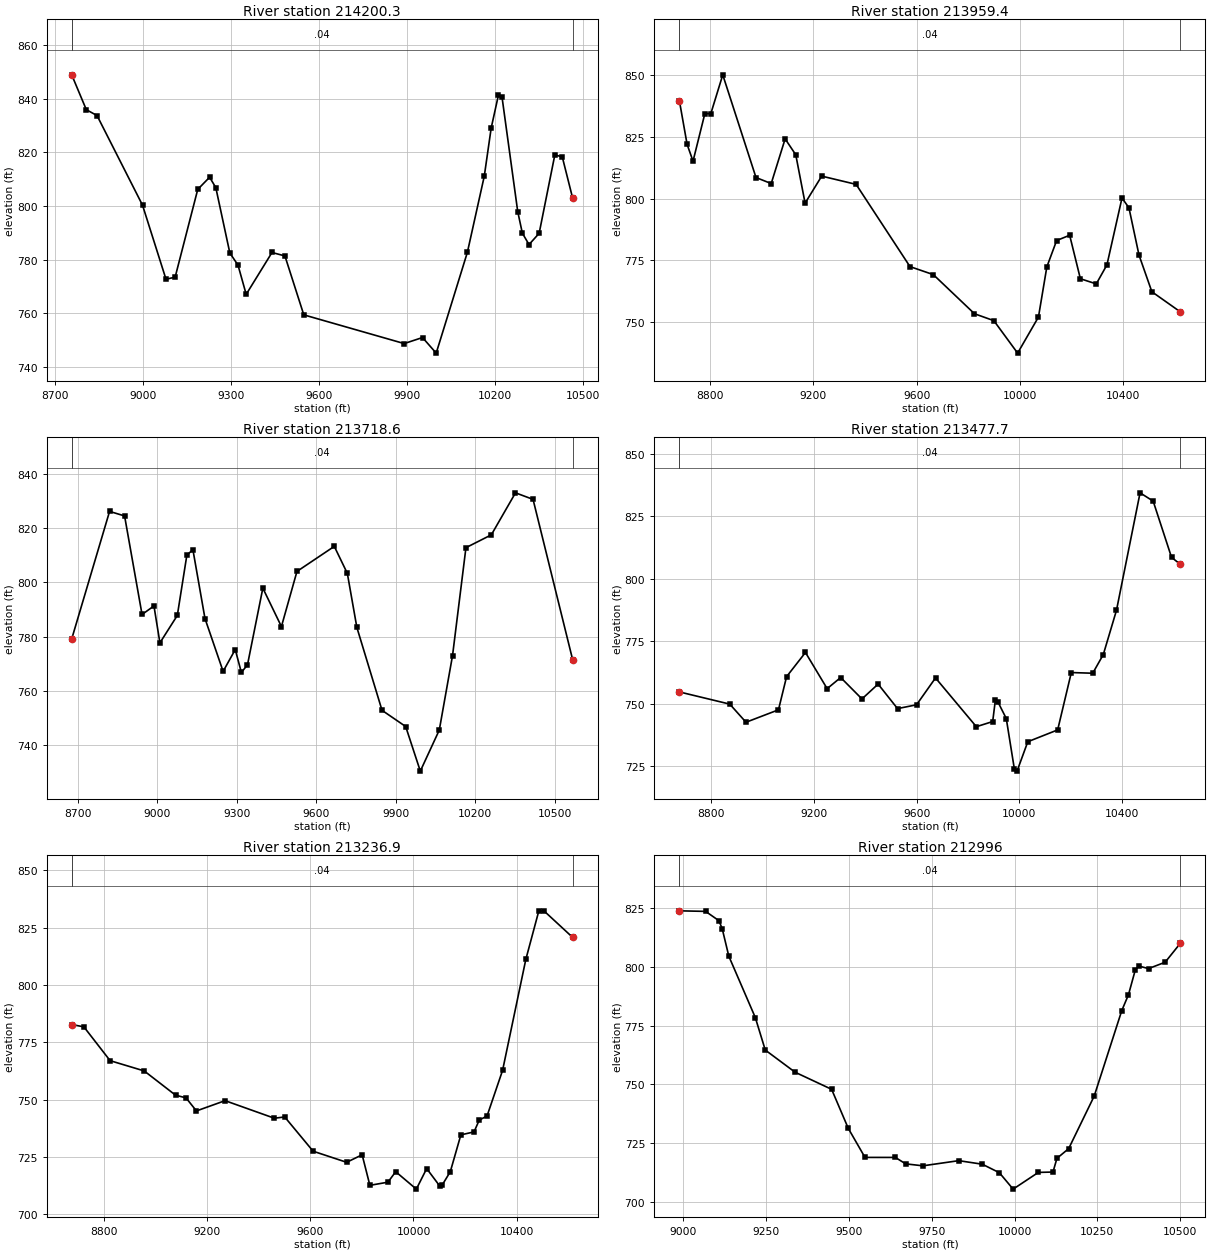
Type RM Length L Ch R = 1 ,214200.3,240.846400,240.846400,240.846400
XS GIS Cut Line= 6
810314.246148897753933.444000545810654.159501122754193.710726076
810871.531999668754413.347965613811005.337162754754608.351842454
811197.862152884755012.255252308811392.870887764755212.328108599
#Sta/Elev= 30
 8757.83848.86868807.545835.88748844.142  833.69 8999.16800.29369079.079772.7227
9110.259 773.4849187.332806.19619227.715810.71329248.845806.85239296.638782.4973
9324.504777.96329352.369767.0815 9440.31782.67869484.352781.39529548.666759.4452
9890.731748.74549953.182750.99329999.829 745.18510106.13782.763510163.65 811.096
10187.23829.063410211.62841.168610223.91840.758710277.68797.907110293.43 789.889
10316.11785.628710350.62 789.81910404.09 819.04810429.45818.295610464.79802.9272
#Mann= 3 , 0 , 0
 8757.83    0.04       0 8757.83    0.04       010464.79    0.04       0
#XS Ineff= 2 , 0
       0                               0
Bank Sta=8757.83,10464.79
Exp/Cntr=0.3,0.1

Type RM Length L Ch R = 1 ,213959.4,240.846400,240.846400,240.846400
XS GIS Cut Line= 6
809829.061138004 754095.17435629810173.826728471754300.457806959
810488.861097932754528.644853644810917.278937333754909.910268935
811152.822339559755183.123630127811328.711587341755306.497404368
#Sta/Elev= 30
8681.163839.50418710.899 821.9298733.827815.14488779.684 834.4368802.699834.3813
8849.045850.11898977.823808.51319036.743806.07829090.706824.17799131.924 817.737
9168.034798.13789232.449809.08949365.724805.74749574.501772.43429665.016769.1827
9824.447753.33219899.437750.54149991.599737.387910072.29752.006710104.81772.3243
10142.69782.9915 10193.2785.140110234.73767.520210296.34765.4324 10337.6 773.126
   10396800.2242 10422.9796.260710461.81777.134310511.72 762.25110622.18754.0946
#Mann= 3 , 0 , 0
8681.163    0.04       08681.163    0.04       010622.18    0.04       0
#XS Ineff= 2 , 0
       0                               0
Bank Sta=8681.163,10622.18
Exp/Cntr=0.3,0.1

Type RM Length L Ch R = 1 ,213718.6,240.846400,240.846400,240.846400
XS GIS Cut Line= 6
809656.321816778754428.574462283810284.613499127754756.027197007
810713.531196862755032.607213882810932.893739775755221.390442416
811085.485385071755310.070318175811274.073624535755386.691833637
#Sta/Elev= 30
8678.094779.13718820.879826.14198877.508824.46418943.375788.15018988.318791.2957
9010.789777.69789076.428787.80249112.395 810.0119135.183812.0479 9180.76786.6643
9249.124767.18979294.905775.22059318.006766.78359341.106769.60989398.994797.8602
9469.085783.69849527.691804.02239668.472 813.2519717.668803.30449753.652783.3739
  9848.5752.83759937.811746.86219992.935730.428910064.53745.568610114.52773.0355
10165.05812.770310260.82817.504310351.96832.982310418.15830.5713 10567.5771.4882
#Mann= 3 , 0 , 0
8678.094    0.04       08678.094    0.04       0 10567.5    0.04       0
#XS Ineff= 2 , 0
       0                               0
Bank Sta=8678.094,10567.5
Exp/Cntr=0.3,0.1

Type RM Length L Ch R = 1 ,213477.7,240.846300,240.846300,240.846300
XS GIS Cut Line= 6
809378.945915985754848.913712745810124.165439815755098.622925945
810827.501113106755342.357171671810892.293750786755362.305240681
810979.923137646755383.833587141811238.689667346 755438.62635144
#Sta/Elev= 30
 8675.43754.71588871.651 749.853 8934.93742.60029061.488 747.5719093.127760.8306
9166.701770.50299251.324756.03459304.056760.48979387.022751.9182 9449.97757.8627
9525.707 748.0579599.734749.5752 9673.76760.31889832.941740.8205 9896.67742.8813
9907.292751.61819917.913750.5531 9949.64744.08839981.143723.91979991.644723.0526
10033.52 734.80810149.99739.539110203.17 762.47810286.71762.2029 10327.9 769.676
10379.26787.358210471.22834.348410522.31831.034910593.86808.566110628.36805.7317
#Mann= 3 , 0 , 0
 8675.43    0.04       0 8675.43    0.04       010628.36    0.04       0
#XS Ineff= 2 , 0
       0                               0
Bank Sta=8675.43,10628.36
Exp/Cntr=0.3,0.1

Type RM Length L Ch R = 1 ,213236.9,240.846400,240.846400,240.846400
XS GIS Cut Line= 6
809288.684790268  755386.2031826809777.370290234755471.843381785
810193.784104039755513.089206637810641.757735947755508.192672473
810963.221469713755457.151092352811215.782565129 755472.24806598
#Sta/Elev= 30
8674.834782.69788721.968781.70838823.736766.96328955.866762.49319077.433751.9221
9117.955750.75719158.477745.06039269.494749.53389460.578741.87979500.707742.4316
9610.854727.50459740.877722.6708  9800.9725.94559830.934712.63119901.014714.0072
9931.048718.584910011.07710.978610051.18719.932510101.91712.327310112.14712.9112
10142.82718.587310183.74 734.63110234.77735.912410254.97 741.06610285.27742.8583
10345.54762.758810435.61 811.09810485.63832.075810505.68832.268210617.15820.6938
#Mann= 3 , 0 , 0
8674.834    0.04       08674.834    0.04       010617.15    0.04       0
#XS Ineff= 2 , 0
       09901.414                       0
Bank Sta=8674.834,10617.15
Exp/Cntr=0.3,0.1

Type RM Length L Ch R = 1 ,  212996,240.846400,240.846400,240.846400
XS GIS Cut Line= 6
809765.962985606 755898.10348056810191.571284799755892.502828582
810464.078997295755847.757554147810639.709609552755769.703332434
810892.700661323755573.041281246811180.953245608755523.368518819
#Sta/Elev= 30
8988.231823.88559067.299823.64759107.307 819.7029117.309816.29999137.313804.5631
9217.327778.42119247.332764.59689337.381755.1506 9447.73747.86389498.035731.2185
 9548.44718.86549640.194718.85599671.028716.12539723.227715.28339831.523717.4809
9902.548715.96979954.083712.35199995.712705.355810071.87 712.47910116.01712.6309
10127.98718.469310163.36722.595910240.51744.9934 10323.7781.386610344.03788.1878
10364.23798.550710374.33800.3951 10404.6799.286910454.68801.991310500.64810.0668
#Mann= 3 , 0 , 0
8988.231    0.04       08988.231    0.04       010500.64    0.04       0
#XS Ineff= 2 , 0
       0                               0
Bank Sta=8988.231,10500.64
Exp/Cntr=0.3,0.1

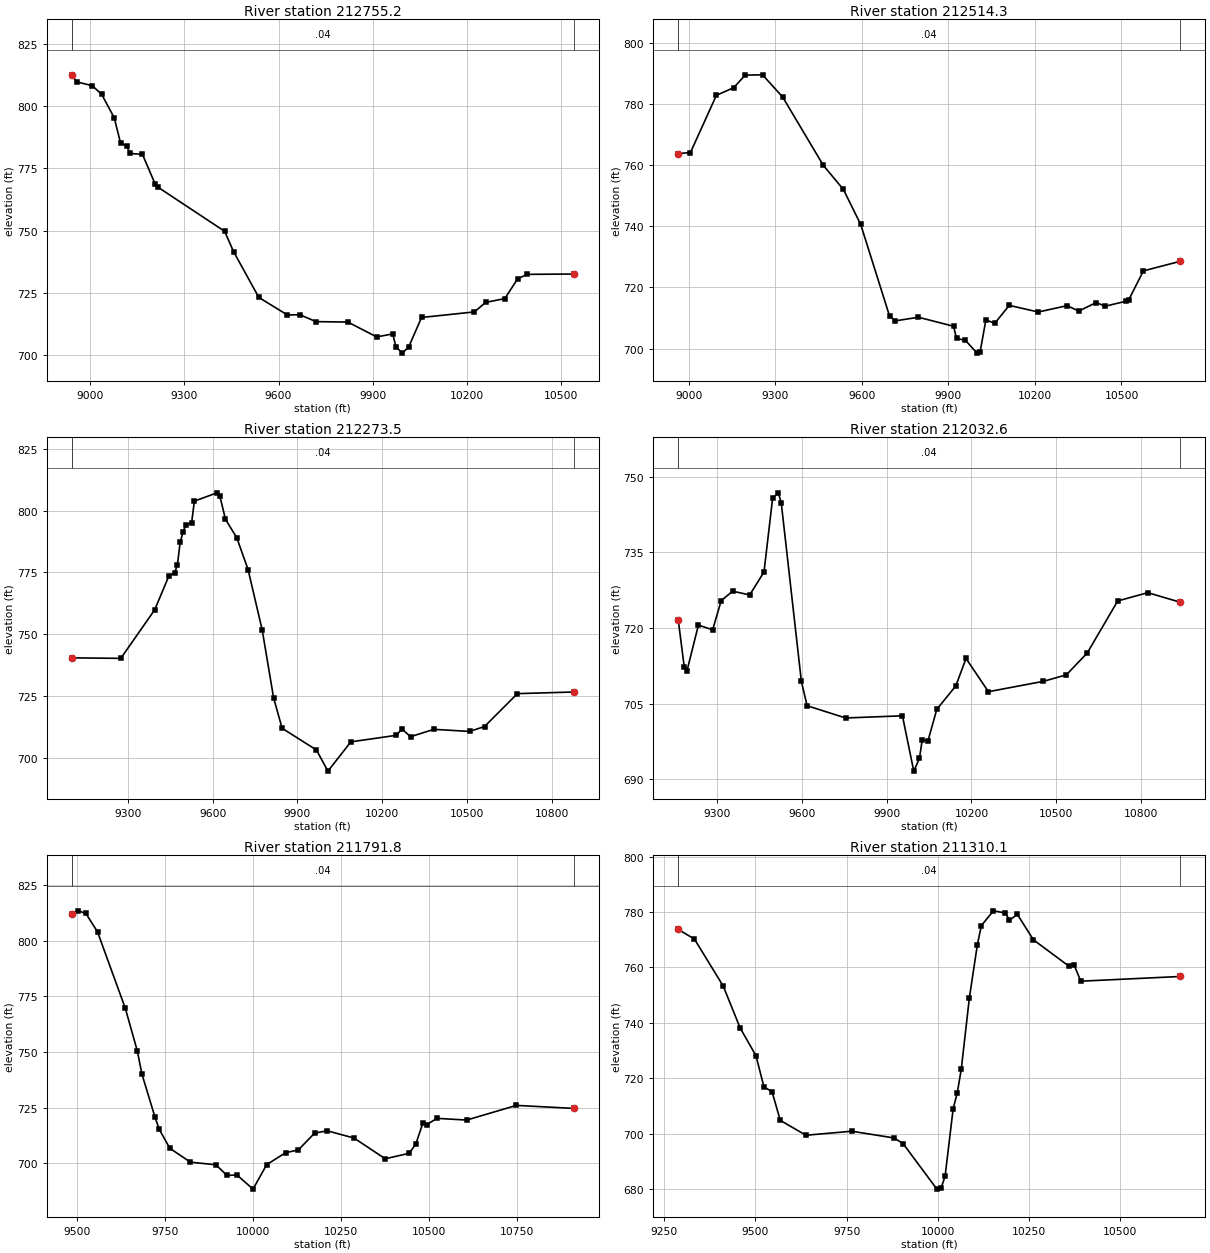
Type RM Length L Ch R = 1 ,212755.2,240.846400,240.846400,240.846400
XS GIS Cut Line= 6
809789.552597299756009.498869098810066.421484392756007.681257818
810411.844423827755981.362378265810639.411991986755944.153068765
811161.677117162755835.830298516811372.831740286755806.604854915
#Sta/Elev= 30
 8940.79812.53288956.244809.70639006.245808.17099036.245804.67339076.245795.2546
9096.245 785.173 9116.25783.86439126.252780.97249166.262780.57569206.273768.7781
9216.275767.3605 9428.04749.70949456.764741.50569537.221723.1324 9627.98716.1315
9668.444716.19489719.246713.43289820.993713.25919912.933707.28979964.011708.5072
9974.227703.35989994.658700.784110015.11703.3216   10056715.098510224.51717.3391
10260.31721.156510321.44722.680410361.96730.579210392.31732.412910541.47732.5516
#Mann= 3 , 0 , 0
 8940.79    0.04       0 8940.79    0.04       010541.47    0.04       0
#XS Ineff= 2 , 0
       0                               0
Bank Sta=8940.79,10541.47
Exp/Cntr=0.3,0.1

Type RM Length L Ch R = 1 ,212514.3,240.846400,240.846400,240.846400
XS GIS Cut Line= 6
809812.810014398756119.325560941810586.435934283756102.450274276
810960.430687609 756161.85650503811092.376138065756168.166538159
811242.757800162756152.380791271811540.005044912756089.983993244
#Sta/Elev= 30
8963.593763.77989005.784764.08679095.793 782.8149155.801785.32459195.825789.4293
9255.869789.52419325.919782.21739466.019759.97729536.069752.02919596.112740.5788
9696.133710.60849716.141709.07269796.321710.24259917.911707.30449928.098703.3127
9958.662702.71559999.416698.514410009.62698.764610030.01709.402710060.49708.2511
10111.12714.132810211.44711.958310311.61714.039210351.87712.258810412.56715.0658
10443.08713.838710514.49715.463410524.73715.8705 10575.9725.411910703.86728.5456
#Mann= 3 , 0 , 0
8963.593    0.04       08963.593    0.04       010703.86    0.04       0
#XS Ineff= 2 , 0
       0                               0
Bank Sta=8963.593,10703.86
Exp/Cntr=0.3,0.1

Type RM Length L Ch R = 1 ,212273.5,240.846300,240.846300,240.846300
XS GIS Cut Line= 6
 809861.72290295756350.303090192810485.437691587756332.696325959
810872.340123444756383.075667298810981.882731021756384.506976943
811116.879622503756359.381822199 811605.79239266756201.501570524
#Sta/Elev= 30
9101.979740.56319275.359740.35449395.465759.98049445.509773.60779465.526774.8035
9475.535778.08349485.544787.38659495.553791.23679505.562794.35379525.579794.8536
9535.587803.79539615.602807.13269625.604805.89189645.607796.43929685.611789.0045
9725.616776.1385  9775.7751.67799815.796724.41039845.969712.14729967.295703.3926
10007.95694.864110089.04 706.67510249.56709.307210269.71711.848610300.15708.7618
10382.76711.723510508.83 710.875 10561.7712.844810678.03726.126510877.66726.7891
#Mann= 3 , 0 , 0
9101.979    0.04       09101.979    0.04       010877.66    0.04       0
#XS Ineff= 2 , 0
       0                               0
Bank Sta=9101.979,10877.66
Exp/Cntr=0.3,0.1

Type RM Length L Ch R = 1 ,212032.6,240.846400,240.846400,240.846400
XS GIS Cut Line= 6
809943.939549067 756738.54836348810226.560357135756705.038621686
810682.046751657 756611.17629285810847.454914082756592.447574368
811252.237547853756372.858061783 811624.86599295756233.833649064
#Sta/Elev= 30
9162.679721.62469183.831712.34019193.875711.56459234.049720.60639284.311719.6414
9314.583725.44039354.946727.32069415.491726.57589466.082731.13549496.578745.7896
9516.908 746.8449527.074 744.8669598.231 709.4249618.585704.5878 9754.66702.1561
9955.773702.58639995.859691.606210015.87694.1229 10025.9697.840210046.03 697.599
10077.33703.871710144.56708.518410180.74713.970810259.98707.369210454.77709.4322
10535.73710.724110609.49715.050510717.32725.384610823.63727.025710938.77725.1278
#Mann= 3 , 0 , 0
9162.679    0.04       09162.679    0.04       010938.77    0.04       0
#XS Ineff= 2 , 0
       0                               0
Bank Sta=9162.679,10938.77
Exp/Cntr=0.3,0.1

Type RM Length L Ch R = 1 ,211791.8,481.692800,481.692800,481.692800
XS GIS Cut Line= 6
810497.874225256757062.926323169810664.308085156756979.971666664
810939.412365985756751.180621418811164.259611513756478.367965757
811365.811671901 756361.45317884811639.409129516756258.486039097
#Sta/Elev= 30
9483.795812.12569502.224813.39079523.747812.24299556.983803.9388 9636.04769.5792
9670.076750.47369683.233740.0713 9720.15720.84939732.456715.2658  9762.6706.7599
9821.201700.51519893.354699.38169924.551694.62989953.674 694.7269998.981688.4301
10037.86699.444710092.01  704.82 10127.5705.988910173.98713.566310209.56714.6237
10286.13711.367210374.67702.0627 10443.5704.537210462.03708.860710481.74718.0509
10493.31717.434310521.73720.204210606.28719.443710747.61 726.02910910.89724.6729
#Mann= 3 , 0 , 0
9483.795    0.04       09483.795    0.04       010910.89    0.04       0
#XS Ineff= 2 , 0
       0                               0
Bank Sta=9483.795,10910.89
Exp/Cntr=0.3,0.1

Type RM Length L Ch R = 1 ,211310.1,240.846300,240.846300,240.846300
XS GIS Cut Line= 6
810651.758450376757285.816745643810909.470384741 757197.76246254
811183.644527292756994.997087031 811341.25501959 756910.71373302
811625.322669239756788.166410527811884.851791863756704.635073386
#Sta/Elev= 30
9288.493 773.6879332.779770.23189411.724753.26859458.301738.09359501.459728.1535
9523.304716.9121 9545.62715.11199568.105704.79799638.451699.42599764.026700.8783
9880.386698.44129905.042696.35529997.382679.986410008.65680.306810019.77684.5665
10042.01709.051810053.13714.639410064.24723.315910086.43749.056810108.37768.2462
10119.35775.097810152.26780.401810185.18779.626810196.15 777.045 10218.1779.0861
10261.83769.9508   10359760.453610373.63760.792210391.75755.012210664.49756.7137
#Mann= 3 , 0 , 0
9288.493    0.04       09288.493    0.04       010664.49    0.04       0
#XS Ineff= 2 , 0
       0                               0
Bank Sta=9288.493,10664.49
Exp/Cntr=0.3,0.1

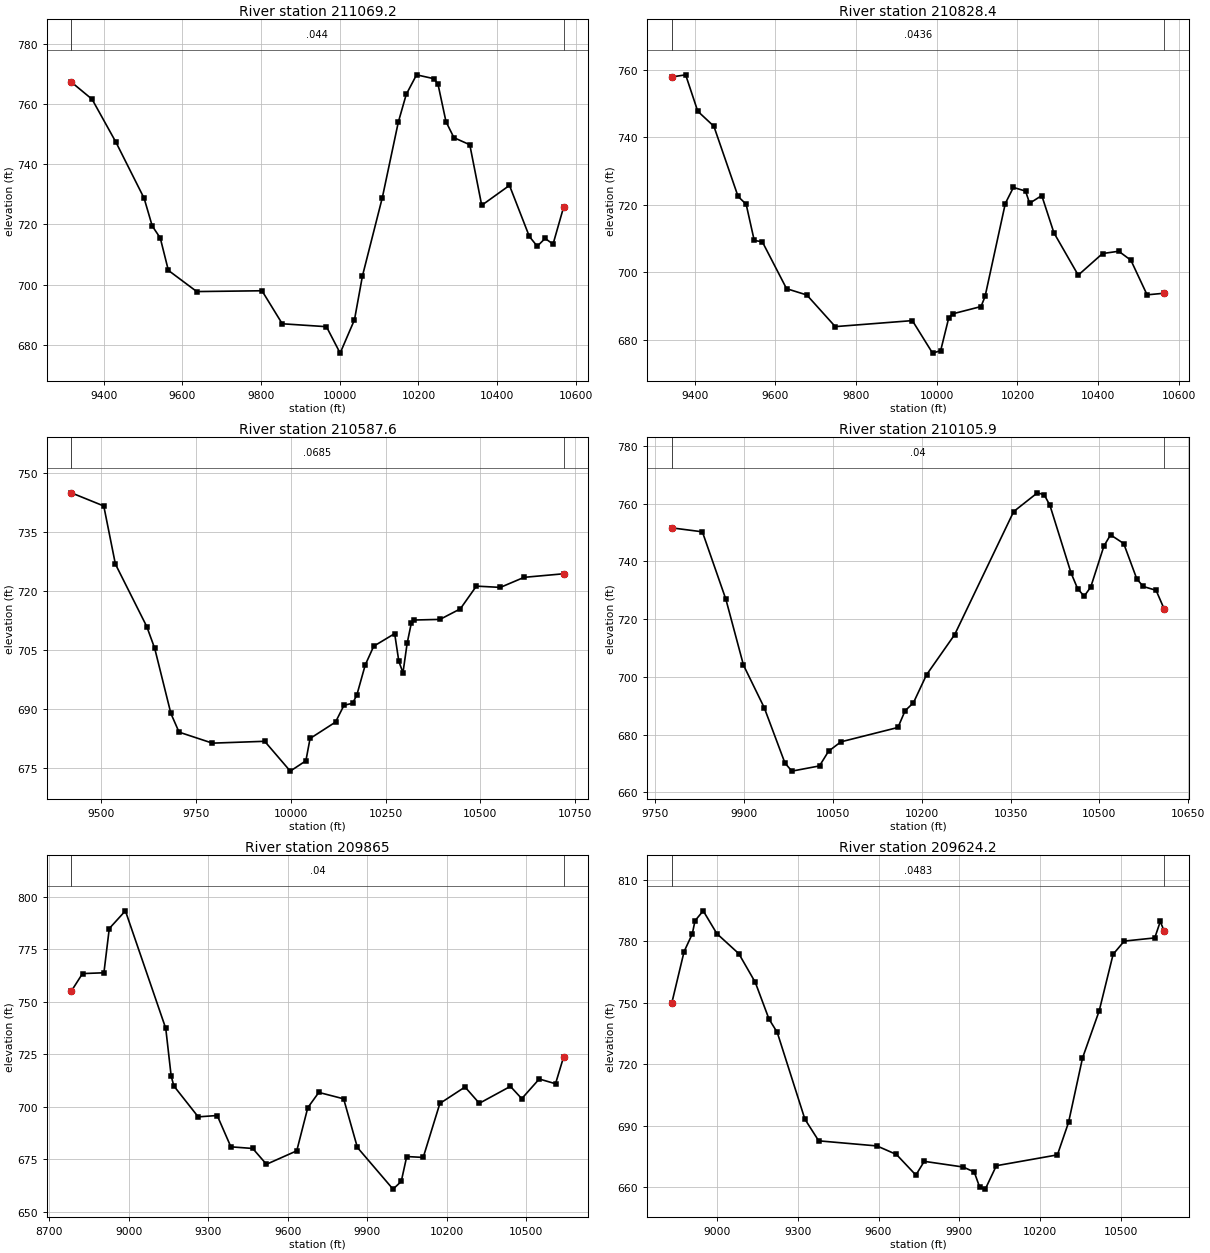
Type RM Length L Ch R = 1 ,211069.2,240.846400,240.846400,240.846400
XS GIS Cut Line= 6
810672.644766345757325.631285455810821.073411466757301.583406879
 811171.50719034757211.113265607811372.008484992757169.920501083
811575.129914748757138.067386303811901.610484175757096.788473495
#Sta/Elev= 30
9317.351767.26519370.232761.55119431.125747.23129502.575728.66859523.114719.4944
9543.652715.46879564.191704.73459636.411697.69519802.242697.96339853.772 687.002
9966.149686.0348   10001677.254510037.44688.334110057.69702.8701 10108.3728.9177
10148.79753.892810169.03763.150910195.27769.664110239.89768.367710249.98766.4528
10270.15754.104710290.33748.793410330.68746.446310360.94726.329610431.56732.9503
   10482716.012710502.12712.739710522.24715.349310542.35713.432810569.12725.6858
#Mann= 3 , 0 , 0
9317.351   0.044       09317.351   0.044       010569.12   0.044       0
#XS Ineff= 2 , 0
       0                               0
Bank Sta=9317.351,10569.12
Exp/Cntr=0.3,0.1

Type RM Length L Ch R = 1 ,210828.4,240.846400,240.846400,240.846400
XS GIS Cut Line= 6
810700.532134975757378.791581899 810873.63447916757379.358163656
810957.362412781757383.353276741811267.701759431757417.743752022
811454.954568044757414.346231215811916.904510889 757454.66869861
#Sta/Elev= 30
9342.943757.90089377.414758.53599407.415747.75219447.415743.29719507.416722.4971
9527.429720.19429547.452709.46669567.475 709.0819627.607695.18139677.817693.3143
9748.356683.94369939.465685.72179989.546 676.089 10009.6676.812110029.64686.5326
10039.66687.737710109.71 689.88710119.74692.904210169.87720.416110189.94725.1802
10220.07724.095110230.11720.484610260.25722.763810290.38711.735610350.64699.1881
10410.91 705.59210451.08 706.26910481.21703.611710521.34693.360310563.36693.8266
#Mann= 3 , 0 , 0
9342.943  0.0436       09342.943  0.0436       010563.36  0.0436       0
#XS Ineff= 2 , 0
       0                               0
Bank Sta=9342.943,10563.36
Exp/Cntr=0.3,0.1

Type RM Length L Ch R = 1 ,210587.6,481.692700,481.692700,481.692700
XS GIS Cut Line= 6
810730.353449689757435.638463068810866.341285751757459.003991177
810970.859937678757490.427576261811578.982671876757782.636923754
811768.223545213 757851.40181181811935.801365399757896.855094157
#Sta/Elev= 30
9421.914744.89879507.525741.56149538.119726.83279620.888710.96249641.768705.4337
9684.367688.93369705.914684.18499793.845681.39259931.579681.8628    9999674.2945
10040.13676.913710051.16682.575110118.26686.737610140.62691.014810162.99 691.489
10174.17693.525710196.53701.2227 10218.9705.9872 10274.1709.180210285.05702.1661
   10296699.248910306.94706.700110317.89711.817410325.38712.6293 10393.5712.7889
10447.13715.461810489.41721.228910552.62720.906710615.09723.458310719.21724.3615
#Mann= 3 , 0 , 0
9421.914  0.0685       09421.914  0.0685       010719.21  0.0685       0
#XS Ineff= 2 , 0
       0                               0
Bank Sta=9421.914,10719.21
Exp/Cntr=0.3,0.1

Type RM Length L Ch R = 1 ,210105.9,240.846400,240.846400,240.846400
XS GIS Cut Line= 6
810739.846848256757850.080294375810956.274170976757977.298244087
811120.148302754758087.535226644811205.932046925758141.399329198
 811293.90561321758190.898705774 811457.35502309758267.841109332
#Sta/Elev= 30
  9777.6751.61259829.349750.24469869.094726.83789898.813704.06039933.842689.3456
9968.872670.14539980.548667.371210027.19669.177510042.48674.2645 10063.3677.5089
10159.72682.491810171.77688.292510185.81691.026310207.92700.713310255.52714.6475
10355.21757.266310395.25763.746510406.72763.083110416.39 759.41610451.91736.0954
10463.05730.609610474.19 727.93910485.33 731.111 10507.6745.318710518.74749.2018
10541.02746.186210563.16733.922510574.01731.318710595.72729.980210609.13723.6224
#Mann= 3 , 0 , 0
  9777.6    0.04       0  9777.6    0.04       010609.13    0.04       0
#XS Ineff= 2 , 0
       0                               0
Bank Sta=9777.6,10609.13
Exp/Cntr=0.3,0.1

Type RM Length L Ch R = 1 ,  209865,240.846400,240.846400,240.846400
XS GIS Cut Line= 6
809663.039878971757914.240388069 809944.79496567757957.808119302
810091.372999403757986.295287418810321.083567164758040.652212858
810983.566262974758224.883918168811453.842171362758394.889247119
#Sta/Elev= 30
8782.727755.0168 8825.09763.3804  8905.9763.7688 8926.17784.8069 8986.98 793.222
9139.371737.30479159.745714.69719169.932709.95549261.884695.25749333.624695.9054
9385.109681.00999467.682680.22969519.548672.71239633.836679.10989675.482 699.614
9717.127706.8829 9810.83703.83569862.793680.6954 9997.25660.899110028.27664.5333
10048.94  676.3910111.21675.973510174.07701.637710269.06709.455510323.05701.7099
10440.35 709.75510483.18703.917810549.28713.267710610.69711.001910641.07723.7026
#Mann= 3 , 0 , 0
8782.727    0.04       08782.727    0.04       010641.07    0.04       0
#XS Ineff= 2 , 0
       09843.088                       0
Bank Sta=8782.727,10641.07
Exp/Cntr=0.3,0.1

Type RM Length L Ch R = 1 ,209624.2,240.846400,240.846400,240.846400
XS GIS Cut Line= 6
809669.731072224758168.841434231809835.683387358758196.415845165
810051.179733159758238.689866554810268.246784913758288.639549191
810959.412540207758460.576155689811448.547011545758586.397527633
#Sta/Elev= 30
8832.052749.69688877.942774.94538908.353783.5787 8918.49789.99478948.902794.8408
8999.587783.70289081.108773.91479142.252759.91469193.205741.97629223.804 735.475
9326.417693.12029377.724682.51789594.109680.02349666.367675.86179738.624665.7913
9769.591672.50449914.106669.72969955.234667.29879975.761659.77089996.288658.9337
10037.37670.369110264.11675.658110305.48691.5358 10357.2722.912610419.27746.0066
10470.98773.632610512.24780.061210625.55781.612810646.13789.650410659.98785.0769
#Mann= 3 , 0 , 0
8832.052  0.0483       08832.052  0.0483       010659.98  0.0483       0
#XS Ineff= 2 , 0
       0 9800.76                       0
Bank Sta=8832.052,10659.98
Exp/Cntr=0.3,0.1