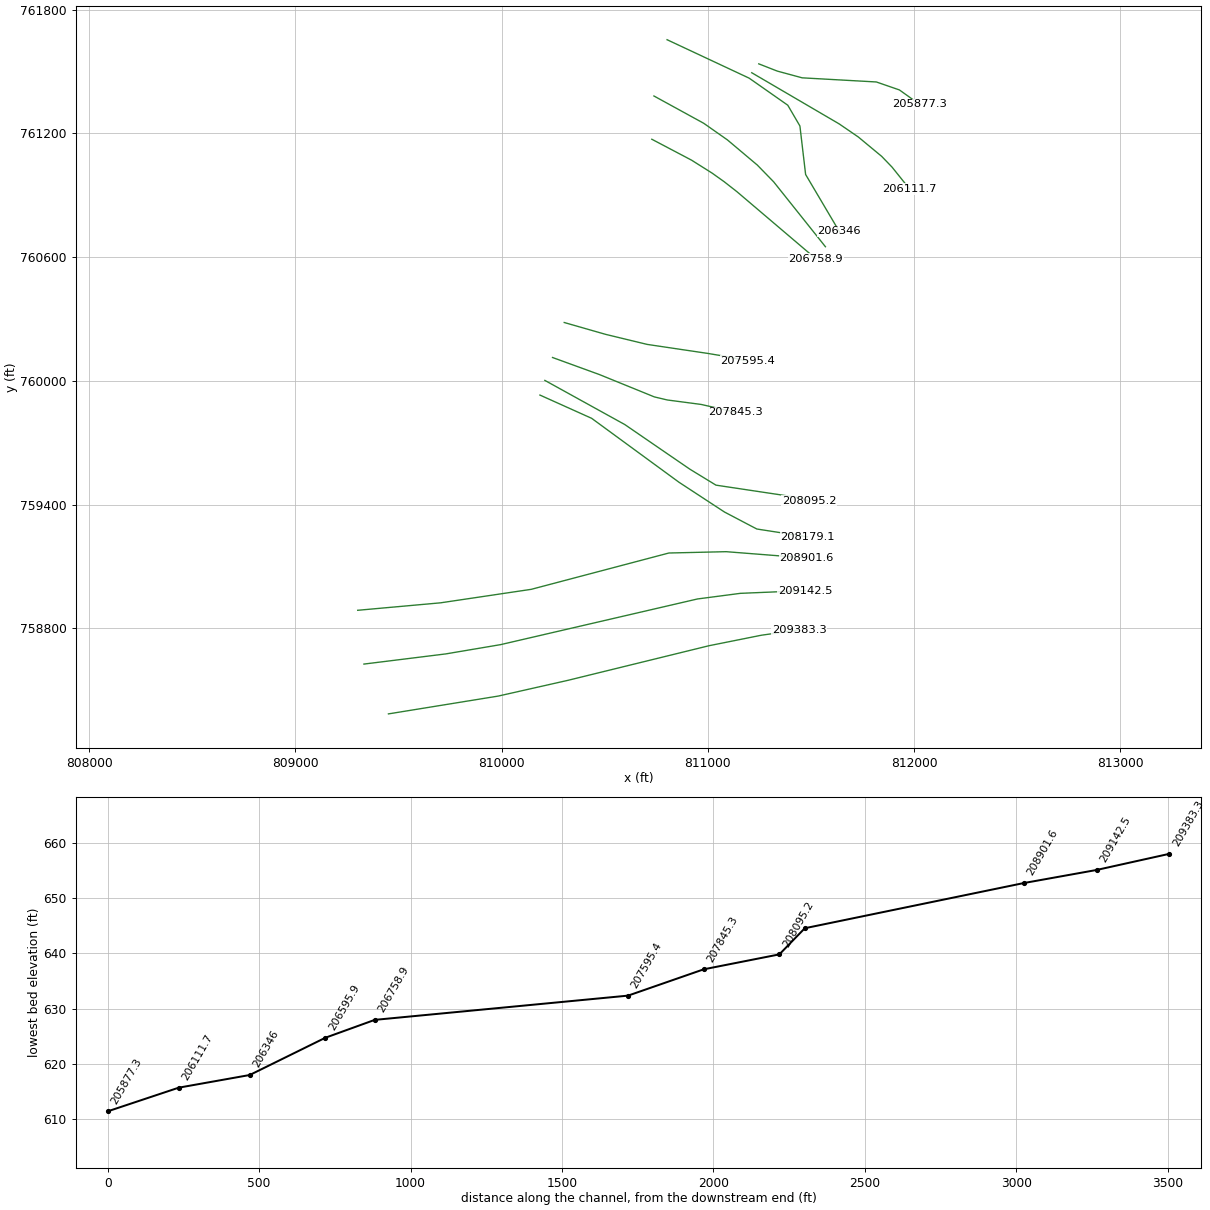
HEC-RAS study 17203_ras.prj: 17203

--- 17203_ras.g01 (geometry) --- (continued)

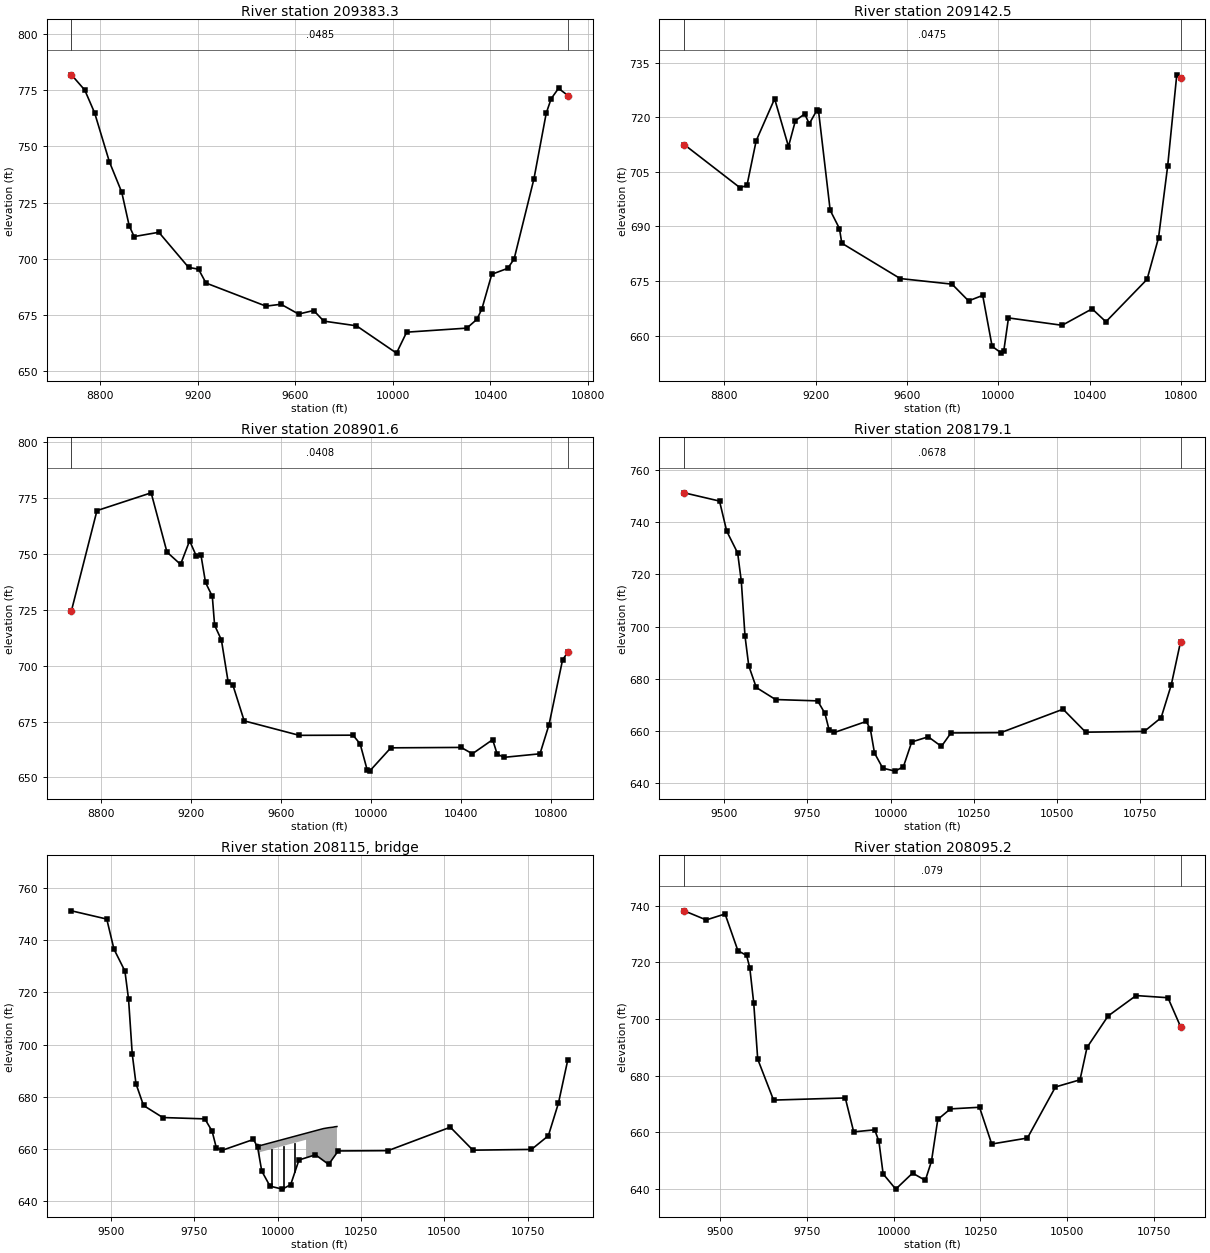
Type RM Length L Ch R = 1 ,209383.3,240.846400,240.846400,240.846400
XS GIS Cut Line= 6
809451.023295757758384.648452968809983.537468569758471.061530147
810321.178184609758547.329375506811006.211477072758715.395240423
811259.799467379758766.176168932811442.861676578758792.017142761
#Sta/Elev= 30
8682.508781.8699 8736.97775.08978777.331764.9638  8837.9743.19348888.559729.6616
8918.955714.81038939.219709.94299040.538711.85039162.501 696.2419203.224695.4462
 9233.81689.28589479.756679.00529541.378679.84539613.478675.47989675.384677.0683
9716.655672.34729850.786670.264310014.84658.112110056.43 667.42910303.09669.2331
10344.02673.101910364.48677.638910405.37693.173310470.87695.8259 10496.9699.9617
10578.02735.512910628.61764.817110648.82771.253310679.05775.858810717.19772.6692
#Mann= 3 , 0 , 0
8682.508  0.0485       08682.508  0.0485       010717.19  0.0485       0
#XS Ineff= 2 , 0
       09790.227                       0
Bank Sta=8682.508,10717.19
Exp/Cntr=0.3,0.1

Type RM Length L Ch R = 1 ,209142.5,240.846300,240.846300,240.846300
XS GIS Cut Line= 6
809332.134650769758626.248453823809728.565944405758675.464197335
809994.146213647 758720.36987652 810949.57599802758941.969571137
811158.091640107758969.284055881811471.780433369758982.321088694
#Sta/Elev= 30
8623.735712.50568868.224700.63888898.507701.30038938.884 713.5719019.639725.0978
9080.384 711.9669110.763719.10159151.267720.91999171.531718.23889206.058722.0995
9212.178 721.6659262.985694.44959303.671 689.419 9313.87685.39849569.799675.6751
9796.844674.13529869.163669.53499931.151671.04429972.393657.042810013.38655.1721
10023.62655.851910044.11664.853310279.12662.824910410.43667.348310470.81663.7971
 10651.2675.463710701.24686.838610741.25706.529110781.25731.687110798.03730.7251
#Mann= 3 , 0 , 0
8623.735  0.0475       08623.735  0.0475       010798.03  0.0475       0
#XS Ineff= 2 , 0
       0                10385.01       0
Bank Sta=8623.735,10798.03
Exp/Cntr=0.3,0.1

Type RM Length L Ch R = 1 ,208901.6,722.539100,722.539100,722.539100
XS GIS Cut Line= 6
809301.959354813758887.075503629809703.577607067758923.234178383
810143.227011777758988.667090019810810.943835653759164.850492602
811088.644442551759171.289937385811478.465511236 759140.75743411
#Sta/Elev= 30
8666.583724.68388779.962769.43919021.021777.40339091.438750.86899151.885745.3583
9192.183755.93659222.452748.96769242.668749.52539262.883737.28449293.207 731.023
9303.315718.13619333.639711.51769363.962692.5182  9384.2691.49249434.989675.2966
9680.069668.8143  9919.3668.88919950.934664.98029982.568 653.1789993.113652.7908
10087.34663.221310400.27663.4027 10450.3660.557210540.43666.872110560.47660.4282
10590.53658.961610751.06660.553110791.21673.568410851.45702.573610875.01706.0996
#Mann= 3 , 0 , 0
8666.583  0.0408       08666.583  0.0408       010875.01  0.0408       0
#XS Ineff= 2 , 0
       0                10371.91       0
Bank Sta=8666.583,10875.01
Exp/Cntr=0.3,0.1

Type RM Length L Ch R = 1 ,208179.1,83.923500,83.923500,83.923500
XS GIS Cut Line= 6
  810185.6740484 759930.80371884810436.455599785759817.984610975
 810859.93510896759508.041928574811080.339178771759363.748616681
811237.317616999759281.295295581811482.785437051  759243.1396759
#Sta/Elev= 30
9380.885751.29449486.748748.13289508.344736.61219541.223728.20079552.183717.3861
9563.243696.37719574.511684.97199597.047676.66549654.873672.03699781.162671.5223
9802.977 666.7969815.386660.5175 9831.83659.41659927.066663.63899939.475660.6918
9951.884651.51579976.702645.725310013.93644.586510038.75646.308310063.56655.7695
 10113.2 657.74310152.73654.063110181.37659.229910330.85659.337410517.84668.3316
10585.62659.526310761.46659.809910812.06665.057910842.42677.607110870.54694.2565
#Mann= 3 , 0 , 0
9380.885  0.0678       09380.885  0.0678       010870.54  0.0678       0
#XS Ineff= 2 , 0
       0                 10175.1       0
Bank Sta=9380.885,10870.54
Exp/Cntr=0.3,0.1

Type RM Length L Ch R = 3 ,  208115,,,
BEGIN DESCRIPTION:
END DESCRIPTION:
Bridge Culvert--1,0,-1,-1, 0
Deck Dist Width WeirC Skew NumUp NumDn MinLoCord MaxHiCord MaxSubmerge Is_Ogee
33.961750,16.000000,2.6,0, 16, 16, , , 0.95, 0, 0,0,,
 9934.61 9938.71 9940.33 9942.51 9946.88 9946.8810084.8810084.8810133.1510138.40
10140.5010153.0110155.0410165.5210171.6810177.61
  661.58  661.71  661.76  661.13  661.28  661.28  666.02  666.02  667.67  667.84
  667.88  668.15  668.18  668.33  668.51  668.59
 -338.42 -338.29 -338.24 -338.87 -338.72  658.78  663.52 -333.98 -332.33 -332.16
 -332.12 -331.85 -331.82 -331.67 -331.49 -331.41
 9934.61 9938.71 9940.33 9942.51 9973.68 9973.6810111.6810111.6810133.1510138.40
10140.5010153.0110155.0410165.5210171.6810177.61
  661.58  661.71  661.76  661.13  662.20  662.20  666.94  666.94  667.67  667.84
  667.88  668.15  668.18  668.33  668.51  668.59
 -338.42 -338.29 -338.24 -338.87 -337.80  659.70  664.44 -333.06 -332.33 -332.16
 -332.12 -331.85 -331.82 -331.67 -331.49 -331.41
Pier Skew, UpSta & Num, DnSta & Num=  ,9980.63, 2 ,10007.43, 2 , 0 , 0 , 0 ,,
    3.00    3.00
 -337.56  662.44
    3.00    3.00
 -336.64  663.36
Pier Skew, UpSta & Num, DnSta & Num=  ,10015.88, 2 ,10042.68, 2 , 0 , 0 , 0 ,,
    3.00    3.00
 -336.35  663.65
    3.00    3.00
 -335.43  664.57
Pier Skew, UpSta & Num, DnSta & Num=  ,10051.13, 2 ,10077.93, 2 , 0 , 0 , 0 ,,
    3.00    3.00
 -335.14  664.86
    3.00    3.00
 -334.22  665.78
BR Coef=-1 , 0 , 0 ,, 0 ,,,0.8,0,1,0,
WSPro=,,,, 1 ,,,, 0 ,,,, 0 ,,,,-1 ,-1 ,-1 , 0 , 0 , 0 , 0 , 0
BC Design=,, 0 ,, 0 ,,,,,,

Type RM Length L Ch R = 1 ,208095.2,249.878700,249.878700,249.878700
XS GIS Cut Line= 6
810209.505222424760001.946782456810597.514607459759787.590399906
810912.352734268759571.580384627811039.417449117759493.929725558
811424.847084194759436.044688776811490.157080632759417.847628703
#Sta/Elev= 30
9395.578738.26669458.979735.04549513.343 737.1589550.375724.16799575.382722.4965
9584.649718.10279596.062705.52719607.498685.81129653.196671.32689860.067672.0872
9884.321660.08849944.958660.81169957.086656.70999969.213645.2179 10005.6 639.838
 10054.1645.5018 10090.9642.941110108.58649.687310126.87 664.48110163.25668.2139
10247.22668.789110282.38655.791310385.35657.906710466.24675.972110537.03678.5057
10557.25689.949110617.93701.065710698.82 708.30110790.64707.531710827.14697.2692
#Mann= 3 , 0 , 0
9395.578   0.079       09395.578   0.079       010827.14   0.079       0
#XS Ineff= 2 , 0
       0                10196.47       0
Bank Sta=9395.578,10827.14
Exp/Cntr=0.3,0.1

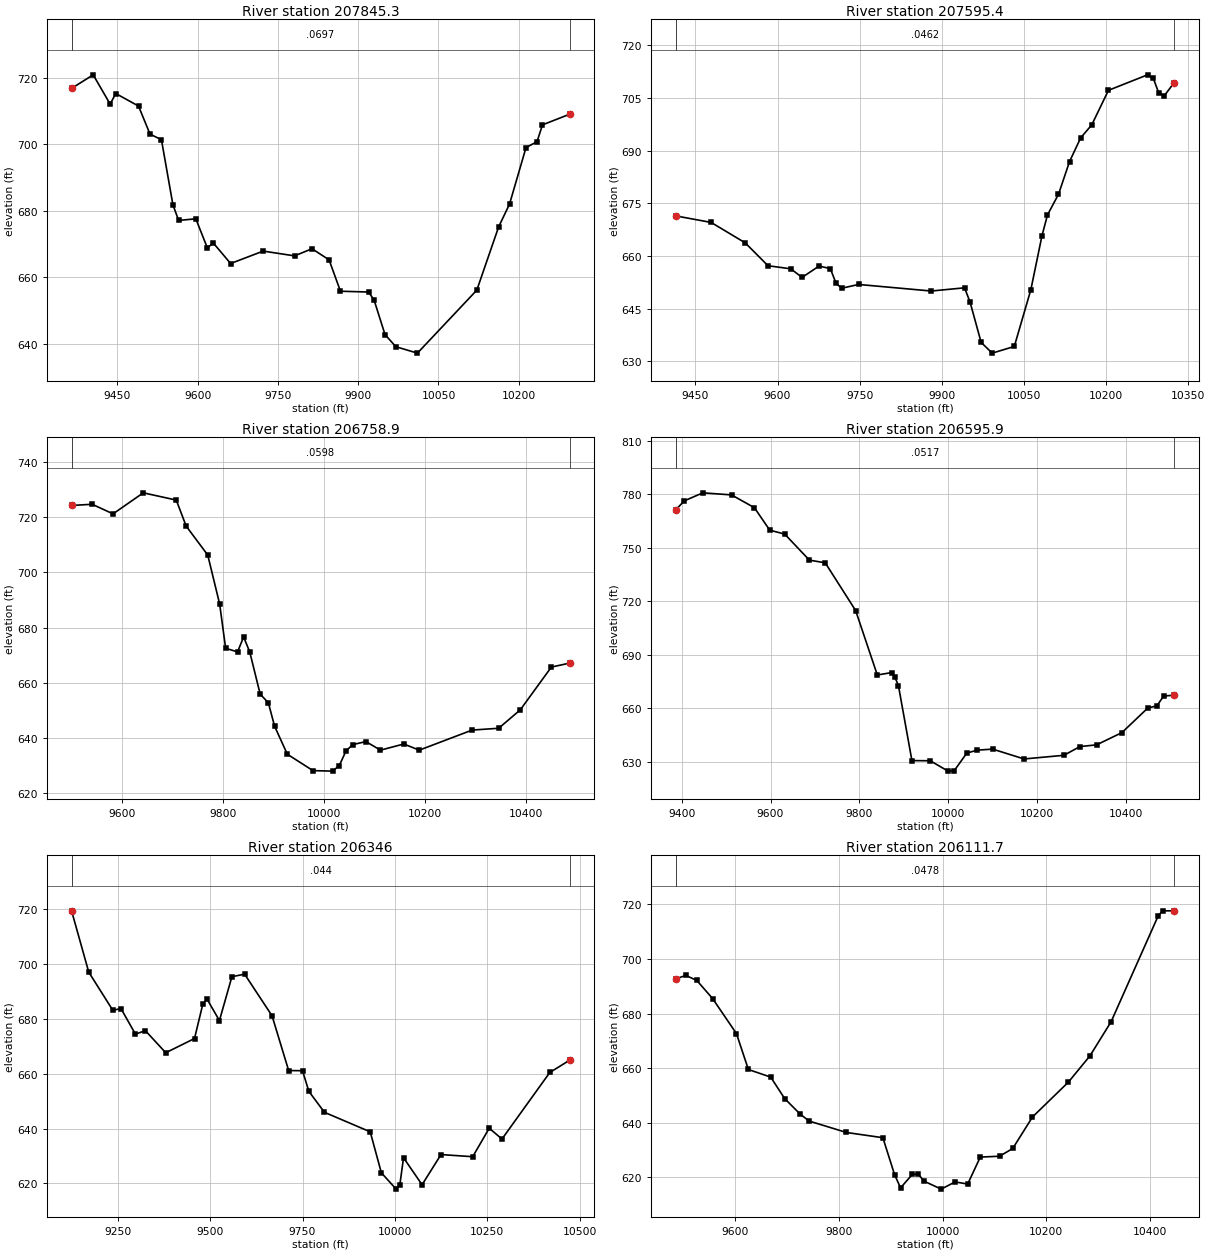
Type RM Length L Ch R = 1 ,207845.3,249.878800,249.878800,249.878800
XS GIS Cut Line= 6
810246.702873498760112.992711375810474.841188245760029.985617532
810740.446448516759921.915371914 810803.24129669759907.019445408
810967.717681564759885.315681069811133.911166283759847.507422754
#Sta/Elev= 30
9364.255716.7263 9404.68720.80489436.347712.00589446.903715.1817 9489.39711.4133
9510.819 702.9879532.247701.28259553.675681.72749564.389677.01749596.532677.5114
9618.109668.7256 9628.97670.27629661.553664.06449722.367667.80259781.023666.3688
9813.605668.50719845.537665.17139866.821655.73449919.356655.49769929.682653.0695
9950.075642.70269970.336639.051510010.65637.122610121.66656.066810162.45675.0896
10182.86681.962110213.58698.931710234.13700.699910244.41705.7637 10294.9 708.945
#Mann= 3 , 0 , 0
9364.255  0.0697       09364.255  0.0697       0 10294.9  0.0697       0
#XS Ineff= 2 , 0
       0                               0
Bank Sta=9364.255,10294.9
Exp/Cntr=0.3,0.1

Type RM Length L Ch R = 1 ,207595.4,836.496000,836.496000,836.496000
XS GIS Cut Line= 6
810303.527705598760282.631548342810504.148254176 760225.20242768
 810706.01872088760176.417484521810999.891784949760132.753298679
811096.667409433760116.516909298811192.217906918760095.760241987
#Sta/Elev= 30
9414.647671.39449478.714669.55049540.998663.73559582.604657.21929624.204656.3458
9644.853653.89849675.826657.12889696.475656.40389706.799652.23939717.124650.8129
9748.097651.88859880.804650.02099941.546650.93429951.648646.87959971.854635.4004
 9992.06 632.34110032.43634.2385 10062.7650.416210082.89665.686510092.98671.6652
10113.16677.558610133.37686.890810153.65693.621710173.93 697.33110204.35707.1566
10275.78711.570110286.01 710.70610296.24706.413610306.48 705.63810324.09709.2734
#Mann= 3 , 0 , 0
9414.647  0.0462       09414.647  0.0462       010324.09  0.0462       0
#XS Ineff= 2 , 0
       0                               0
Bank Sta=9414.647,10324.09
Exp/Cntr=0.3,0.1

Type RM Length L Ch R = 1 ,206758.9,163.018900,163.018900,163.018900
XS GIS Cut Line= 6
810728.244954642 761171.41129881810920.767845831761070.052317957
811019.654873178761007.755032566811078.251551184760966.137847009
811141.132164535760916.949612048811522.689159257760592.614366078
#Sta/Elev= 30
9499.419724.28099540.313724.70149581.608721.22719641.601728.85579706.965726.2229
9726.537716.80269769.336706.30019792.974688.50789804.793672.48829828.431671.1695
9840.488676.61899852.754671.0551 9873.23655.8702 9889.55652.67439901.816644.2344
9927.068634.06879977.853628.115610016.97627.934310030.14629.9683 10043.3635.2082
10056.46637.535610082.79 638.64310111.77 635.54710157.91637.764410188.66635.5437
 10293.4642.822410346.05643.477310388.84650.154610450.42665.666310486.43667.0981
#Mann= 3 , 0 , 0
9499.419  0.0598       09499.419  0.0598       010486.43  0.0598       0
#XS Ineff= 2 , 0
       0                               0
Bank Sta=9499.419,10486.43
Exp/Cntr=0.3,0.1

Type RM Length L Ch R = 1 ,206595.9,249.878800,249.878800,249.878800
XS GIS Cut Line= 6
810738.402617551761381.213906381810979.893904544761248.848787759
811095.238300201761167.941614743811239.543374749761046.425960449
 811318.95362109760965.043625278811570.082886811760650.231933067
#Sta/Elev= 30
9387.161771.4447 9405.51776.31069447.539780.84879512.213779.67419563.706772.5067
9598.233759.90529632.011757.6876  9687.5743.09329723.243741.58029791.767714.7866
9840.587 678.633 9872.77679.98549880.118677.42429888.137672.69429918.538630.5989
9959.785630.50669999.926624.687910013.98624.974710042.12634.794810065.21 636.441
 10100.3637.046510171.22631.515410261.13 633.57110296.81638.453510334.61639.4356
10391.61646.2966 10450.1660.143710470.24661.291910485.66666.821710508.91667.2845
#Mann= 3 , 0 , 0
9387.161  0.0517       09387.161  0.0517       010508.91  0.0517       0
#XS Ineff= 2 , 0
       0                               0
Bank Sta=9387.161,10508.91
Exp/Cntr=0.3,0.1

Type RM Length L Ch R = 1 ,  206346,234.343500,234.343500,234.343500
XS GIS Cut Line= 6
810802.193849977761654.098622866811200.326452585761467.638321258
811387.560787112 761336.42836021 811446.39503051761235.760289012
811474.087460762761000.461758941811637.272138656760724.353409315
#Sta/Elev= 30
9125.115719.4285 9171.61697.0712 9236.78683.13889258.738683.79199297.936674.4513
9324.842675.71659379.928667.66199457.767672.84689480.249685.4009 9491.49687.2627
9525.214679.40129558.937695.39879593.364696.32449667.583681.13269712.527661.1658
9749.988661.10759767.126653.59529809.334645.93529933.205638.81829963.351623.8719
10003.36617.915610013.36619.522710023.36629.353910073.51619.511110124.74630.5245
10210.52629.7425 10255.2640.1324 10289.7636.191810419.11  660.4610472.45664.9182
#Mann= 3 , 0 , 0
9125.115   0.044       09125.115   0.044       010472.45   0.044       0
#XS Ineff= 2 , 0
       0                               0
Bank Sta=9125.115,10472.45
Exp/Cntr=0.3,0.1

Type RM Length L Ch R = 1 ,206111.7,234.343600,234.343600,234.343600
XS GIS Cut Line= 6
811212.854352147761493.915312589811636.939148819761245.730300932
811729.568348915761182.364446736811842.768724202761088.536167265
811893.237895277761036.169082508 811978.13783711760930.366369489
#Sta/Elev= 30
9486.529692.75139505.419  693.999526.607692.12999557.057685.47829602.956672.6458
9625.906 659.4879668.936656.69489695.847648.8171 9726.13643.04649743.084640.5779
 9814.74636.39349885.079634.4687 9907.81620.81079919.176616.09119941.907621.0313
9953.272621.07249964.638618.51829997.443615.615610024.26618.258110048.51617.4802
10072.77627.367410109.89627.679210135.37630.529710173.37642.072310242.49 654.846
10284.15664.500210324.85677.0059 10415.4715.750910423.89  717.6710446.01717.6712
#Mann= 3 , 0 , 0
9486.529  0.0478       09486.529  0.0478       010446.01  0.0478       0
#XS Ineff= 2 , 0
       0                               0
Bank Sta=9486.529,10446.01
Exp/Cntr=0.3,0.1

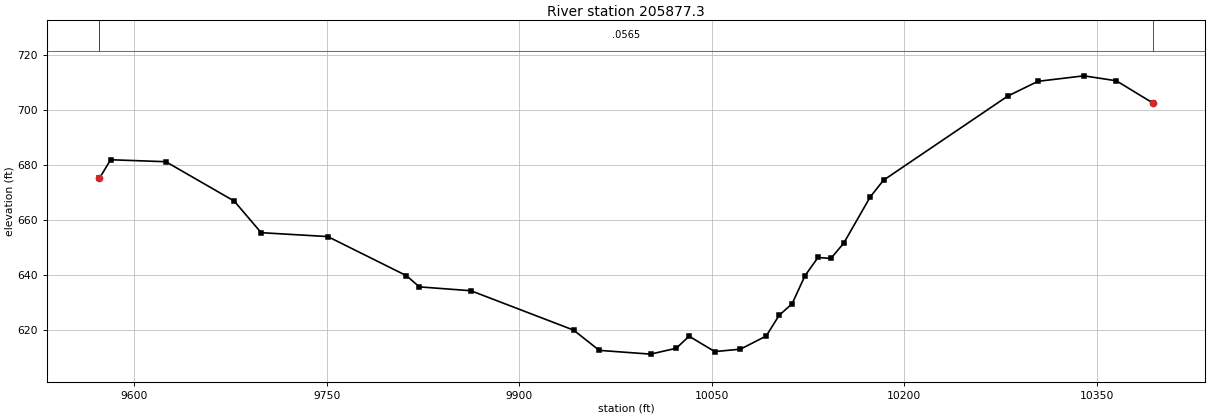
Type RM Length L Ch R = 1 ,205877.3,280.949100,280.949100,280.949100
XS GIS Cut Line= 6
811246.910509186761536.986334702811336.776560959761501.862977473
811457.357237535761469.226213932811816.912875635761449.190526421
811928.790139518761410.575483931812026.396641284 761341.09866212
#Sta/Elev= 30
9572.661675.13029581.443681.93539624.509681.22069677.794666.91629698.785655.4416
9750.713654.02499812.005639.82479822.105635.75099862.273634.3467  9942.3620.0456
9962.301 612.687 10002.3  611.32 10022.3613.449310032.31617.823610052.33612.2407
10072.34 613.123 10092.4 617.89710102.48625.412710112.57 629.61210122.66639.8081
10132.75646.427810142.83 646.07310152.92651.691210173.52668.456610183.85674.5094
10280.82705.109410304.23 710.42910339.99712.4253 10365.3 710.62810393.68702.5712
#Mann= 3 , 0 , 0
9572.661  0.0565       09572.661  0.0565       010393.68  0.0565       0
#XS Ineff= 2 , 0
       0                               0
Bank Sta=9572.661,10393.68
Exp/Cntr=0.3,0.1