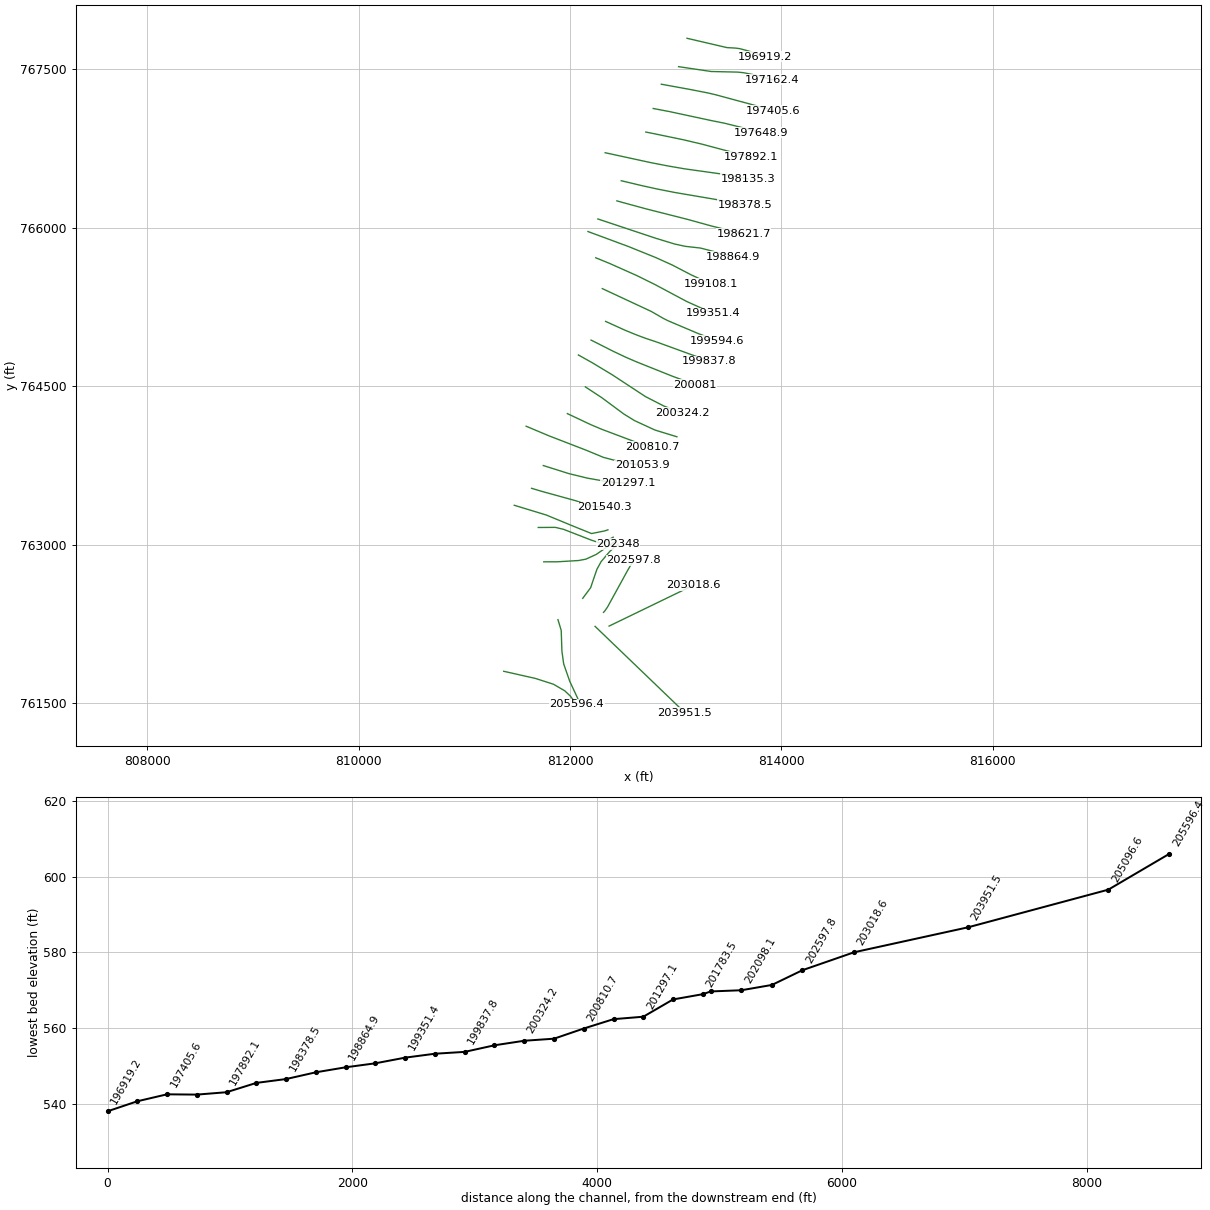
HEC-RAS study 17203_ras.prj: 17203

--- 17203_ras.g01 (geometry) --- (continued)

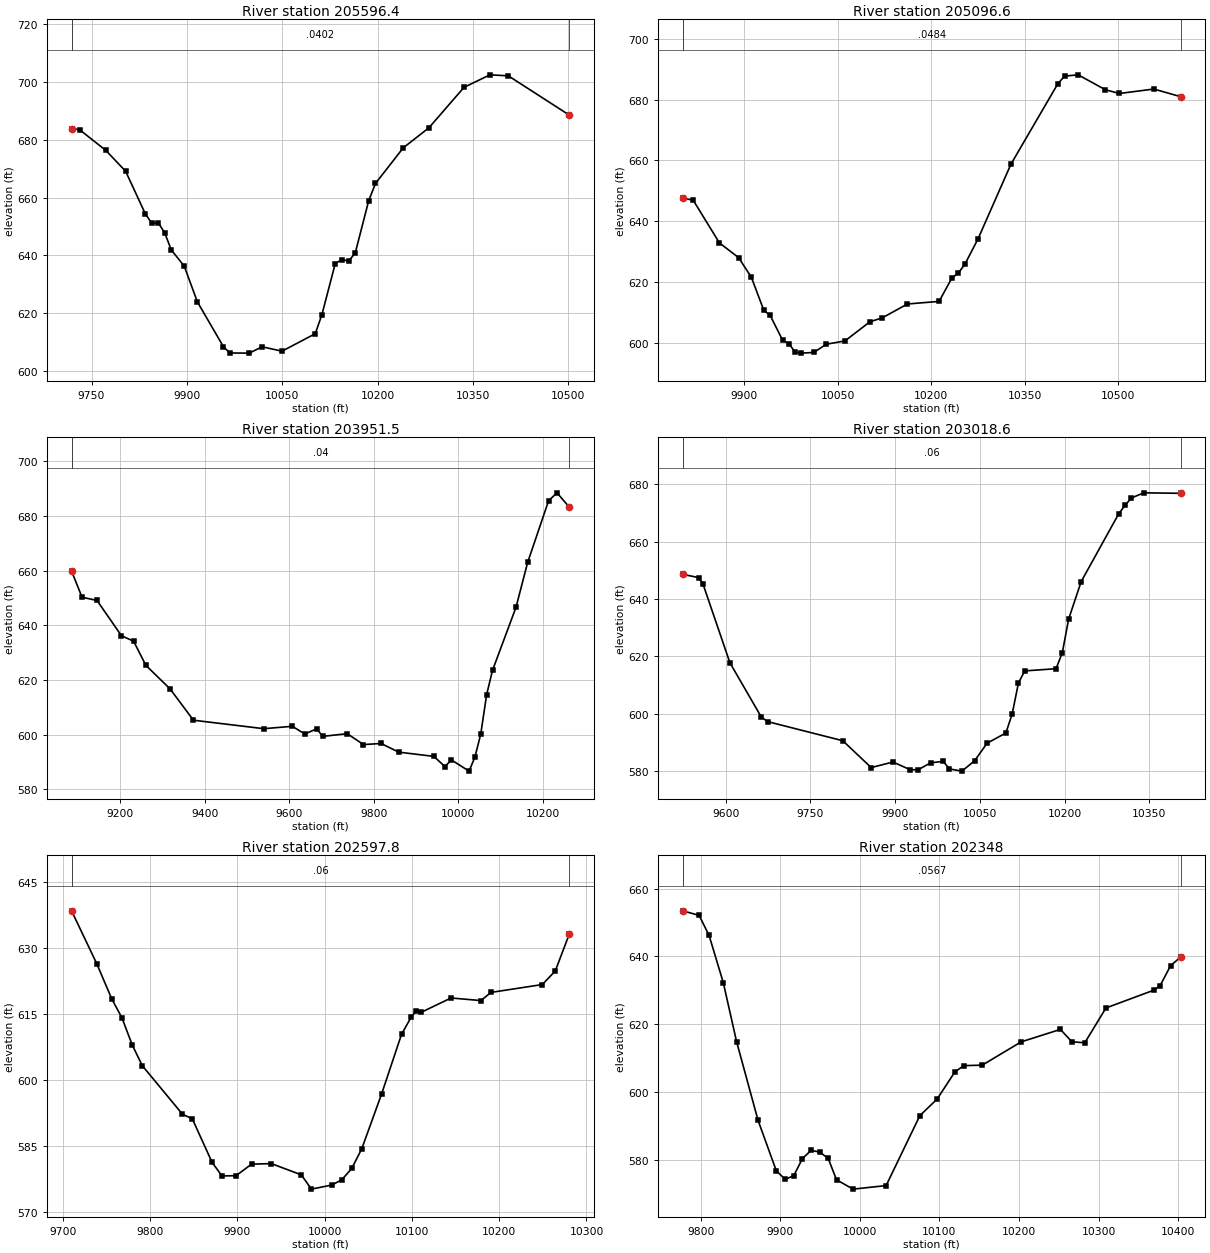
Type RM Length L Ch R = 1 ,205596.4,499.757500,499.757500,499.757500
XS GIS Cut Line= 6
811372.794623593761801.877618692811672.648026079 761734.25958587
811843.664023101761679.305889877811951.253441245761616.500633631
812001.425132313761568.793093809812063.913143212761489.132530632
#Sta/Elev= 30
9718.598683.8794 9731.22683.51769772.587 676.3149803.612669.10959834.377654.4498
9844.627651.09399854.878 651.2579865.128647.73559875.379641.8452 9895.88636.1838
9916.381623.85829957.383608.27939967.622 606.0919998.019606.040510018.34 608.243
10049.53606.712310101.89612.778210112.36619.4188 10133.3637.099710143.77638.4871
10154.24637.937710164.71640.738610185.92658.912610196.56664.875710240.22677.2176
10280.67684.1823 10335.8698.198810376.63702.535410405.57702.182310501.41688.5633
#Mann= 3 , 0 , 0
9718.598  0.0402       09718.598  0.0402       010501.41  0.0402       0
#XS Ineff= 2 , 0
       0                               0
Bank Sta=9718.598,10501.41
Exp/Cntr=0.3,0.1

Type RM Length L Ch R = 1 ,205096.6,1145.092000,1145.092000,1145.092000
XS GIS Cut Line= 6
811886.091486024762290.121451336 811916.63247289762188.306345138
811923.485058573761990.702985172811940.083884903761871.876764828
811997.175773345761707.836562882812081.728720835761526.347292771
#Sta/Elev= 30
9801.483647.52419818.101646.91649860.346632.81599891.158627.96229911.493621.5659
9931.654 610.5869941.734608.96169961.765600.7924 9971.78599.68479981.795596.9089
9991.808596.554810011.81596.780210031.81599.483110061.81600.574710101.81606.8683
10121.87 608.18110162.03612.721710212.88613.578310233.44621.294110243.88622.9349
10254.32625.828310275.21634.091510328.11 658.71110403.18685.101110414.13687.7071
10436.02688.129910479.81 683.21910501.98681.987310557.44683.452410600.32680.9526
#Mann= 3 , 0 , 0
9801.483  0.0484       09801.483  0.0484       010600.32  0.0484       0
#XS Ineff= 2 , 0
       0                               0
Bank Sta=9801.483,10600.32
Exp/Cntr=0.3,0.1

Type RM Length L Ch R = 1 ,203951.5,932.980000,932.980000,932.980000
XS GIS Cut Line= 2
812237.146120042762226.737603754813085.993689537761411.069743812
#Sta/Elev= 30
9085.433659.84199110.193650.30439145.671649.09489203.402636.20739232.267634.1768
9261.132625.36379318.221616.76889373.695605.26119540.117602.15899607.516603.0387
9637.196600.21519664.933602.11119679.679 599.3519737.409600.32829775.881596.3467
9817.487596.74379859.092593.57999942.303592.02139968.332 588.3049983.909590.7082
10025.51586.622810039.38591.752910053.25600.229810067.12614.637410080.99623.5086
10136.46646.5598 10164.2663.076410213.69685.628310233.54688.515310262.66683.2612
#Mann= 3 , 0 , 0
9085.433    0.04       09085.433    0.04       010262.66    0.04       0
#XS Ineff= 2 , 0
       0                               0
Bank Sta=9085.433,10262.66
Exp/Cntr=0.3,0.1

Type RM Length L Ch R = 1 ,203018.6,420.715500,420.715500,420.715500
XS GIS Cut Line= 2
812369.864958316 762229.50257954813163.413011819762613.834215239
#Sta/Elev= 30
9523.798648.59829551.726647.45879559.352645.38539607.282617.78789662.837 598.895
9673.948597.27619807.282590.60739857.593581.2499 9896.17583.19489926.418580.5233
9940.615580.48039962.837582.90519985.059583.4189 9996.17580.779610018.18580.0158
10040.61583.582810062.84589.735410096.17593.314510107.28599.911810118.39610.7168
 10129.5614.938410185.06615.712310196.17621.339410207.28632.9618 10229.5646.0603
10296.17669.738110307.28672.640310318.39675.200410340.61 676.99810405.52676.8275
#Mann= 3 , 0 , 0
9523.798    0.06       09523.798    0.06       010405.52    0.06       0
#XS Ineff= 2 , 0
       0                               0
Bank Sta=9523.798,10405.52
Exp/Cntr=0.3,0.1

Type RM Length L Ch R = 1 ,202597.8,249.878800,249.878800,249.878800
XS GIS Cut Line= 6
812316.626139837762359.327733394812327.777494538 762371.06112342
812354.898905957762409.806952965812547.704801855762760.900419025
812574.178386525762806.006037827812603.916966318 762850.77082448
#Sta/Elev= 30
9710.207 638.4919738.989626.52249756.427618.41639767.821614.24819779.676608.0448
9791.206603.33619837.185592.31389848.502591.25649871.135581.37899882.452 578.293
9898.525578.33379916.402580.96589939.035581.08999973.377578.53429984.932575.2921
10008.04576.209810019.57577.379910031.09579.978310042.62584.458710065.43596.9571
10088.13610.437110099.48614.451410105.17615.742510110.84615.458910144.89618.7003
10179.04618.110710190.64619.965810249.39621.748710264.22624.821410280.33633.2246
#Mann= 3 , 0 , 0
9710.207    0.06       09710.207    0.06       010280.33    0.06       0
#XS Ineff= 2 , 0
       0                               0
Bank Sta=9710.207,10280.33
Exp/Cntr=0.3,0.1

Type RM Length L Ch R = 1 ,  202348,249.878700,249.878700,249.878700
XS GIS Cut Line= 6
812120.201699495762492.087851457812195.031237289762592.444481605
812254.428696091762766.729586171812294.044360514  762838.8536708
812375.639785877762935.034951363 812454.73547573763006.264353501
#Sta/Elev= 30
9777.442653.43839797.966652.09619810.508646.19929828.341632.29419845.064614.8941
9872.059591.66719894.963576.8276 9906.25574.24859917.059575.40279927.868580.4206
9938.676582.81299949.485 582.3289960.229580.44749970.653574.14879991.499571.3953
10033.01572.439910075.36593.040410097.11597.950910119.51605.975810130.72607.7933
10153.82607.944910202.65614.7995   10252618.483910266.53614.833910282.69614.5345
10309.27   624.810370.07630.098310377.41631.413810390.52637.2636   10403639.7708
#Mann= 3 , 0 , 0
9777.442  0.0567       09777.442  0.0567       0   10403  0.0567       0
#XS Ineff= 2 , 0
       0                               0
Bank Sta=9777.442,10403
Exp/Cntr=0.3,0.1

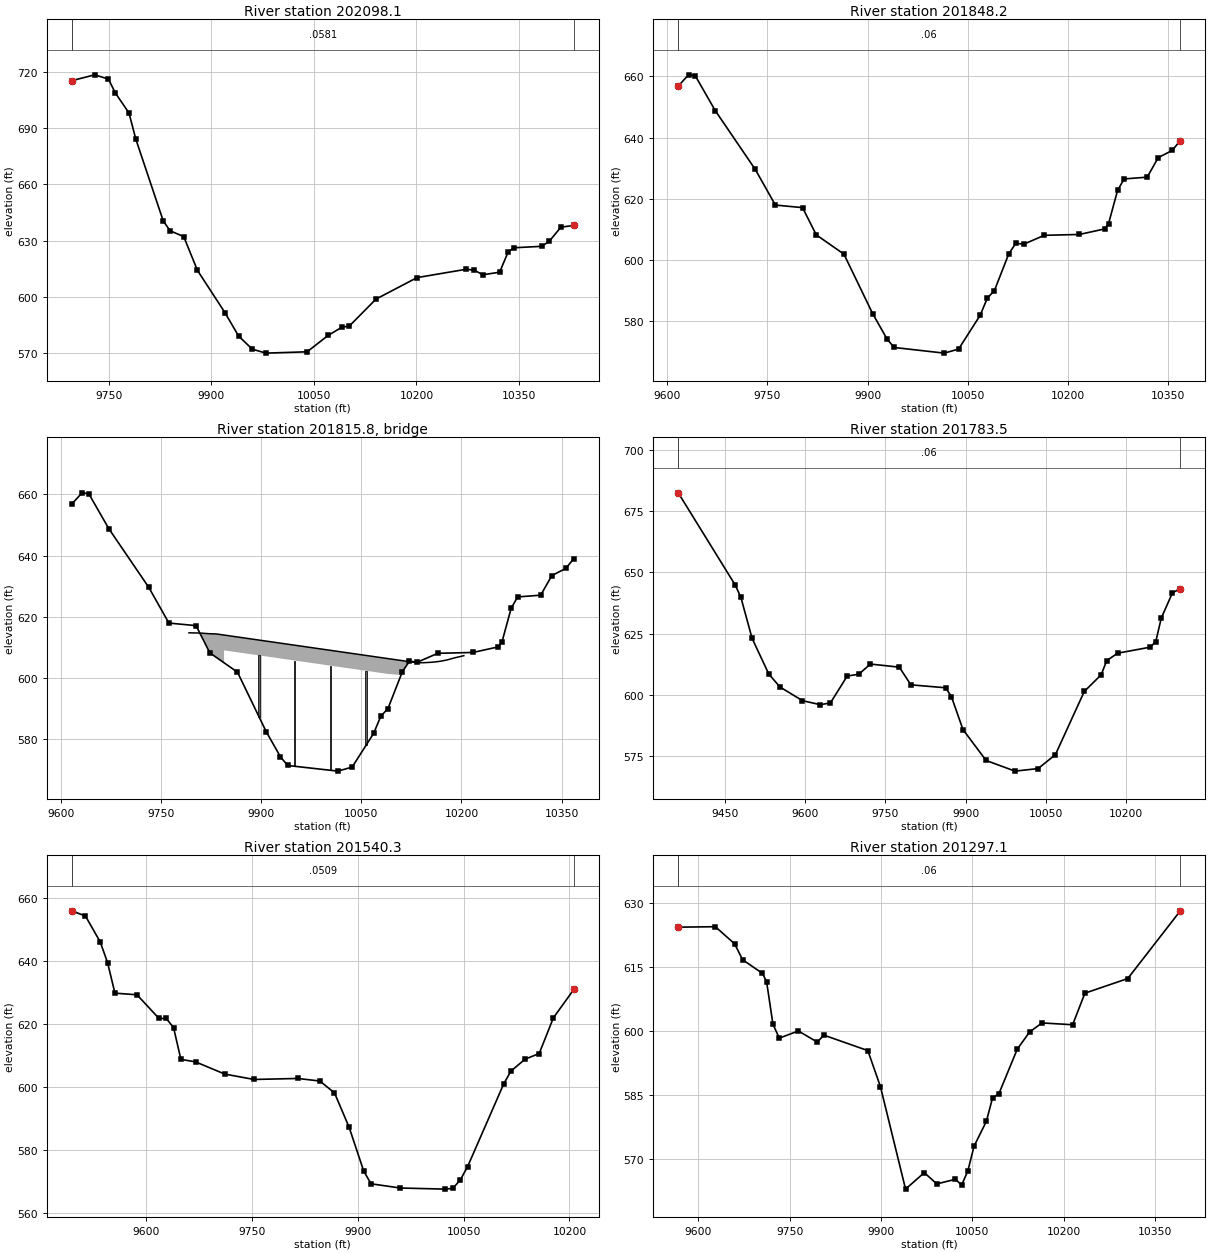
Type RM Length L Ch R = 1 ,202098.1,249.878800,249.878800,249.878800
XS GIS Cut Line= 6
811751.442158125 762837.29938106 811879.26933699762837.563966409
812081.082920221762849.742916713812150.191358522762862.594438502
812248.618925179762907.576549641812433.500337727763035.954222372
#Sta/Elev= 30
9695.985715.18169729.571718.29289749.585716.02649759.589708.69289779.597698.0088
  9789.6 684.064 9829.63640.5389 9839.66635.2208 9859.72632.06689879.779 614.069
9919.899591.61029939.958 579.0769960.018572.08619980.025569.994510040.18570.7088
10070.64579.389410091.18583.853610101.62584.347810140.83598.784210200.85610.2345
10273.03614.704910284.78614.152610297.05611.739910321.58613.121110333.84623.7176
10342.12626.1304 10382.9626.904210393.93629.4901 10411.2637.120310430.12638.0286
#Mann= 3 , 0 , 0
9695.985  0.0581       09695.985  0.0581       010430.12  0.0581       0
#XS Ineff= 2 , 0
       0                               0
Bank Sta=9695.985,10430.12
Exp/Cntr=0.3,0.1

Type RM Length L Ch R = 1 ,201848.2,64.679500,64.679500,64.679500
XS GIS Cut Line= 6
811699.609521743763162.250139775811862.172707647763163.356011793
811940.651653856763144.106458962812203.482086778763041.935755432
812301.950953156763010.099956527812408.622364187763070.737315005
#Sta/Elev= 30
9616.669656.80879632.059660.4807 9642.06 660.213 9672.06648.81159732.062629.5924
9762.062617.98739802.739617.15019823.332608.26449864.706601.97589907.622 582.603
 9929.08 574.3399939.809571.523210014.91569.680510036.37570.997310068.56     582
10079.29587.600910090.01590.106510111.47602.0854 10122.2605.584510133.57605.1897
10164.65608.122610217.19608.395510255.01610.208910260.76611.900710274.37622.7834
10284.11 626.51610318.64627.087910335.23 633.46710356.24 635.82710368.25639.0538
#Mann= 3 , 0 , 0
9616.669    0.06       09616.669    0.06       010368.25    0.06       0
#XS Ineff= 2 , 0
       0                               0
Bank Sta=9616.669,10368.25
Exp/Cntr=0.3,0.1

Type RM Length L Ch R = 3 ,201815.8,,,
BEGIN DESCRIPTION:
END DESCRIPTION:
Bridge Culvert--1,0,-1,-1, 0
Deck Dist Width WeirC Skew NumUp NumDn MinLoCord MaxHiCord MaxSubmerge Is_Ogee
20.839750,23.000000,2.6,0, 24, 24, , , 0.95, 0, 0,0,,
 9792.12 9800.60 9805.46 9811.27 9821.94 9832.60 9834.17 9834.45 9844.62 9844.62
10109.6210109.6210134.0310134.5610145.5010153.7110156.4310167.3710178.3110178.39
10189.2510200.1910203.0710203.57
  614.81  614.76  614.75  614.69  614.52  614.44  614.40  614.39  614.08  614.08
  605.78  605.78  605.02  605.01  605.08  605.18  605.22  605.49  605.94  605.95
  606.61  607.17  607.32  607.35
 -385.19 -385.24 -385.25 -385.31 -385.48 -385.56 -385.60 -385.61 -385.92  609.08
  600.78 -394.22 -394.98 -394.99 -394.92 -394.82 -394.78 -394.51 -394.06 -394.05
 -393.39 -392.83 -392.68 -392.65
 9792.12 9800.60 9805.46 9811.27 9821.94 9832.60 9834.17 9834.45 9857.86 9857.86
10122.8610122.8610134.0310134.5610145.5010153.7110156.4310167.3710178.3110178.39
10189.2510200.1910203.0710203.57
  614.81  614.76  614.75  614.69  614.52  614.44  614.40  614.39  613.66  613.66
  605.37  605.37  605.02  605.01  605.08  605.18  605.22  605.49  605.94  605.95
  606.61  607.17  607.32  607.35
 -385.19 -385.24 -385.25 -385.31 -385.48 -385.56 -385.60 -385.61 -386.34  608.66
  600.37 -394.63 -394.98 -394.99 -394.92 -394.82 -394.78 -394.51 -394.06 -394.05
 -393.39 -392.83 -392.68 -392.65
Pier Skew, UpSta & Num, DnSta & Num=  ,9897.02, 2 ,9910.26, 2 , 0 , 0 , 0 ,,
    2.00    2.00
 -387.56  612.44
    2.00    2.00
 -387.98  612.02
Pier Skew, UpSta & Num, DnSta & Num=  ,9950.42, 2 ,9963.66, 2 , 0 , 0 , 0 ,,
    2.00    2.00
 -389.23  610.77
    2.00    2.00
 -389.65  610.35
Pier Skew, UpSta & Num, DnSta & Num=  ,10003.82, 2 ,10017.06, 2 , 0 , 0 , 0 ,,
    2.00    2.00
 -390.91  609.09
    2.00    2.00
 -391.32  608.68
Pier Skew, UpSta & Num, DnSta & Num=  ,10057.22, 2 ,10070.46, 2 , 0 , 0 , 0 ,,
    2.00    2.00
 -392.58  607.42
    2.00    2.00
 -392.99  607.01
BR Coef=-1 , 0 , 0 ,, 0 ,,,0.8,0,1,0,
WSPro=,,,, 1 ,,,, 0 ,,,, 0 ,,,,-1 ,-1 ,-1 , 0 , 0 , 0 , 0 , 0
BC Design=,, 0 ,, 0 ,,,,,,

Type RM Length L Ch R = 1 ,201783.5,243.215800,243.215800,243.215800
XS GIS Cut Line= 6
811472.870081364763372.369525329811774.809352517763280.334063634
812040.601255059763170.759685963812203.482086778763104.866985857
 812329.34454757763130.039478019812358.791569841763140.408147835
#Sta/Elev= 30
9362.978682.37429469.616644.74699480.077 639.7689500.999 623.0669532.382608.4715
9553.304603.21719595.148597.67919628.681596.02329647.453596.76749678.843607.7023
9700.475608.44669722.108612.59479776.191611.32599797.823604.12089862.722602.9296
9873.539599.32759895.171585.89969938.437573.29489992.448568.9565 10035.6 569.999
10067.96575.6653 10121.9601.414610153.58608.235210163.78613.967610184.17617.0172
10245.36 619.48410255.56621.760610265.76631.274510286.79641.667210301.41643.2758
#Mann= 3 , 0 , 0
9362.978    0.06       09362.978    0.06       010301.41    0.06       0
#XS Ineff= 2 , 0
       0                               0
Bank Sta=9362.978,10301.41
Exp/Cntr=0.3,0.1

Type RM Length L Ch R = 1 ,201540.3,243.215800,243.215800,243.215800
XS GIS Cut Line= 6
811636.411122579763532.882028766 811721.88937295763507.068642527
812054.227122552763415.202469033812169.532433178763376.049740746
812234.618254123 763362.16106991812323.959265461763354.212760035
#Sta/Elev= 30
9494.155 655.9979513.573 654.3499534.465646.12829544.911 639.5639555.357629.8366
9586.673629.31879617.798 621.8079628.173  621.799638.548618.89069648.923608.7908
9669.673608.00739711.173604.12319752.673602.41349814.923602.73069846.048601.9115
9866.798598.14929887.549587.22519908.299573.28789918.674 569.261 9959.96567.9253
10024.12567.566510034.68567.824710045.23570.481510055.61574.720410106.73600.9541
10116.95605.045110137.07  608.8510157.18610.657210177.29621.999210206.31631.0252
#Mann= 3 , 0 , 0
9494.155  0.0509       09494.155  0.0509       010206.31  0.0509       0
#XS Ineff= 2 , 0
       0                               0
Bank Sta=9494.155,10206.31
Exp/Cntr=0.3,0.1

Type RM Length L Ch R = 1 ,201297.1,243.215800,243.215800,243.215800
XS GIS Cut Line= 6
811747.140047333763748.225721379811989.209385175763672.010968832
812164.202968647763629.100283218812330.898324337763599.807208397
812433.518399474763587.589669787812551.154170201763580.324000346
#Sta/Elev= 30
9566.994624.29549627.939624.40149659.538620.39869672.769616.67399705.237613.4872
9712.074611.56439722.508 601.6049732.942 598.3259764.244600.01169795.546597.3882
9805.981 599.0429878.385595.41369899.025586.98779940.302563.00239971.061566.8598
9991.567564.217910022.22565.309510032.42563.939210042.62567.292210052.82573.0488
10073.13578.911310083.26584.421610093.39 585.25810123.78595.765910144.04 599.762
 10164.3601.886810214.69601.463510234.83608.849210305.19612.273110391.51628.1178
#Mann= 3 , 0 , 0
9566.994    0.06       09566.994    0.06       010391.51    0.06       0
#XS Ineff= 2 , 0
       0                               0
Bank Sta=9566.994,10391.51
Exp/Cntr=0.3,0.1

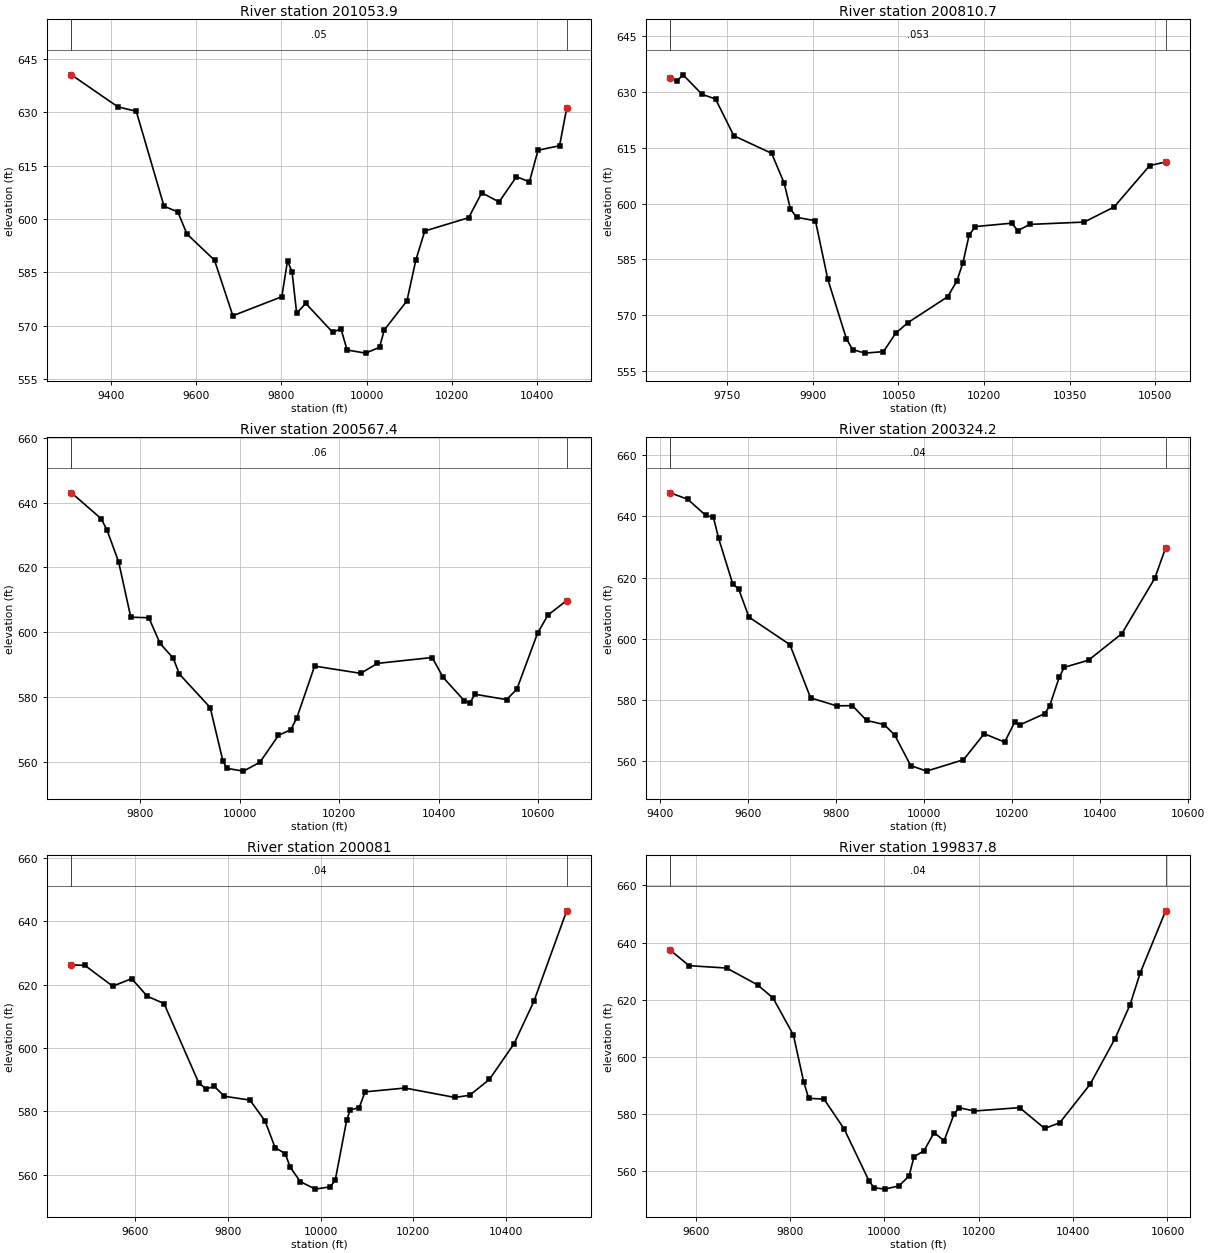
Type RM Length L Ch R = 1 ,201053.9,243.215800,243.215800,243.215800
XS GIS Cut Line= 6
811584.686797541 764120.24669404811799.221523378764029.986027135
812154.078304669763892.769903795812316.595218738763825.443102855
 812463.83038718763786.734524356  812681.5538889763749.322035747
#Sta/Elev= 30
9307.325640.45699416.155631.48519459.551630.22199524.645603.58929557.058601.9694
9578.586595.77769643.172588.43479686.229572.85439801.181578.19569814.622588.3261
9825.313585.03629836.004573.56759857.387576.3189 9920.55568.20999940.044569.2023
9954.266563.2367 9997.88562.360210030.63564.003910041.53568.851110094.85 577.024
10115.77588.485510136.66596.623410239.72600.363510270.39607.366910311.14 604.787
10351.89611.867710382.31610.429310402.52619.303410453.06620.555610469.79631.0343
#Mann= 3 , 0 , 0
9307.325    0.05       09307.325    0.05       010469.79    0.05       0
#XS Ineff= 2 , 0
       09860.417                       0
Bank Sta=9307.325,10469.79
Exp/Cntr=0.3,0.1

Type RM Length L Ch R = 1 ,200810.7,243.215700,243.215700,243.215700
XS GIS Cut Line= 6
811974.982108649764239.522727983812197.222012769 764134.67777234
812302.884914973764090.162288773812602.546761448763977.415405857
812706.657382359763944.507977449812782.060328294763924.322697973
#Sta/Elev= 30
9650.297633.77779661.433632.83089672.548634.52159705.894629.27379729.368628.0507
9761.471618.18149827.656613.47579849.638605.50129860.629 598.535 9871.62596.3047
9904.483595.38189926.183579.67479958.732563.72829969.582560.84299991.282559.8906
10023.69560.292310045.12565.225210066.56568.066810136.21575.0228 10152.3579.2415
10163.02584.178210173.74591.523710184.45593.823210248.43594.739810259.06 592.749
10280.33594.411310375.41595.034210427.85599.090310490.12610.176410518.13611.1536
#Mann= 3 , 0 , 0
9650.297   0.053       09650.297   0.053       010518.13   0.053       0
#XS Ineff= 2 , 0
       0                               0
Bank Sta=9650.297,10518.13
Exp/Cntr=0.3,0.1

Type RM Length L Ch R = 1 ,200567.4,243.215800,243.215800,243.215800
XS GIS Cut Line= 6
812144.657268352764492.664529415812299.250263876764391.197379112
812507.597021765764236.786191784812609.772892584 764173.54184062
812803.746619457764084.145419077813011.477611734764020.223775638
#Sta/Elev= 30
9661.823642.99899721.313635.07179733.186631.59699756.819621.64349781.133604.6542
 9817.43604.48269840.016 596.5719866.418592.02949878.892587.1058 9940.78 576.808
9966.212560.41859974.236558.052610007.75557.198810040.85559.942610078.07568.2328
10102.88569.954510114.93573.6127 10150.7589.583110243.37587.343810277.01590.4191
10387.19592.229810408.87586.129410451.94578.854110462.52578.1264 10473.1580.9006
10536.53579.236710557.33582.471310598.92 599.70810619.71605.282910657.48609.8012
#Mann= 3 , 0 , 0
9661.823    0.06       09661.823    0.06       010657.48    0.06       0
#XS Ineff= 2 , 0
       0                               0
Bank Sta=9661.823,10657.48
Exp/Cntr=0.3,0.1

Type RM Length L Ch R = 1 ,200324.2,243.215800,243.215800,243.215800
XS GIS Cut Line= 6
812079.470656254764793.987483081812209.604466287764721.273858486
812399.743699532764606.546100096812713.904246307764400.482883035
812886.006193163764312.069807866813058.244973442764245.108447635
#Sta/Elev= 30
 9423.34647.73329462.753645.61679503.575640.36939521.248639.66859532.719632.9409
9564.809 618.036 9578.67616.16499601.858607.06169694.898598.04679741.911580.6329
9800.825578.03089836.929578.0835 9869.17573.24129909.138571.89439933.208 568.425
9969.312558.475710005.38556.655610089.27560.374710136.46568.898510182.95566.1516
10205.82572.750710217.26571.764910273.73575.466610284.85577.874910307.09587.4542
10318.21590.618310373.53592.968810449.22601.659610524.06619.779210548.67 629.752
#Mann= 3 , 0 , 0
 9423.34    0.04       0 9423.34    0.04       010548.67    0.04       0
#XS Ineff= 2 , 0
       0                10109.99       0
Bank Sta=9423.34,10548.67
Exp/Cntr=0.3,0.1

Type RM Length L Ch R = 1 ,  200081,243.215700,243.215700,243.215700
XS GIS Cut Line= 6
812198.815493165764935.280795736812411.980827176 764827.52480039
 812528.73442372764772.442794716812629.662078429764728.824542595
 812965.03596751764594.596478448813181.858232592764514.810104041
#Sta/Elev= 30
9461.768626.31869491.108626.07399551.055619.53629591.953621.92369625.568616.3692
9661.885614.0482 9737.13 588.9199753.412587.08779770.301587.90519792.415  584.77
9847.435583.58199880.117 576.9899901.905568.56469923.692566.66219934.586562.3797
 9956.24557.83349988.659555.4578   10021556.189910031.76558.221810056.61577.2558
10064.05580.446410083.63581.228210096.35586.171410182.46587.3824 10290.1584.4168
10322.24 585.08810364.97590.100910418.39601.401210461.13614.762910531.96643.3358
#Mann= 3 , 0 , 0
9461.768    0.04       09461.768    0.04       010531.96    0.04       0
#XS Ineff= 2 , 0
       0                               0
Bank Sta=9461.768,10531.96
Exp/Cntr=0.3,0.1

Type RM Length L Ch R = 1 ,199837.8,243.215800,243.215800,243.215800
XS GIS Cut Line= 6
812336.727932063765111.761234717812522.978666527765027.258629292
812634.690475576764981.655757515812712.135980709764952.913974912
812831.133440735 764912.91716687813315.999741459764735.975048944
#Sta/Elev= 30
9546.619637.2968 9586.06631.89949665.914631.05659731.503625.16659764.141620.5811
9807.345607.63159828.947591.33649839.749585.49639872.148585.20879914.814574.7837
9967.973 556.4349978.506554.2286   10001553.718510031.24554.858810052.36558.3302
10062.92565.026610084.09567.1509 10105.4573.468510126.72570.657610148.04580.1231
10158.69582.190910190.67581.047710286.59582.227810339.88574.935710371.86576.9604
 10435.8590.332710489.01606.409410520.83618.294710542.03629.262810596.12651.0808
#Mann= 3 , 0 , 0
9546.619    0.04       09546.619    0.04       010596.12    0.04       0
#XS Ineff= 2 , 0
       0                               0
Bank Sta=9546.619,10596.12
Exp/Cntr=0.3,0.1

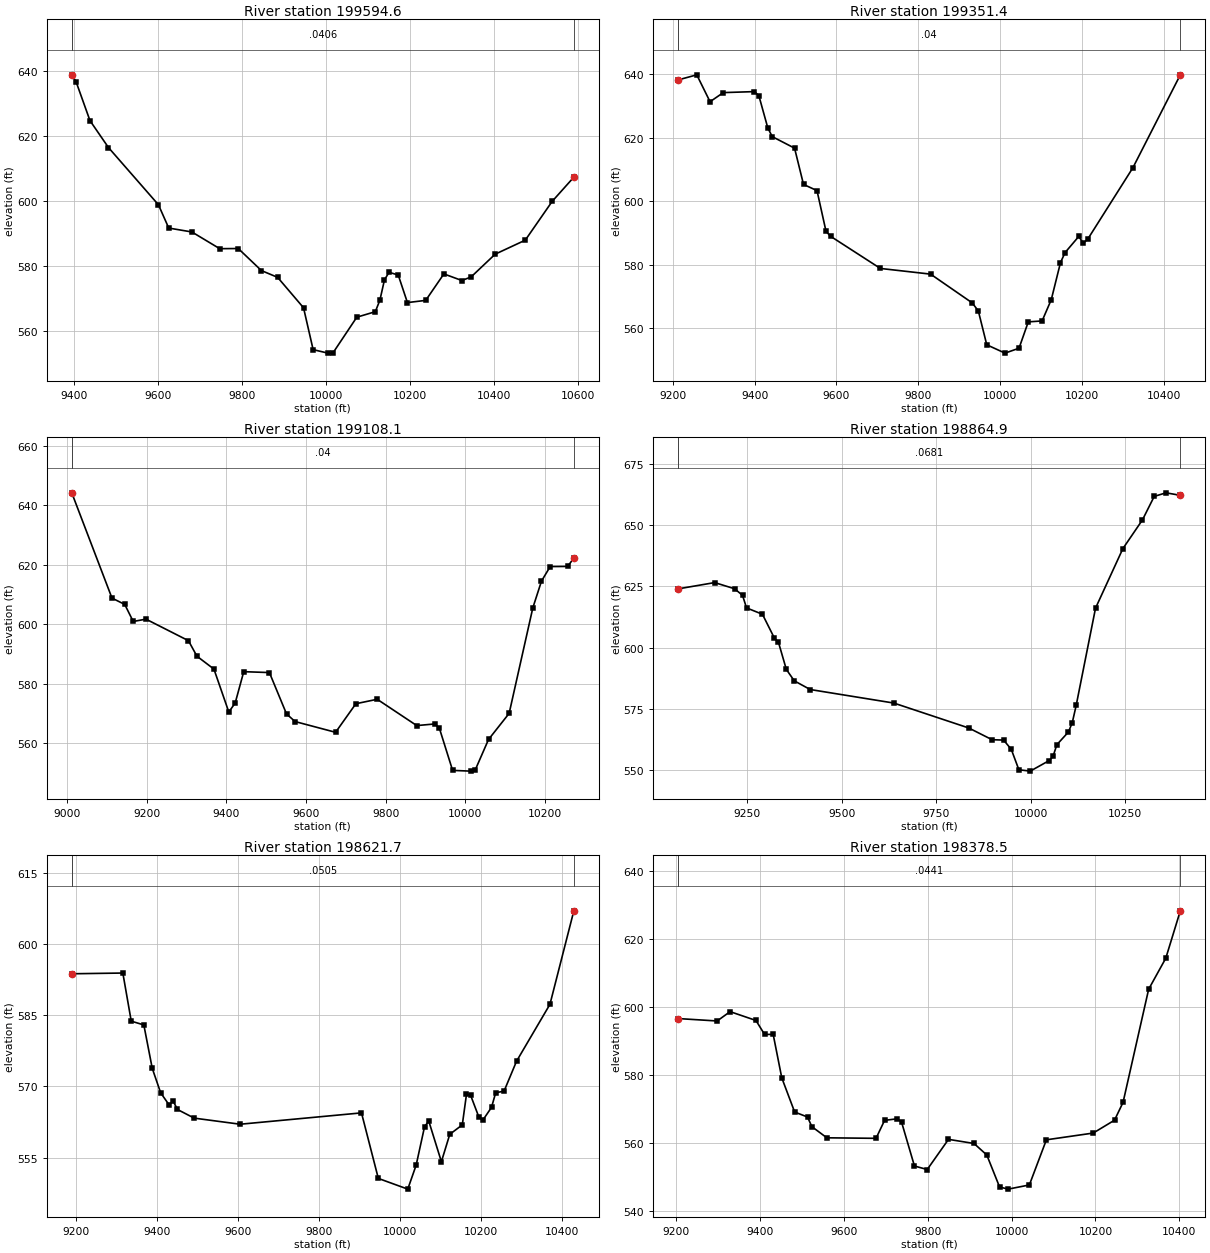
Type RM Length L Ch R = 1 ,199594.6,243.215800,243.215800,243.215800
XS GIS Cut Line= 6
812305.602213573765421.951038475812767.209235124765206.947150744
812883.564456404765139.911727793812928.310952492765117.554414928
 813211.55361973764997.463247373813393.169096186764928.518939177
#Sta/Elev= 30
9394.233 638.9089404.524636.77199437.552624.81299481.691616.50739600.609598.9034
9625.146591.73359680.321590.52819746.531 585.3849790.671585.43349845.845578.6423
9884.413576.55759946.112567.19549968.971554.301410004.34553.229610016.06553.2607
10072.97564.293610117.01 565.98710127.93569.520410138.86575.805410149.79578.1164
10171.64577.267610193.49568.790710237.06569.468310280.31577.615510323.11575.5851
10345.19576.690410402.42583.689610474.16588.010910538.39599.982810589.79 607.403
#Mann= 3 , 0 , 0
9394.233  0.0406       09394.233  0.0406       010589.79  0.0406       0
#XS Ineff= 2 , 0
       0                               0
Bank Sta=9394.233,10589.79
Exp/Cntr=0.3,0.1

Type RM Length L Ch R = 1 ,199351.4,243.215800,243.215800,243.215800
XS GIS Cut Line= 6
 812243.04400997 765713.87960024812375.163946972765659.773473259
812630.915472293765545.861206001812804.495719527765460.157046277
813104.365674222765300.070673074813351.415565562765188.531012219
#Sta/Elev= 30
9213.375638.23729258.712639.82579291.131631.36079323.549634.23239399.596 634.546
9410.504 633.2569432.319623.11589443.227620.36699497.765616.73669519.611605.3246
9552.614603.36929574.616590.56699585.618     589  9707.6578.85969830.286577.0735
9932.188568.00739947.047565.46969967.602 554.82610012.23552.1967 10046.5553.7435
10069.13562.038910102.88562.329810125.38 569.05510147.88580.719110159.13583.8691
10192.53588.9347 10203.6586.815110214.68588.129410324.98610.597910440.79  639.83
#Mann= 3 , 0 , 0
9213.375    0.04       09213.375    0.04       010440.79    0.04       0
#XS Ineff= 2 , 0
       0                               0
Bank Sta=9213.375,10440.79
Exp/Cntr=0.3,0.1

Type RM Length L Ch R = 1 ,199108.1,243.215700,243.215700,243.215700
XS GIS Cut Line= 6
812169.940426753765961.978147009812551.305169401765820.777094207
812812.060954404765715.463964321812969.392928582765644.249942713
813147.541554555765551.528758726 813329.37504688765467.764650315
#Sta/Elev= 30
9011.205644.22079112.263608.84129144.287606.72919165.635600.99139197.659601.7755
9304.403594.53689325.752589.3189 9368.45584.98779405.807570.5787 9421.85573.5816
9443.349 584.1249507.847583.82319550.846569.92569572.425567.35729674.161563.7484
9725.143573.35299778.763574.84619878.134566.00819923.175566.55349934.436565.3561
9968.217550.952110013.31 550.70410024.61550.957710058.49 561.339 10110.3570.1157
10169.71605.521510191.58614.565310213.46619.4432 10257.2619.482510272.89622.2854
#Mann= 3 , 0 , 0
9011.205    0.04       09011.205    0.04       010272.89    0.04       0
#XS Ineff= 2 , 0
       09812.827                       0
Bank Sta=9011.205,10272.89
Exp/Cntr=0.3,0.1

Type RM Length L Ch R = 1 ,198864.9,243.215800,243.215800,243.215800
XS GIS Cut Line= 6
812263.498039063766080.875034966812803.218930011765900.893908389
812988.344675484 765844.33307274813089.913738685765822.097479273
813235.151924765765805.612298156813541.347383134765725.575350483
#Sta/Elev= 30
9067.197623.94799163.653626.49679216.359623.98619237.442621.29739247.984616.1857
9290.149613.58399321.773603.87029332.314602.30249353.397591.1032 9374.48586.4465
9416.645582.90539638.005577.39189836.581567.22259898.192562.45139928.735562.2985
9948.951 558.5429969.116550.20319999.216549.645510049.49553.960510059.59555.6768
 10069.7560.429610100.31565.599710110.56569.449310120.81576.411810172.05616.0613
 10244.5640.350610296.35652.059710327.49661.633210358.71663.083610396.55 662.069
#Mann= 3 , 0 , 0
9067.197  0.0681       09067.197  0.0681       010396.55  0.0681       0
#XS Ineff= 2 , 0
       09798.237                       0
Bank Sta=9067.197,10396.55
Exp/Cntr=0.3,0.1

Type RM Length L Ch R = 1 ,198621.7,243.215800,243.215800,243.215800
XS GIS Cut Line= 6
812443.543453539766252.200949523812488.273052655766239.455826711
812718.745648864766176.728996575813114.681389019766076.325326367
813338.898685898766014.183125913813642.290179113765939.574077979
#Sta/Elev= 30
9189.544593.78449315.572593.93879336.299583.78439367.391582.98249388.118 573.826
9408.846568.66289429.573 566.1269439.937566.88789450.301565.14119491.679563.3129
9605.161562.02659904.469564.4217 9945.99550.588510018.67548.327610039.42553.4095
10060.16561.537910070.53562.674710101.64554.116310122.34559.901310153.23561.8902
10163.53568.325710173.82568.116210194.42563.469110204.72 562.98610225.31565.5875
10235.61568.678810256.21568.9991 10287.1575.329910369.49587.333310428.48607.0699
#Mann= 3 , 0 , 0
9189.544  0.0505       09189.544  0.0505       010428.48  0.0505       0
#XS Ineff= 2 , 0
       09789.789                       0
Bank Sta=9189.544,10428.48
Exp/Cntr=0.3,0.1

Type RM Length L Ch R = 1 ,198378.5,243.215800,243.215800,243.215800
XS GIS Cut Line= 6
812484.773716578766442.539649272 812688.00515503766394.331420016
812829.981984631766363.254918875812993.306191689766331.168463627
 813465.80145991 766250.77099736813658.903863993766213.538384279
#Sta/Elev= 30
9205.709596.70659298.464595.9976 9329.29598.74679390.942596.14959411.493592.0329
9431.978592.06269452.451579.28519483.162569.22149513.872 567.7499524.109564.9299
9559.919561.63769677.135561.48659697.518566.77539728.083567.23339738.228566.1544
9768.661553.34729799.094 552.3079849.816561.18179910.683559.96649941.116556.5809
 9971.55547.18129991.838 546.54510042.56547.769310083.13561.0502 10194.7 563.034
10245.51566.818710265.84572.058410326.85605.331210367.69614.453810402.32628.3945
#Mann= 3 , 0 , 0
9205.709  0.0441       09205.709  0.0441       010402.32  0.0441       0
#XS Ineff= 2 , 0
       09819.224                       0
Bank Sta=9205.709,10402.32
Exp/Cntr=0.3,0.1

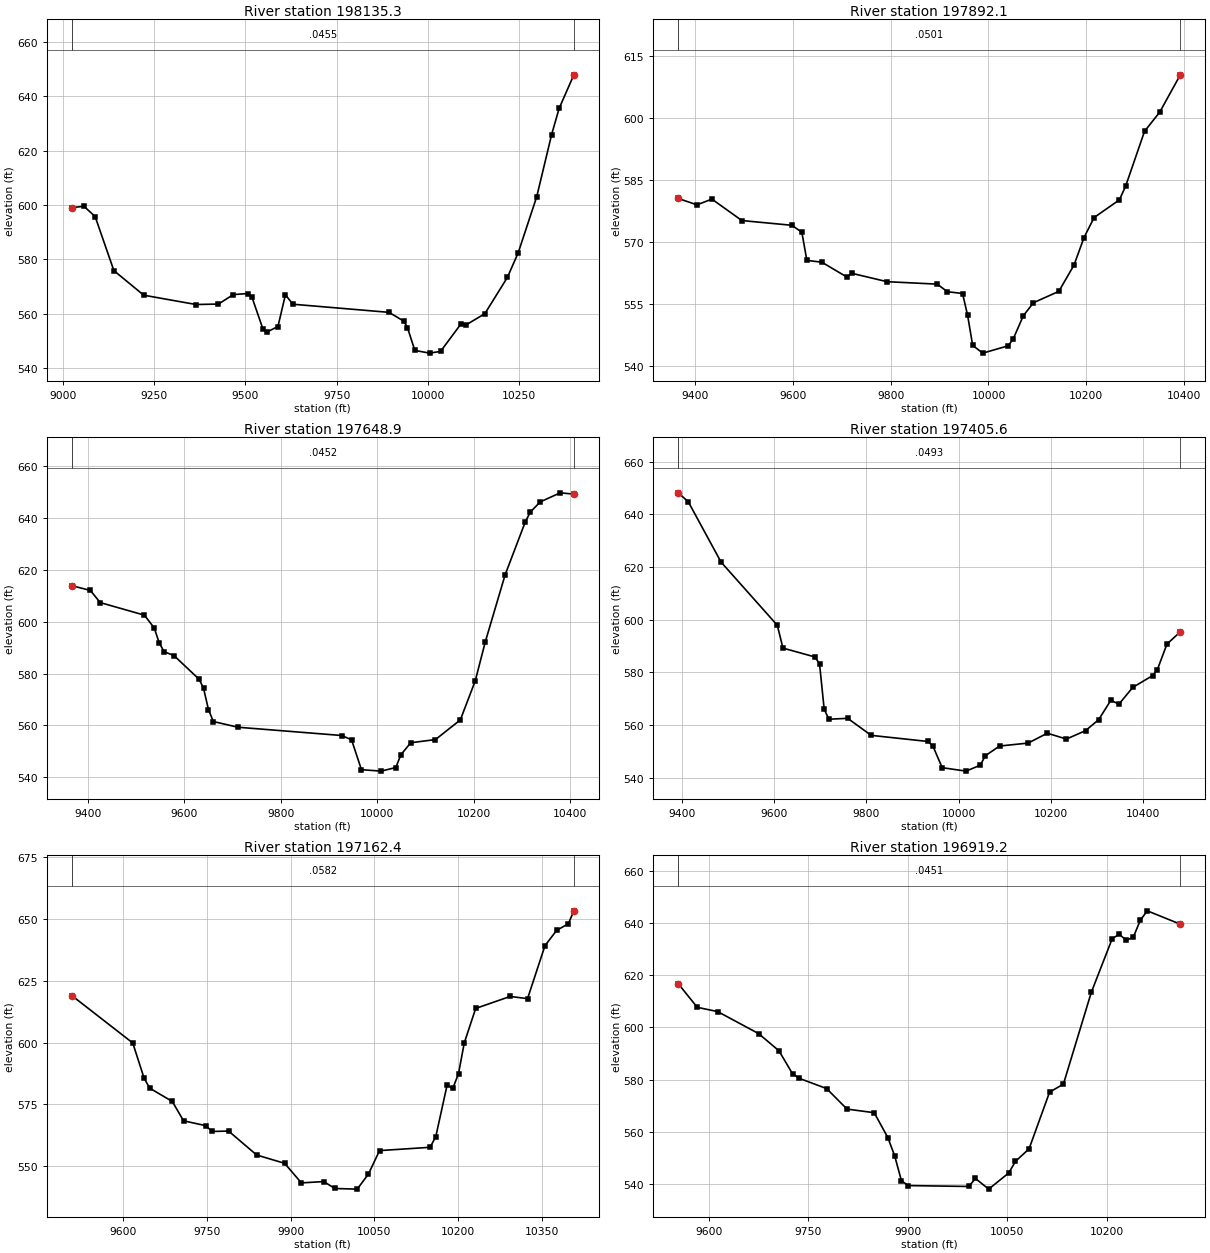
Type RM Length L Ch R = 1 ,198135.3,243.215700,243.215700,243.215700
XS GIS Cut Line= 6
812332.587901547766707.563559155812765.612568593766613.567439618
812930.965750013766581.606272544813086.715877554766554.784039412
813475.947887042  766500.4234726813684.579083408766460.291533891
#Sta/Elev= 30
9024.588 599.0519057.836599.5478 9088.61595.7756  9139.9575.88429221.704566.8374
 9364.84563.41199426.184563.5753 9467.08567.06229507.823567.45389518.008566.1414
9548.564554.22719558.749553.28669589.304555.31019609.674567.00669630.044 563.517
9893.512560.5274 9933.86557.2874 9943.94554.9374  9964.1546.525710004.42 545.525
10034.67546.162310091.19556.3866 10105.3555.989110155.89560.027110217.65573.3835
10247.21582.423510298.02603.077910338.85625.955210359.26635.527210399.67647.9104
#Mann= 3 , 0 , 0
9024.588  0.0455       09024.588  0.0455       010399.67  0.0455       0
#XS Ineff= 2 , 0
       09786.381                       0
Bank Sta=9024.588,10399.67
Exp/Cntr=0.3,0.1

Type RM Length L Ch R = 1 ,197892.1,243.215800,243.215800,243.215800
XS GIS Cut Line= 6
 812717.52437281766903.143202503812817.183979934766883.135645012
813070.444625082766830.574276026813242.841238669766790.143403478
813485.787099533766725.285158419813715.891991169766667.927579954
#Sta/Elev= 30
9366.063 580.5119404.286 578.9699434.885580.3541 9496.12575.16249598.251574.0163
9618.677572.3314 9628.89565.51769659.529565.08029710.595561.49199720.808562.3888
9792.675560.36219895.389559.76649916.022557.9381 9947.06557.50139957.406 552.201
9967.752544.93149988.444543.064110040.21544.836810050.56546.487710071.26552.1225
10091.97555.271210143.73558.0118 10174.7564.360310195.31571.058410215.92575.9011
10267.45580.162110280.11583.426110318.98596.7889 10349.9601.394510392.04610.4468
#Mann= 3 , 0 , 0
9366.063  0.0501       09366.063  0.0501       010392.04  0.0501       0
#XS Ineff= 2 , 0
       09695.856                       0
Bank Sta=9366.063,10392.04
Exp/Cntr=0.3,0.1

Type RM Length L Ch R = 1 ,197648.9,243.215800,243.215800,243.215800
XS GIS Cut Line= 6
812787.085998407767126.024329272812939.515366909767097.079799475
813335.753902534767012.017021979 813460.99255792766986.900639482
 813649.19608708766940.250466327813802.261423452766898.353454895
#Sta/Elev= 30
9366.779613.8181 9405.37611.98269425.727607.30899517.336602.47139537.744597.5361
9547.956591.84469558.168588.40919578.592586.92519630.901 577.7649639.863574.3929
9650.074566.14589660.286 561.5249711.375559.32599926.435556.14619946.829554.4712
 9967.22542.987810008.02542.433610038.62543.825110048.83548.690110069.33553.3479
10120.69554.583110172.22562.1413 10203.2577.198310223.86592.120310265.24618.0807
10306.71638.271510317.08642.095610337.81646.064210379.28 649.55810407.55649.0577
#Mann= 3 , 0 , 0
9366.779  0.0452       09366.779  0.0452       010407.55  0.0452       0
#XS Ineff= 2 , 0
       0                               0
Bank Sta=9366.779,10407.55
Exp/Cntr=0.3,0.1

Type RM Length L Ch R = 1 ,197405.6,243.215700,243.215700,243.215700
XS GIS Cut Line= 6
 812863.61754902767355.641892291813136.869206213767305.946128317
813294.115255747767275.167941882813366.045756929767258.987481654
813777.770688169767148.086494148813922.820332523767106.645010466
#Sta/Elev= 30
9391.752648.17929413.485644.79739484.633621.87899606.601597.89479618.886589.2253
 9687.96585.8747 9698.15583.3217 9708.34565.9846 9718.53562.21969759.289562.5584
9810.237556.09399933.323 553.7689943.642552.20789964.281543.814610016.03542.5119
10047.12544.787510057.49548.310610088.58552.035410150.77553.164110192.23556.9121
10233.69554.688410275.15557.878110303.57562.038510329.85569.352410347.77567.9795
10377.49574.284210420.57578.782510430.97581.067710451.77590.771110480.71595.3968
#Mann= 3 , 0 , 0
9391.752  0.0493       09391.752  0.0493       010480.71  0.0493       0
#XS Ineff= 2 , 0
       0                10215.32       0
Bank Sta=9391.752,10480.71
Exp/Cntr=0.3,0.1

Type RM Length L Ch R = 1 ,197162.4,243.215800,243.215800,243.215800
XS GIS Cut Line= 6
813027.145707115767521.731528477813336.325864246767475.924442291
813588.640137771767470.172041528813643.698039026767464.190523366
813761.974169082 767440.51816615813914.395433031767396.956581672
#Sta/Elev= 30
9507.578619.04089616.886599.8418 9637.12585.63959647.237581.54789687.705576.1709
9707.939568.32629748.387566.33199758.454564.01529788.655564.17739838.916554.4891
9889.049551.12149919.069543.19329959.077543.73299979.087540.931410019.11540.6719
10039.12546.719110059.13556.269410149.79557.606410159.94561.918410180.24582.8125
10190.43581.446610200.68587.420710210.92599.801310231.42613.826810293.34618.6841
10324.38617.787510355.69639.262410376.62645.440910397.54648.103110407.37653.3436
#Mann= 3 , 0 , 0
9507.578  0.0582       09507.578  0.0582       010407.37  0.0582       0
#XS Ineff= 2 , 0
       0                               0
Bank Sta=9507.578,10407.37
Exp/Cntr=0.3,0.1

Type RM Length L Ch R = 1 ,196919.2,243.215800,243.215800,243.215800
XS GIS Cut Line= 6
813107.026622832767790.106259927813484.860541493767702.088370413
813570.690720201767697.187879756813606.841002613767691.876799881
813690.104193926767669.679858655813841.631233579767616.379211141
#Sta/Elev= 30
 9553.81616.71489582.532607.67599613.335606.03359674.942597.62689705.745591.0332
9726.281582.20719736.548580.44769777.619576.55759808.423568.69159849.494567.3009
9870.029557.78219880.297550.82979890.565541.20669900.832539.38569992.211539.0445
10002.22542.104610022.22538.025510052.48544.222210062.59548.657510083.11553.4528
10114.09575.201510134.92578.244510176.95613.377810208.64634.031510219.21635.6259
10229.77633.419810240.34634.4861 10250.9641.029710261.47644.6432 10311.3639.5287
#Mann= 3 , 0 , 0
 9553.81  0.0451       0 9553.81  0.0451       0 10311.3  0.0451       0
#XS Ineff= 2 , 0
       0                               0
Bank Sta=9553.81,10311.3
Exp/Cntr=0.3,0.1