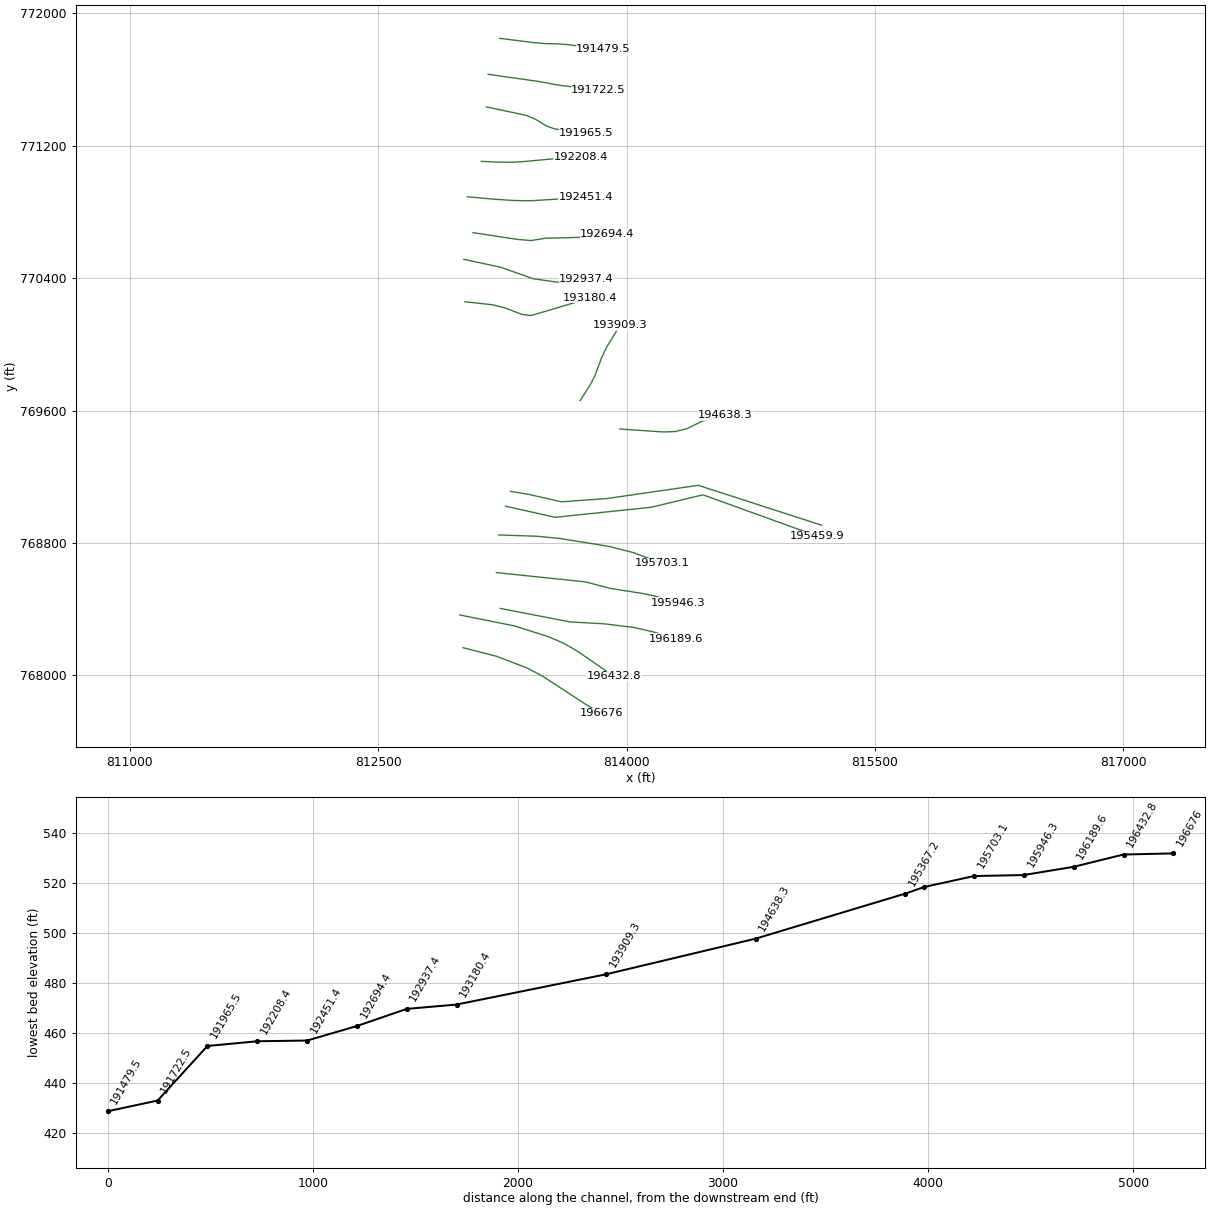
HEC-RAS study 17203_ras.prj: 17203

--- 17203_ras.g01 (geometry) --- (continued)

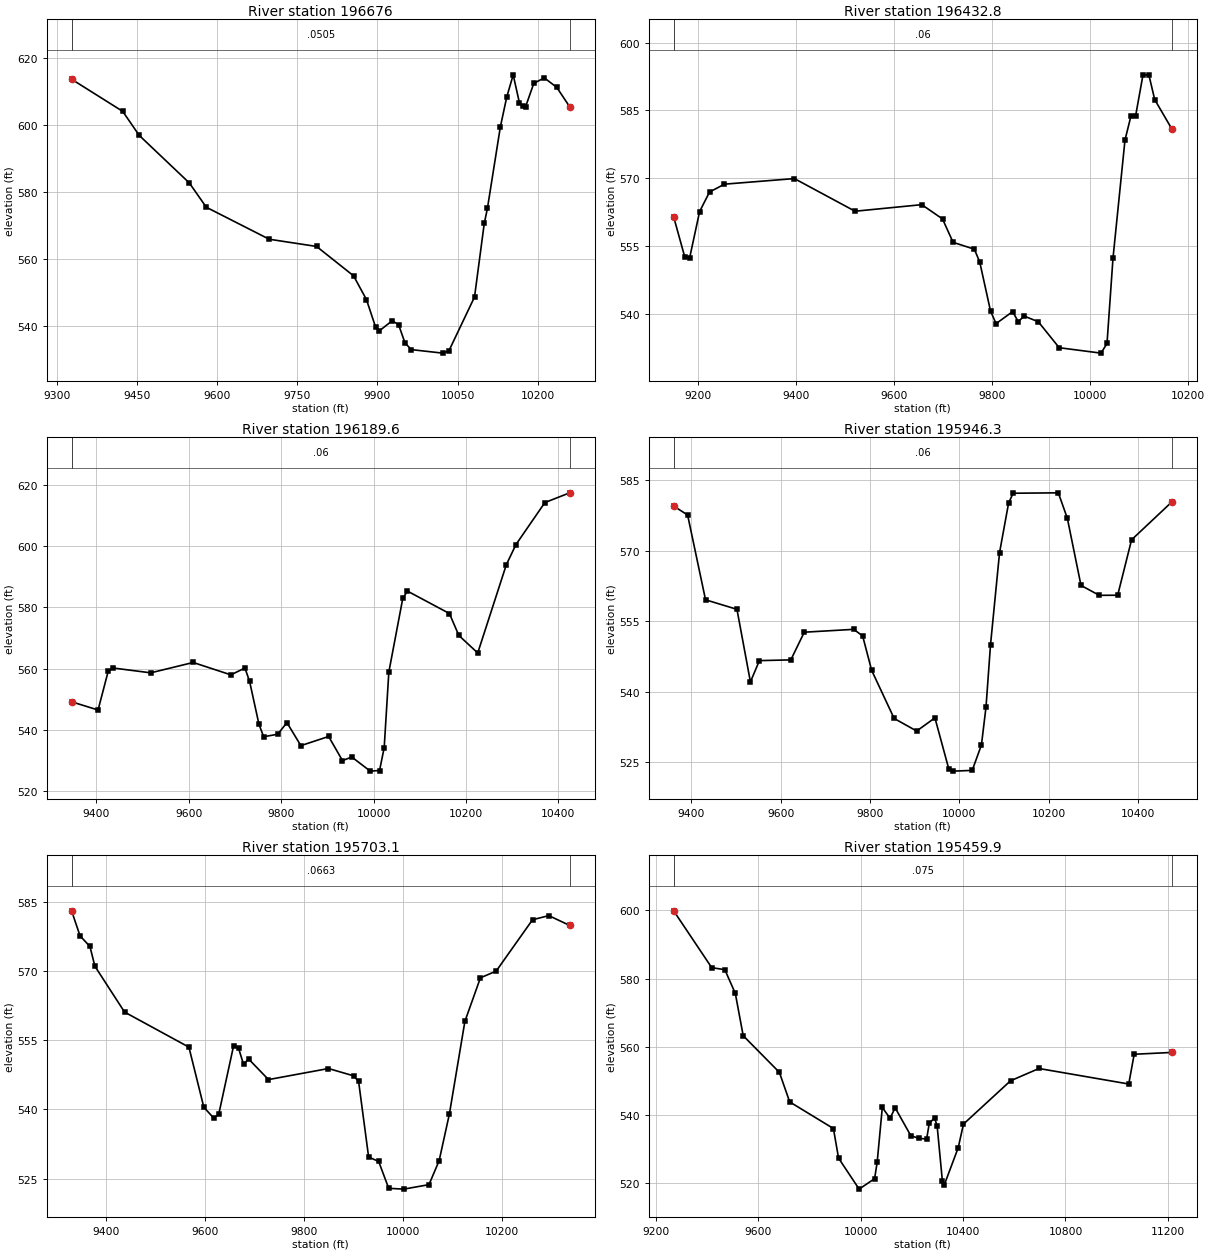
Type RM Length L Ch R = 1 ,  196676,243.215800,243.215800,243.215800
XS GIS Cut Line= 6
813011.850616187 768167.88231954813215.277060807768115.797510371
813402.678475916768043.996294871813501.311487466 767990.39979507
813755.667153418767824.296871141 813846.07141453767771.192573532
#Sta/Elev= 30
9327.853613.71099423.511604.09459454.477596.8942 9548.19582.67129579.952575.3989
9697.673565.83019786.286563.66829855.445554.87999879.508547.78049896.688539.5228
 9903.57538.41019927.633541.43569939.664540.27459951.696534.76059963.727532.7974
10022.09 531.75210033.75532.425210081.72548.543310099.94570.564610105.84575.0503
10129.96599.371710142.02608.386210154.07615.026310165.74606.631110173.06605.5524
10177.37605.532510192.62612.485810212.28614.116110235.55611.277910259.74605.4729
#Mann= 3 , 0 , 0
9327.853  0.0505       09327.853  0.0505       010259.74  0.0505       0
#XS Ineff= 2 , 0
       0                               0
Bank Sta=9327.853,10259.74
Exp/Cntr=0.3,0.1

Type RM Length L Ch R = 1 ,196432.8,243.215700,243.215700,243.215700
XS GIS Cut Line= 6
812992.752396494768365.475438565813320.762437046768299.748495698
813526.122700572768235.137116343813613.128292322768197.688458815
813700.065473944768148.950114667813924.386194855767994.475880131
#Sta/Elev= 30
9149.403561.43539171.952 552.6119182.088552.4143 9202.36562.61899222.631566.9341
9253.038568.67459395.857 569.9119519.708562.68979655.889564.14259698.254 560.989
9719.827555.81639763.242554.29499774.243551.4635  9796.3540.61739807.584 537.834
9841.435540.49339852.979538.24449864.649539.51739893.899538.24579936.468532.5101
10021.85 531.31210034.08533.443710046.31 552.31610070.78 578.43110083.02583.7686
10092.57583.825210107.49592.811110119.54 592.85410131.41587.3871 10166.3580.9148
#Mann= 3 , 0 , 0
9149.403    0.06       09149.403    0.06       0 10166.3    0.06       0
#XS Ineff= 2 , 0
       0                               0
Bank Sta=9149.403,10166.3
Exp/Cntr=0.3,0.1

Type RM Length L Ch R = 1 ,196189.6,243.215800,243.215800,243.215800
XS GIS Cut Line= 6
813236.838016331768404.946000949813658.424284607768323.565776631
813867.133364558 768311.71418184814044.802935392768289.902435824
814167.137607247 768261.62664625814296.067444673 768221.87023786
#Sta/Elev= 30
9346.209549.1082 9403.53546.41119425.628559.17559435.838560.17549517.514558.5891
9609.399 561.978    9691557.93019721.434 560.1619731.578555.77519751.867541.7113
9762.012537.65749792.286538.47519812.384542.2795 9842.53534.74469902.629537.7471
9932.641529.8369 9952.65531.02699992.706526.397610012.84526.599810022.89534.0929
10032.94  558.84 10063.1 582.95710073.15585.360810164.05578.014610184.47570.8326
10225.37565.088510287.24 593.98910308.08600.593310370.69614.349110424.37617.5374
#Mann= 3 , 0 , 0
9346.209    0.06       09346.209    0.06       010424.37    0.06       0
#XS Ineff= 2 , 0
       0                               0
Bank Sta=9346.209,10424.37
Exp/Cntr=0.3,0.1

Type RM Length L Ch R = 1 ,195946.3,243.215800,243.215800,243.215800
XS GIS Cut Line= 6
813213.885962963 768621.36295791813754.274384975768564.786502272
813900.292182207768526.042776614814104.075358748768494.017383158
814177.809350699768477.706175089814311.296655217 768439.23260647
#Sta/Elev= 30
9360.315579.45719391.522577.56779431.676 559.5329502.036557.5038 9532.19542.0708
9552.293546.59759622.653546.75639652.807552.64059763.373553.24859783.476551.8531
9803.607544.53839854.025534.30269904.453531.62699945.345 534.4299976.351523.5698
9986.822523.1014 10028.8523.257910049.47528.6557 10059.7536.713810069.82549.9883
10090.07569.580710110.31580.108610120.43582.189610221.66582.275310241.91576.8334
10272.41562.588110313.37560.481510354.56560.502610385.68572.288510475.68580.3259
#Mann= 3 , 0 , 0
9360.315    0.06       09360.315    0.06       010475.68    0.06       0
#XS Ineff= 2 , 0
       0                               0
Bank Sta=9360.315,10475.68
Exp/Cntr=0.3,0.1

Type RM Length L Ch R = 1 ,195703.1,243.215800,243.215800,243.215800
XS GIS Cut Line= 6
813227.849442393768848.590892166813458.303295255768840.786045834
813596.657641113768827.439793617813892.325359613768779.748548344
814042.883343667768741.362355128814214.339500193768678.095533169
#Sta/Elev= 30
9329.863583.10069347.014577.66669367.015575.36419377.016571.07929437.043561.1236
9567.214553.51189597.353540.46519617.446538.11019627.492538.93059657.632553.8361
9667.678553.25879677.724549.76949687.771550.95739728.115546.46989849.504548.8724
9900.241547.28659910.388546.07599930.683529.65569950.977528.71059971.272522.8715
10001.72 522.69610052.74523.667210073.32 528.878   10094538.987410125.38559.1037
10156.79568.562810188.61570.014610262.18 581.16410295.18582.059710337.31579.9281
#Mann= 3 , 0 , 0
9329.863  0.0663       09329.863  0.0663       010337.31  0.0663       0
#XS Ineff= 2 , 0
       09868.874                       0
Bank Sta=9329.863,10337.31
Exp/Cntr=0.3,0.1

Type RM Length L Ch R = 1 ,195459.9,92.663400,92.663400,92.663400
XS GIS Cut Line= 5
813269.909786165769022.165502921813568.170435727768955.140637845
814150.831717402769015.980771691 814460.88239944769090.860936388
815153.166989177768841.277138278
#Sta/Elev= 30
9268.935599.87049417.644583.21329468.891582.61999509.888575.65069540.636563.2685
9682.044552.52799722.262543.86899893.186536.05959913.295527.3819 9993.73518.3012
10054.06521.370510064.11526.137710084.22542.234310114.38539.074910134.49542.1309
10195.61533.965310226.48533.205810257.34532.971710267.63537.5445 10288.2 539.216
10298.49536.807810319.06 520.60410326.67519.598810380.79530.430610401.36537.3644
10585.16550.048410696.41553.6585 11047.2549.111311068.46557.832911215.33558.3609
#Mann= 3 , 0 , 0
9268.935   0.075       09268.935   0.075       011215.33   0.075       0
#XS Ineff= 2 , 0
       0                10175.97       0
Bank Sta=9268.935,11215.33
Exp/Cntr=0.3,0.1

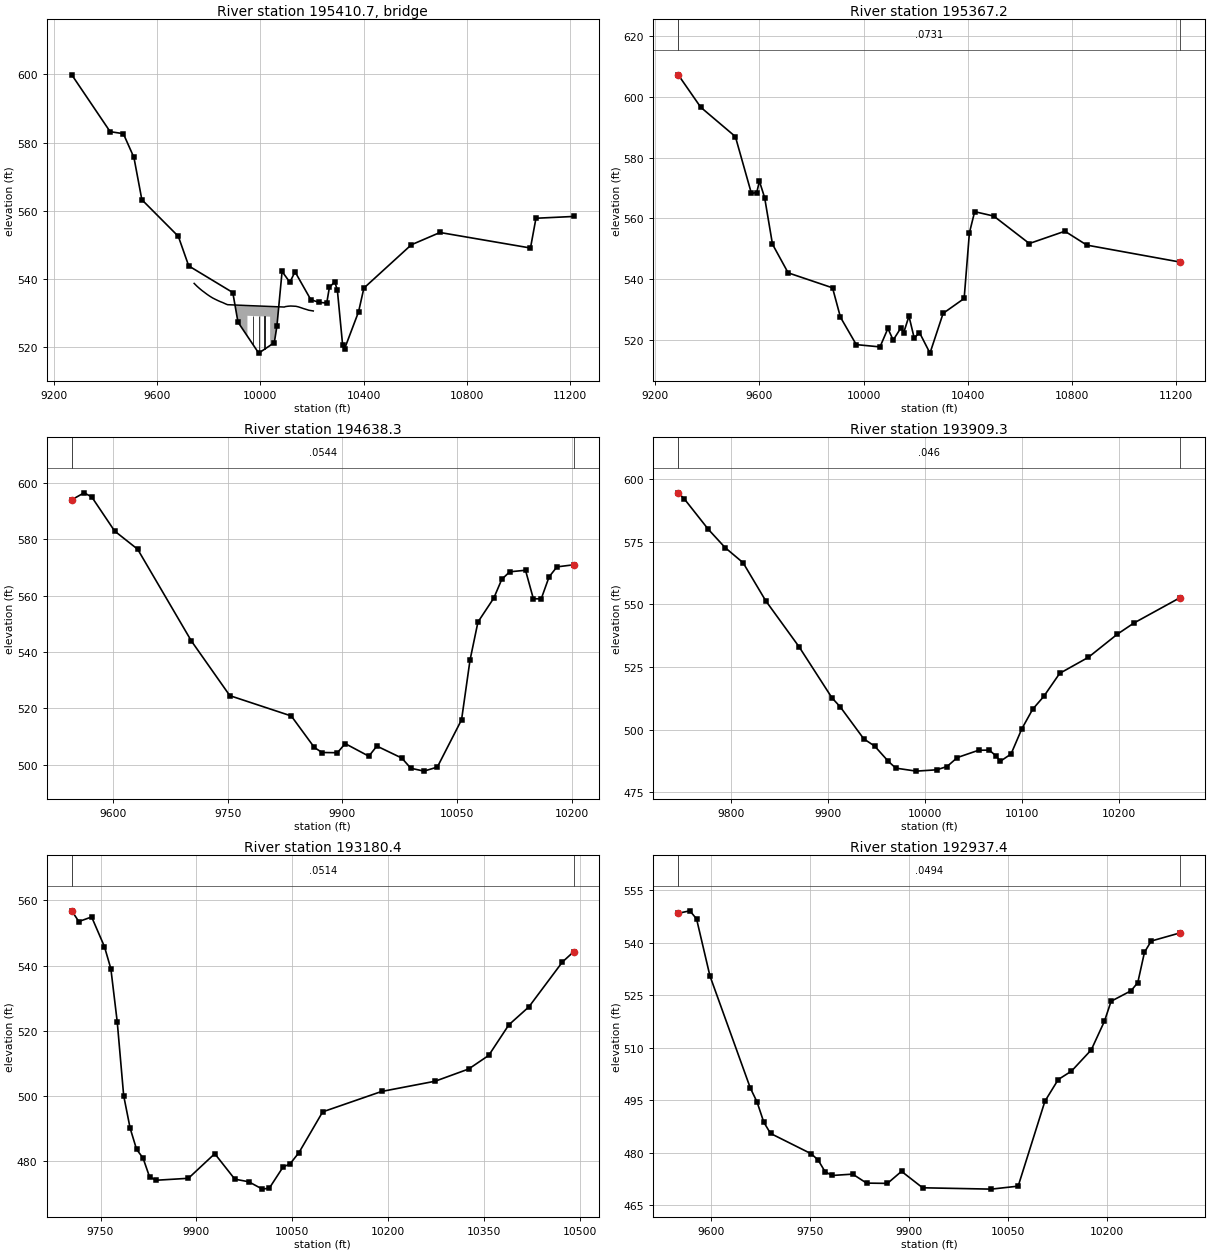
Type RM Length L Ch R = 3 ,195410.7,,,
BEGIN DESCRIPTION:
END DESCRIPTION:
Bridge Culvert--1,0,-1,-1, 0
Deck Dist Width WeirC Skew NumUp NumDn MinLoCord MaxHiCord MaxSubmerge Is_Ogee
38.331700,16.000000,2.6,0, 36, 36, , , 0.95, 0, 0,0,,
 9743.40 9744.07 9754.18 9764.28 9774.38 9783.85 9784.48 9794.59 9804.69 9814.79
 9824.89 9834.99 9845.10 9854.34 9855.20 9865.30 9872.67 9949.90 9949.9010037.90
10037.9010092.6910097.4510107.5410117.6210127.7110134.7010137.7910147.8510153.56
10157.9110167.9810178.0410188.1010198.1610205.23
  538.74  538.69  537.92  537.24  536.61  536.08  536.04  535.47  534.95  534.48
  534.09  533.72  533.38  533.11  533.08  532.73  532.50  532.25  532.25  531.98
  531.98  531.81  531.94  532.05  532.11  532.07  532.04  532.03  531.85  531.71
  531.60  531.34  531.11  530.87  530.75  530.66
 -461.26 -461.31 -462.08 -462.76 -463.39 -463.92 -463.96 -464.53 -465.05 -465.52
 -465.91 -466.28 -466.62 -466.89 -466.92 -467.27 -467.50 -467.75  529.25  528.98
 -468.02 -468.19 -468.06 -467.95 -467.89 -467.93 -467.96 -467.97 -468.15 -468.29
 -468.40 -468.66 -468.89 -469.13 -469.25 -469.34
 9743.40 9744.07 9754.18 9764.28 9774.38 9783.85 9784.48 9794.59 9804.69 9814.79
 9824.89 9834.99 9845.10 9854.34 9855.20 9865.30 9872.67 9945.70 9945.7010033.70
10033.7010092.6910097.4510107.5410117.6210127.7110134.7010137.7910147.8510153.56
10157.9110167.9810178.0410188.1010198.1610205.23
  538.74  538.69  537.92  537.24  536.61  536.08  536.04  535.47  534.95  534.48
  534.09  533.72  533.38  533.11  533.08  532.73  532.50  532.27  532.27  531.99
  531.99  531.81  531.94  532.05  532.11  532.07  532.04  532.03  531.85  531.71
  531.60  531.34  531.11  530.87  530.75  530.66
 -461.26 -461.31 -462.08 -462.76 -463.39 -463.92 -463.96 -464.53 -465.05 -465.52
 -465.91 -466.28 -466.62 -466.89 -466.92 -467.27 -467.50 -467.73  529.27  528.99
 -468.01 -468.19 -468.06 -467.95 -467.89 -467.93 -467.96 -467.97 -468.15 -468.29
 -468.40 -468.66 -468.89 -469.13 -469.25 -469.34
Pier Skew, UpSta & Num, DnSta & Num=  ,9971.65, 2 ,9967.45, 2 , 0 , 0 , 0 ,,
    1.00    1.00
 -467.81  532.19
    1.00    1.00
 -467.80  532.20
Pier Skew, UpSta & Num, DnSta & Num=  ,9993.90, 2 ,9989.70, 2 , 0 , 0 , 0 ,,
    1.00    1.00
 -467.88  532.12
    1.00    1.00
 -467.87  532.13
Pier Skew, UpSta & Num, DnSta & Num=  ,10016.15, 2 ,10011.95, 2 , 0 , 0 , 0 ,,
    1.00    1.00
 -467.95  532.05
    1.00    1.00
 -467.94  532.06
BR Coef=-1 , 0 , 0 ,, 0 ,,,0.8,0,1,0,
WSPro=,,,, 1 ,,,, 0 ,,,, 0 ,,,,-1 ,-1 ,-1 , 0 , 0 , 0 , 0 , 0
BC Design=,, 0 ,, 0 ,,,,,,

Type RM Length L Ch R = 1 ,195367.2,728.954400,728.954400,728.954400
XS GIS Cut Line= 6
 813299.83905986769111.885351747813416.070101112769092.030938998
813606.780520618769048.740843758813882.901128054769068.630887493
814432.802337706 769148.19106251815176.645834774768907.800534114
#Sta/Elev= 30
9288.017607.30649374.412596.62559507.378586.96199568.905568.26289589.413568.5323
9599.668572.2655 9619.76566.85299649.838551.51999709.994542.08859880.455537.1507
9910.827527.46899971.573518.446610062.69517.694810093.06523.762510113.31519.9435
10143.63524.055710153.72522.3972 10173.9527.823110194.08 520.58710214.25522.4179
10254.61 515.64410305.06528.750310385.77533.643710405.95555.261610426.12562.2328
10499.36560.789110635.98551.7428 10772.6555.796210856.67551.221711215.72545.6219
#Mann= 3 , 0 , 0
9288.017  0.0731       09288.017  0.0731       011215.72  0.0731       0
#XS Ineff= 2 , 0
       0                10194.01       0
Bank Sta=9288.017,11215.72
Exp/Cntr=0.3,0.1

Type RM Length L Ch R = 1 ,194638.3,728.954400,728.954400,728.954400
XS GIS Cut Line= 6
813958.939884514769488.174641445814224.724816322769470.276437476
814295.154638499769473.229195178814364.028236359769490.024539903
814457.302561343 769536.11682342814596.533164752769571.642360691
#Sta/Elev= 30
9546.212594.01619562.274596.47779572.275595.0311 9602.28582.89669632.326576.4468
9702.558543.86469752.824524.44999833.143517.23769863.209  506.089873.245504.2638
9893.451504.18489903.622507.42089934.538502.94639944.999 506.5479977.606502.2917
9989.342498.679410006.63497.648810024.06499.087610055.73515.884210066.77537.0522
10077.15550.593710097.92559.1261 10108.3565.766610118.68568.432910139.32 568.979
10149.59558.856910159.85558.820610170.12566.629110180.39570.1848 10202.5 570.929
#Mann= 3 , 0 , 0
9546.212  0.0544       09546.212  0.0544       0 10202.5  0.0544       0
#XS Ineff= 2 , 0
       0                               0
Bank Sta=9546.212,10202.5
Exp/Cntr=0.3,0.1

Type RM Length L Ch R = 1 ,193909.3,728.954400,728.954400,728.954400
XS GIS Cut Line= 6
813719.402209103 769659.75199835813780.467962742769754.897577628
813808.321911514769809.082720622813850.863236666769922.740934372
813883.233168244769988.545035839813960.333535886 770114.83051715
#Sta/Elev= 30
9745.976594.61799752.411592.09959776.932580.03759794.203 572.7359812.714566.6941
9835.978551.51919870.482533.03179904.214512.70559912.782509.06539936.998496.2974
9948.246493.38949962.381  487.279969.958484.59919990.997483.4004 10012.1483.9296
 10022.7485.2334 10033.3488.823910055.16 491.73810066.31491.795810073.53489.3207
10077.45487.3092 10088.6490.233210099.74500.327710110.89508.141110122.26513.2415
10138.71522.474910168.23528.8863 10198.2538.1708 10215.1542.578810262.88552.7696
#Mann= 3 , 0 , 0
9745.976   0.046       09745.976   0.046       010262.88   0.046       0
#XS Ineff= 2 , 0
       0                               0
Bank Sta=9745.976,10262.88
Exp/Cntr=0.3,0.1

Type RM Length L Ch R = 1 ,193180.4,242.984700,242.984700,242.984700
XS GIS Cut Line= 6
813024.002006948770256.580481902 813191.26716122770238.438957468
813268.529037237770218.677383319813368.391961545770180.144116983
813424.041804135770173.449862957813781.973300325770279.947459546
#Sta/Elev= 30
9705.035556.81499716.059553.52169736.107554.92899756.154545.80449766.178539.0184
9776.202522.58939786.226500.01769796.291490.04859806.403483.51859816.516480.8535
9826.628475.10659836.741474.02559887.497474.62919928.701482.18719960.088474.3627
9981.842473.564410003.17   471.310014.05471.598210035.68478.132510046.21 478.992
10060.32482.4966 10097.5495.040310189.55501.301210273.42 504.45610325.84508.2103
10357.29512.397910388.74 521.78710420.19527.327510472.61541.110710490.41544.2942
#Mann= 3 , 0 , 0
9705.035  0.0514       09705.035  0.0514       010490.41  0.0514       0
#XS Ineff= 2 , 0
       0                               0
Bank Sta=9705.035,10490.41
Exp/Cntr=0.3,0.1

Type RM Length L Ch R = 1 ,192937.4,242.984800,242.984800,242.984800
XS GIS Cut Line= 6
813017.532351353770512.759017741813238.106540531770465.516898662
813436.137836099 770395.80843845813574.282470256770375.793960407
813632.197253883770373.848139167813757.594643742770396.905148163
#Sta/Elev= 30
9550.401548.47449568.076549.17169578.195546.85289598.432 530.575 9659.67498.5037
9669.883494.50569680.096  488.729690.309485.50099752.246479.65619762.593477.8636
9772.941474.58739783.404473.46339814.948473.85229835.977471.28649867.675471.2032
9888.993474.64919920.969469.948610025.16469.562810065.87 470.41510106.43494.7084
10126.63500.912210146.68503.316310176.69509.393510196.74517.613310206.78523.3034
10237.07526.305610247.24528.6432 10257.4537.324510267.57540.523210311.74542.8793
#Mann= 3 , 0 , 0
9550.401  0.0494       09550.401  0.0494       010311.74  0.0494       0
#XS Ineff= 2 , 0
       0                               0
Bank Sta=9550.401,10311.74
Exp/Cntr=0.3,0.1

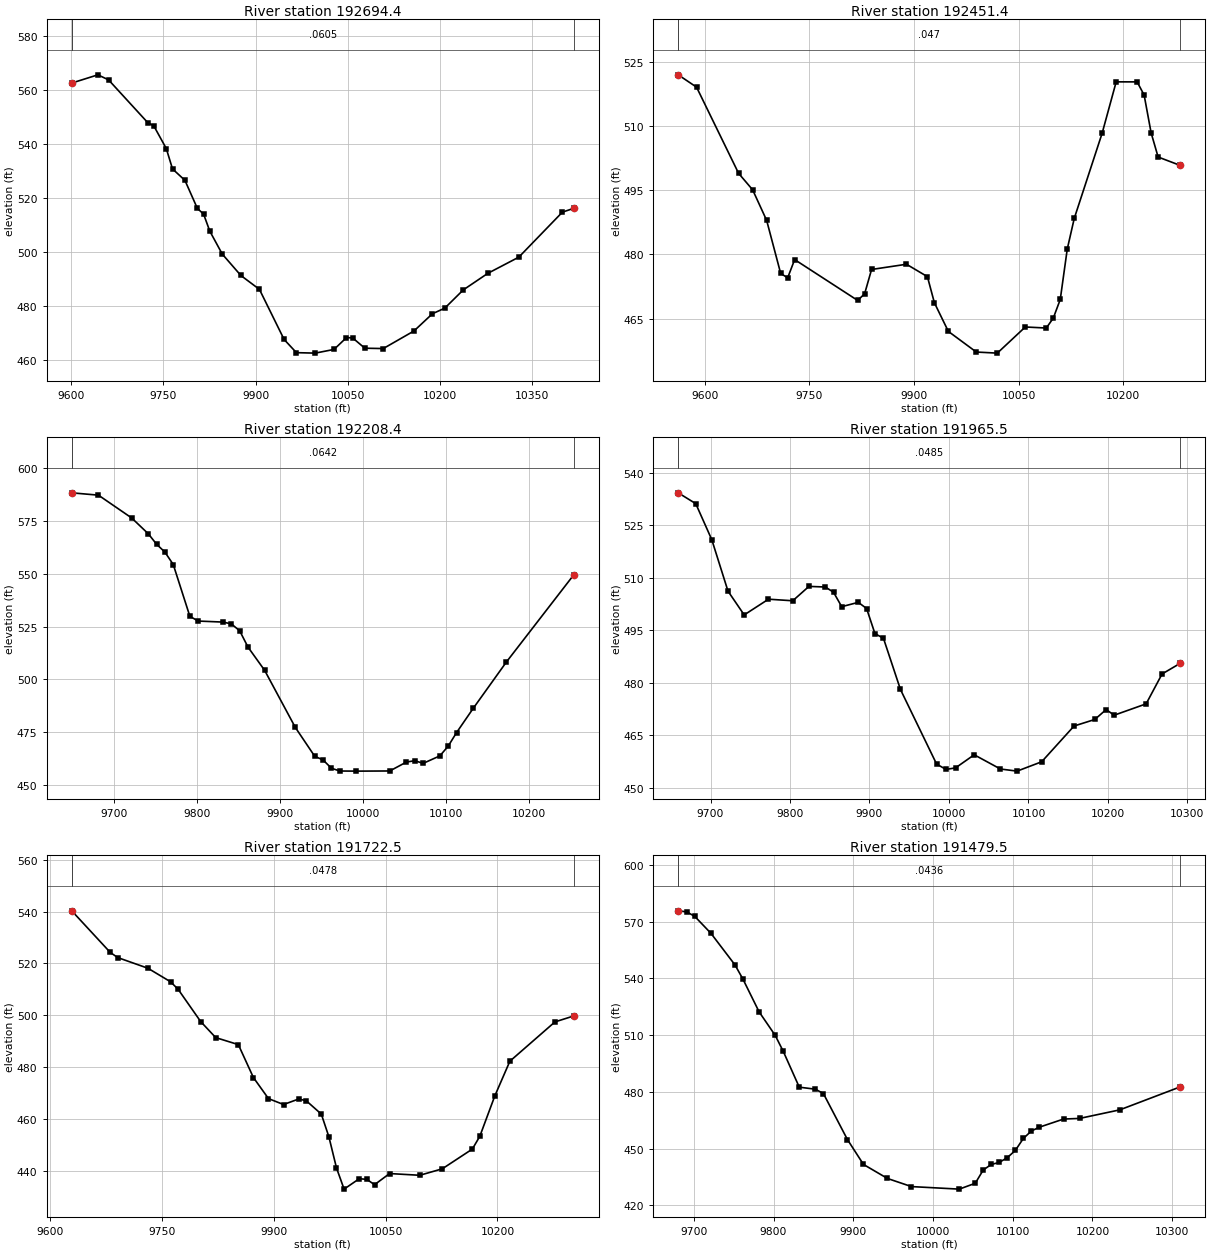
Type RM Length L Ch R = 1 ,192694.4,242.984800,242.984800,242.984800
XS GIS Cut Line= 6
813073.005014479770674.016759351 813341.07746926770633.151519835
813423.338766962770626.226771116813511.727649003770640.307283521
813734.404015273 770645.93231301813883.385753423770666.676605362
#Sta/Elev= 30
9601.043562.45649643.523565.49229660.876563.63289724.447 547.8839734.563546.6124
9754.794538.26469764.909530.74789785.141526.51419805.372516.15239815.487514.0525
9825.603507.75069845.834499.29789876.159491.3798 9906.34486.24619946.463467.7514
9966.503462.88089997.038462.707210027.69464.0764 10047.8468.4139 10057.8468.3585
 10077.8464.521810107.81464.393910157.81 470.90110187.82477.265310207.84479.3113
10237.89486.0491   10278492.192410328.34498.163810399.15514.771610417.81516.1986
#Mann= 3 , 0 , 0
9601.043  0.0605       09601.043  0.0605       010417.81  0.0605       0
#XS Ineff= 2 , 0
       0                               0
Bank Sta=9601.043,10417.81
Exp/Cntr=0.3,0.1

Type RM Length L Ch R = 1 ,192451.4,242.984800,242.984800,242.984800
XS GIS Cut Line= 6
813038.838229448770890.745160684813187.208876729770876.848961547
813306.808605015770868.854464561813387.777761757770866.448971078
813444.173261315770867.911194339 813756.75325095770888.251154054
#Sta/Elev= 30
9562.247521.90579588.523 519.0239648.786498.89389668.873 495.0579688.961487.9129
9709.048475.53379719.075474.49649729.098478.75999819.298469.23349829.321470.7449
9839.328476.4516 9889.35477.66959919.363474.77429929.366468.67389949.373461.9891
9989.441457.168510019.54456.915410059.66463.021710089.72462.776310099.74465.0865
10109.76469.453910119.77481.205410129.79488.367210169.86508.317110189.89520.2626
10219.94520.260910229.96517.181610239.97508.361110249.99502.713510281.81500.7422
#Mann= 3 , 0 , 0
9562.247   0.047       09562.247   0.047       010281.81   0.047       0
#XS Ineff= 2 , 0
       0                               0
Bank Sta=9562.247,10281.81
Exp/Cntr=0.3,0.1

Type RM Length L Ch R = 1 ,192208.4,242.984800,242.984800,242.984800
XS GIS Cut Line= 6
813122.921567112771104.564422593813232.689692318 771099.37474525
813302.773871362771099.200433031813362.707854241771101.832927883
813612.065309107771124.869357526813726.195399461771127.925383622
#Sta/Elev= 30
9649.224 588.2239681.353587.11769721.392576.32749741.412568.84089751.422563.8901
9761.429560.17099771.429554.32929791.429529.83739801.429527.58669831.432527.1026
9841.441526.23899851.451522.97279861.461 515.258 9881.48 504.2899918.457477.2693
9941.796463.64899951.855461.89699961.914457.99489971.974456.68059992.082456.6209
 10032.2456.695410052.31460.923410062.36461.540310072.42460.299810092.51463.8364
10102.53468.430510112.56474.814310132.61486.272210172.63508.223110253.86549.4934
#Mann= 3 , 0 , 0
9649.224  0.0642       09649.224  0.0642       010253.86  0.0642       0
#XS Ineff= 2 , 0
       0                               0
Bank Sta=9649.224,10253.86
Exp/Cntr=0.3,0.1

Type RM Length L Ch R = 1 ,191965.5,242.984800,242.984800,242.984800
XS GIS Cut Line= 6
813153.191134393771433.192155182813394.189059496771382.210388169
813449.040843725771359.148309067813513.564964086771319.152224422
813565.333495378771300.721812531 813757.89266687771274.920990994
#Sta/Elev= 30
9659.376534.25939681.422531.1628 9701.64520.83949721.991506.16079742.358499.3704
9772.907503.86199803.457503.41259823.824507.52099844.423507.34189854.732505.8585
 9865.04501.72539885.933502.96189896.386501.19019906.859494.02259917.561492.6975
9938.963478.0574  9984.4 456.7619996.217455.215210008.29455.659210031.75459.4011
10064.73455.334310085.71454.728810116.65457.402210157.38467.6205 10183.5469.4925
10197.77472.329910207.83470.708810248.05473.953610268.11482.494110291.06 485.556
#Mann= 3 , 0 , 0
9659.376  0.0485       09659.376  0.0485       010291.06  0.0485       0
#XS Ineff= 2 , 0
       0                               0
Bank Sta=9659.376,10291.06
Exp/Cntr=0.3,0.1

Type RM Length L Ch R = 1 ,191722.5,242.984800,242.984800,242.984800
XS GIS Cut Line= 6
813163.986073673771630.260534301813481.268335938771585.026195303
813529.444667578771575.947496057813564.214800477771568.842172533
813625.625518948771559.881114841813830.204743363771536.729262481
#Sta/Elev= 30
9629.485540.32389681.015524.28039691.116522.27439731.521518.16769761.824512.9471
9771.925510.07859802.228497.59739822.431491.38519852.734 488.6889872.936475.9737
9893.138467.84079913.341465.55779933.543467.67919943.644467.04669963.949461.8658
9974.125 453.0889984.301441.08319994.477 432.90110014.88436.929110025.09 436.658
10035.28434.605810055.49438.912110095.92 438.24610126.11440.742310166.37448.3582
10176.43453.305710196.56468.911410216.69482.276210277.07497.443310302.44499.7606
#Mann= 3 , 0 , 0
9629.485  0.0478       09629.485  0.0478       010302.44  0.0478       0
#XS Ineff= 2 , 0
       0                               0
Bank Sta=9629.485,10302.44
Exp/Cntr=0.3,0.1

Type RM Length L Ch R = 1 ,191479.5,242.984800,242.984800,242.984800
XS GIS Cut Line= 6
813234.357743382771847.317426816813436.922785997771821.890485644
813506.477477312771815.700513601813586.516311109771813.861831665
813639.730079263771809.765399665813860.342368369771781.964661199
#Sta/Elev= 30
9680.444575.6805 9691.17575.13239701.249572.70929721.406563.82829751.641547.1002
 9761.72539.50139781.876522.30839802.033509.89749812.112501.49439832.269482.5043
9852.426481.43289862.504 479.1549892.708454.79969912.787 441.6799942.906434.2613
9972.958429.976710032.97428.631410053.03431.733710063.06438.765910073.09 441.661
10083.12442.746110093.17445.255910103.25449.063710113.33455.407710123.41459.3549
10133.49461.374510163.73 465.65510183.88465.989410234.28470.514110310.22 482.678
#Mann= 3 , 0 , 0
9680.444  0.0436       09680.444  0.0436       010310.22  0.0436       0
#XS Ineff= 2 , 0
       0                               0
Bank Sta=9680.444,10310.22
Exp/Cntr=0.3,0.1