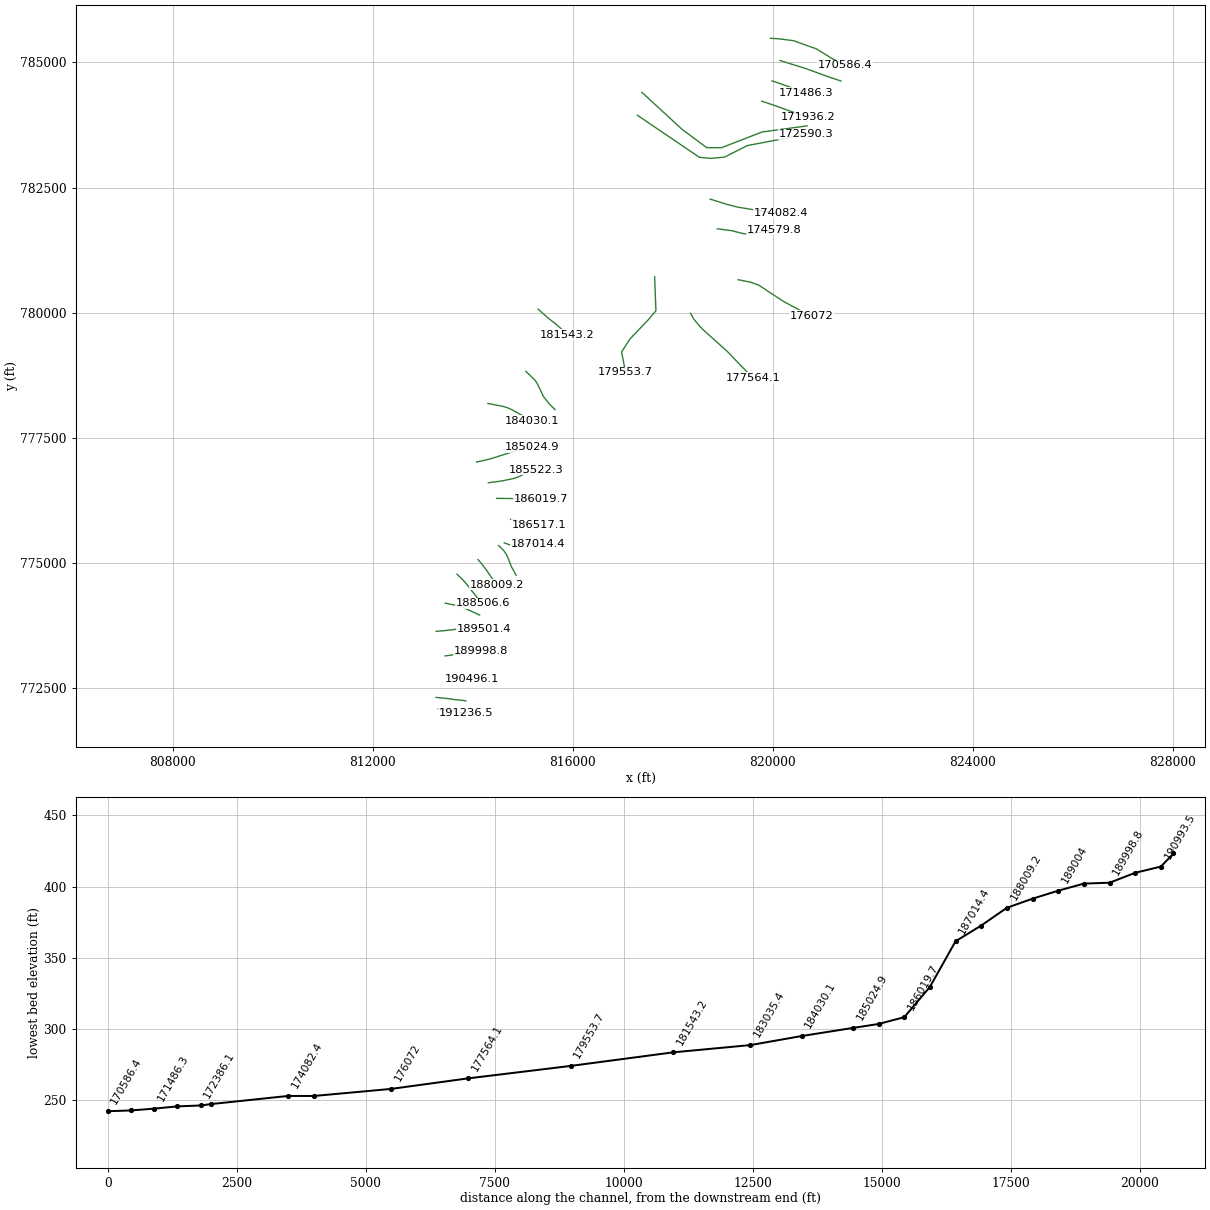
HEC-RAS study 17203_ras.prj: 17203

--- 17203_ras.g01 (geometry) --- (continued)

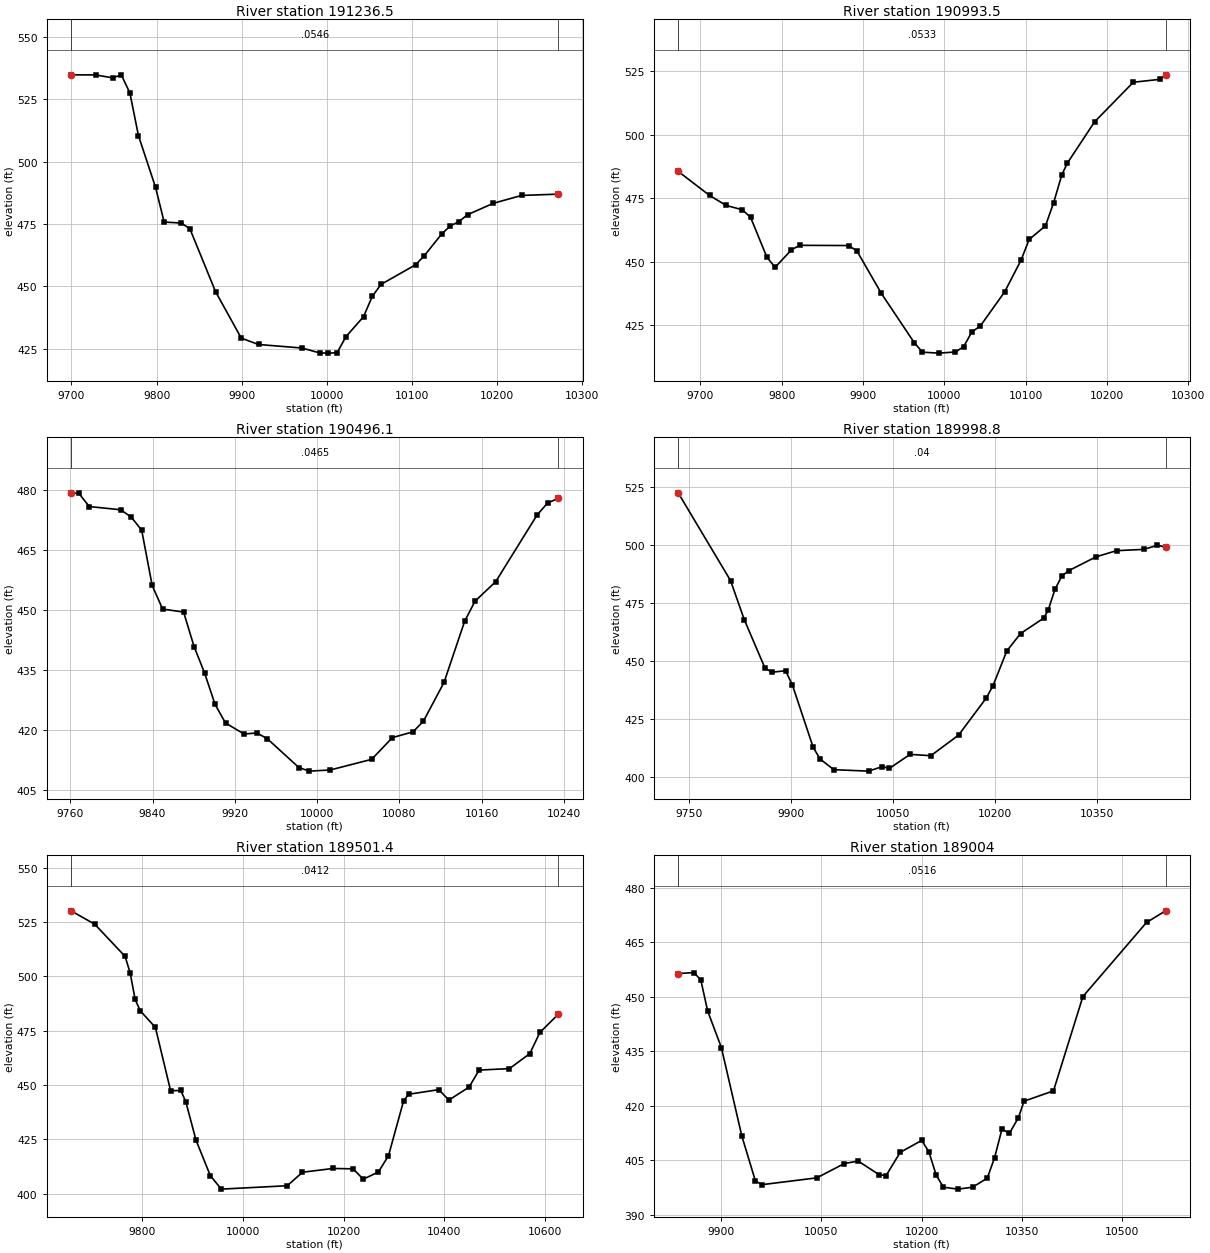
Type RM Length L Ch R = 1 ,191236.5,242.984700,242.984700,242.984700
XS GIS Cut Line= 6
813306.290672064772089.807879835813489.207501918772070.302164659
813555.026037216772060.418777272813661.647091091772032.761244819
813785.734194726772010.819861412813870.580304797771999.057185207
#Sta/Elev= 30
9699.479534.80139728.351534.76329748.465533.58159758.521534.76129768.578527.5609
9778.635510.42719798.748489.67549808.805475.79819828.918475.40089838.975473.1655
9869.145447.93979899.402429.27479919.627426.72799970.607425.31719991.251423.3774
 10001.6423.269310011.94 423.44610022.27429.850310042.94437.867710053.27446.0533
10063.55450.822410104.17458.699810114.32462.314510134.63470.975810144.79474.2343
10154.94475.9723 10165.1478.751610195.51483.330710228.53486.464610271.81486.9867
#Mann= 3 , 0 , 0
9699.479  0.0546       09699.479  0.0546       010271.81  0.0546       0
#XS Ineff= 2 , 0
       0                               0
Bank Sta=9699.479,10271.81
Exp/Cntr=0.3,0.1

Type RM Length L Ch R = 1 ,190993.5,497.385600,497.385600,497.385600
XS GIS Cut Line= 6
813266.562958241772319.006229207813537.612835824772290.065505445
 813636.34336561 772273.65198034813745.290407687772264.699703351
813795.521347672772259.038206756813861.471177576772249.085283091
#Sta/Elev= 30
9672.873485.5627 9711.58476.07919731.721472.17849751.843470.44669761.896467.4724
9782.001451.75629792.054447.80679812.159454.68649822.212456.46449882.527456.3768
 9892.58454.28459922.738437.51699963.091418.17979973.225414.40659993.495414.0404
10013.79414.487610023.92416.598510034.06422.4458 10044.2424.631210074.31438.1538
10094.38450.589410104.41458.767310124.48464.138410134.51473.227810144.55484.1817
10151.21488.722410184.77505.029910232.48520.640610265.57521.793910272.12523.5609
#Mann= 3 , 0 , 0
9672.873  0.0533       09672.873  0.0533       010272.12  0.0533       0
#XS Ineff= 2 , 0
       0                               0
Bank Sta=9672.873,10272.12
Exp/Cntr=0.3,0.1

Type RM Length L Ch R = 1 ,190496.1,497.385500,497.385500,497.385500
XS GIS Cut Line= 6
813507.499392301772756.703342959 813523.39740169772753.959966615
813743.354816288772711.150292814813761.950182617772707.771109089
813915.516472429772692.788687125 813975.48282673772685.039766232
#Sta/Elev= 30
9760.777479.26769768.389479.13019778.543475.83229809.102475.02979819.288473.1932
9829.474469.93489839.661456.10289849.847450.1972 9870.22  449.459880.406440.8206
9890.593 434.2349900.779 426.3769910.965421.71189929.004418.94329941.524419.2173
9951.711417.7507 9982.27410.57069992.456409.669510012.84409.955710053.11 412.622
 10073.2418.0463 10093.3419.497710103.34 422.13610123.44431.864210143.53447.1761
10153.58452.172210173.68457.052910214.01473.764410224.09476.715210234.66477.9132
#Mann= 3 , 0 , 0
9760.777  0.0465       09760.777  0.0465       010234.66  0.0465       0
#XS Ineff= 2 , 0
       0                               0
Bank Sta=9760.777,10234.66
Exp/Cntr=0.3,0.1

Type RM Length L Ch R = 1 ,189998.8,497.385600,497.385600,497.385600
XS GIS Cut Line= 6
813448.669284463773146.438958883813572.418708712 773162.74091585
813863.237426668773216.587313384813980.405856252773235.320131391
814069.998058975773245.818697155814156.908936421773251.592552874
#Sta/Elev= 30
9734.266522.41669811.233484.6885 9831.42467.89069861.714447.16179871.857 445.242
9892.144445.88819902.288439.70979932.719412.96749942.862407.92719963.189403.3283
10014.13402.706610034.49404.657910044.67403.845610075.22409.915510105.76409.3424
10146.49 418.18910187.04 434.07210197.17439.447910217.42454.400910237.67461.8811
 10271.5468.486210278.15471.823710288.22 480.86110298.29486.583310308.36488.9158
10348.63494.882110378.77497.536510418.86498.0894 10438.9499.857410450.84499.0712
#Mann= 3 , 0 , 0
9734.266    0.04       09734.266    0.04       010450.84    0.04       0
#XS Ineff= 2 , 0
       0                               0
Bank Sta=9734.266,10450.84
Exp/Cntr=0.3,0.1

Type RM Length L Ch R = 1 ,189501.4,497.385500,497.385500,497.385500
XS GIS Cut Line= 6
813268.092976643773636.520852601813429.819848121 773650.85519639
813879.801620199773702.594693284814006.286752291773704.511771682
814089.981022487773699.944559767814231.340767309773682.023721604
#Sta/Elev= 30
9658.241530.13139705.268523.97939765.528509.19919775.577501.69739785.626489.3417
9795.675484.17539825.836476.46459856.068447.34349876.223447.4666  9886.3 442.254
9906.455424.62889935.002408.25319956.842402.073410087.82403.639510118.05 409.841
10178.49411.578810218.66411.406810238.72406.638510268.81409.959410288.84417.3901
10318.86 442.64510328.87445.723810388.87447.851610408.88443.046110448.94449.0052
10468.97456.846410529.28457.540110569.54464.404410589.69 474.147 10626.5482.6123
#Mann= 3 , 0 , 0
9658.241  0.0412       09658.241  0.0412       0 10626.5  0.0412       0
#XS Ineff= 2 , 0
       0                               0
Bank Sta=9658.241,10626.5
Exp/Cntr=0.3,0.1

Type RM Length L Ch R = 1 ,  189004,497.385600,497.385600,497.385600
XS GIS Cut Line= 6
813452.028897927774201.443448392813522.579584277774185.132070499
813706.935679015774146.569590699813777.245251749774124.459187917
813850.106883007774095.096186584814137.384545419773963.127158761
#Sta/Elev= 30
9835.779456.39829859.356456.6633 9869.62454.64869879.884446.11149900.411436.0482
9931.056411.68999951.453399.28899961.651398.350310043.26400.2171 10084.3404.1456
10105.01404.841910136.46401.069510146.94400.8542 10167.9407.213410200.18410.5172
10210.96407.334910221.75401.001610232.53397.6414 10254.2 397.11310276.21397.6339
10298.22 400.13510309.22405.772810320.23413.660910331.23412.431110344.87416.7676
10353.24421.300310397.26424.128510441.28450.070410536.51470.450210564.95473.6465
#Mann= 3 , 0 , 0
9835.779  0.0516       09835.779  0.0516       010564.95  0.0516       0
#XS Ineff= 2 , 0
       0                               0
Bank Sta=9835.779,10564.95
Exp/Cntr=0.3,0.1

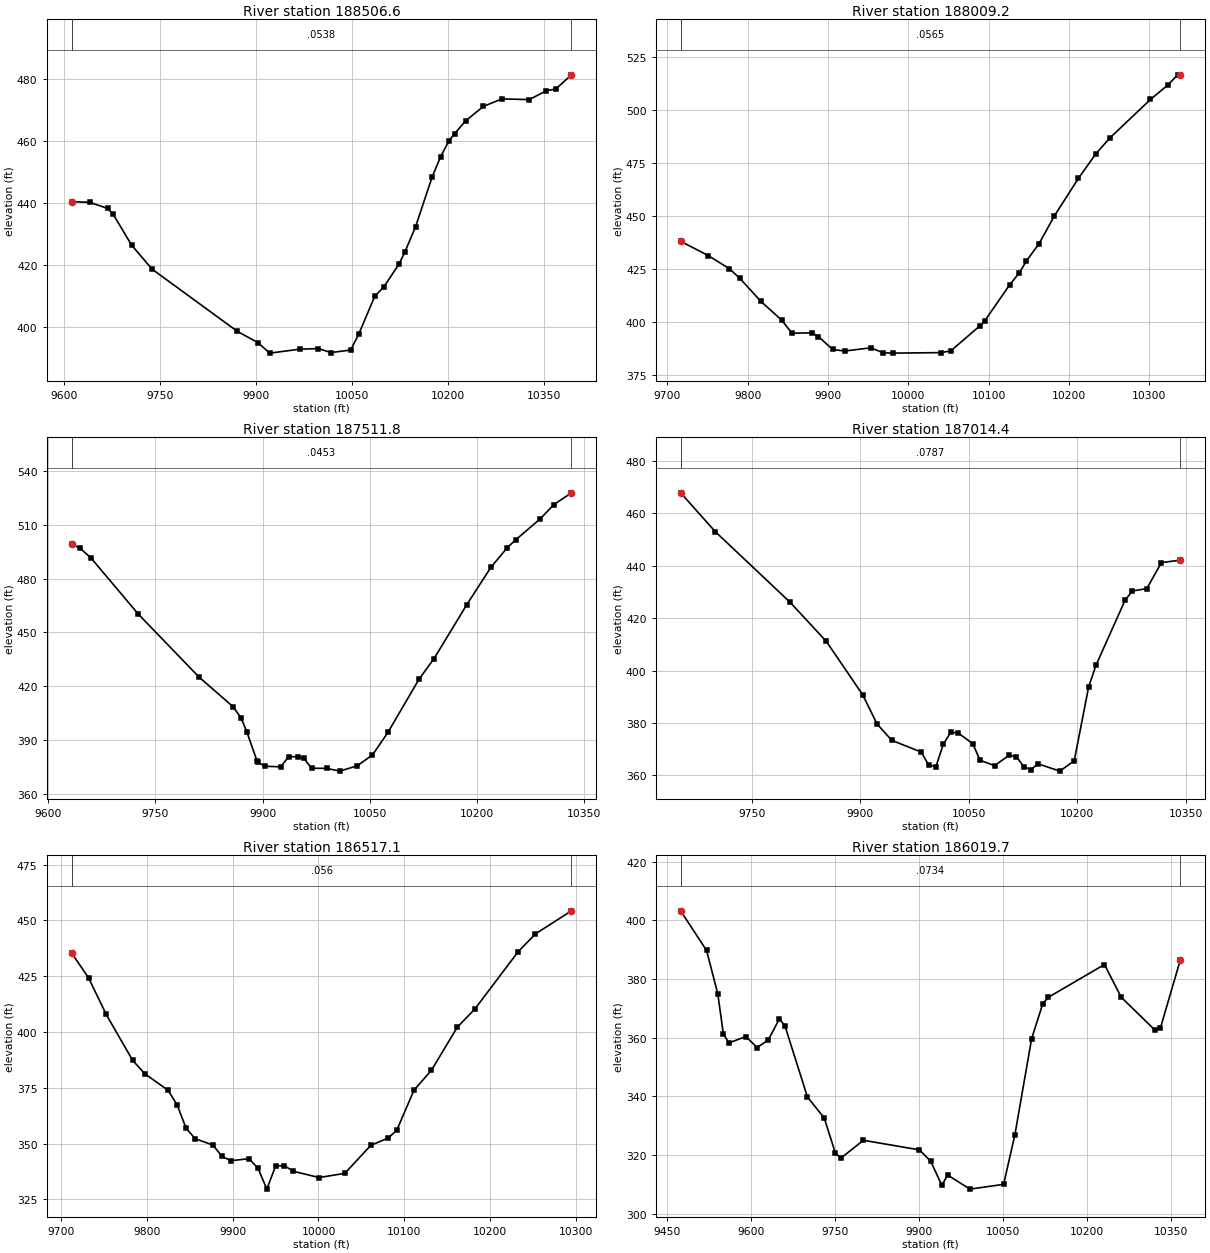
Type RM Length L Ch R = 1 ,188506.6,497.385500,497.385500,497.385500
XS GIS Cut Line= 6
813683.862400126774779.087094085813777.679069889774690.209269634
813829.764019317774635.113389629813873.435052283774584.770929361
814085.546930878774315.696287049814203.341226789774198.877970015
#Sta/Elev= 30
 9611.88440.47499640.085440.27499667.893438.29659676.669436.42069705.455426.4402
9737.412418.66129870.727398.51789902.452394.92449921.298 391.4989967.655392.7632
9997.273392.971710016.71391.680710047.58392.498210060.14397.651110085.26409.9052
10099.35412.908510122.94420.273610132.16424.182810148.85432.347410174.97448.5973
10188.03455.025510201.09460.2018 10209.9462.505410227.25466.654410254.73471.2875
10283.83473.7287 10326.4473.483810353.16476.371310367.74476.8965 10392.3481.5031
#Mann= 3 , 0 , 0
 9611.88  0.0538       0 9611.88  0.0538       0 10392.3  0.0538       0
#XS Ineff= 2 , 0
       0                               0
Bank Sta=9611.88,10392.3
Exp/Cntr=0.3,0.1

Type RM Length L Ch R = 1 ,188009.2,497.385600,497.385600,497.385600
XS GIS Cut Line= 6
814105.204425752775070.807734966 814179.22125569774984.720870569
814253.020255417774890.272054374814322.047640204774788.680220172
814423.613180935774644.942800611814477.100528763774572.309590453
#Sta/Elev= 30
9716.563 437.9189750.884431.20899777.363424.9542 9790.31420.43799816.595409.5227
 9842.44400.70429855.131394.53639880.512394.70899888.214392.92379905.893386.8699
9920.698386.11479953.447 387.6369968.531385.31849980.687385.128510041.09385.3691
10053.14 386.23610089.54398.107610095.24400.348410126.28 417.34310138.52423.1517
10147.22428.637610163.01436.848910181.88449.828310211.99467.669510233.87479.3421
10251.13486.712210301.72504.908610323.23511.678610335.65516.524210338.99516.4655
#Mann= 3 , 0 , 0
9716.563  0.0565       09716.563  0.0565       010338.99  0.0565       0
#XS Ineff= 2 , 0
       0                               0
Bank Sta=9716.563,10338.99
Exp/Cntr=0.3,0.1

Type RM Length L Ch R = 1 ,187511.8,497.385500,497.385500,497.385500
XS GIS Cut Line= 6
 814516.36383751775352.136139736814617.506563008775254.583993509
814666.137404978775184.481617019814701.484714389775112.136751547
814771.678798974774932.704320043814868.531469783774758.265001752
#Sta/Elev= 30
9632.971 499.139 9644.21497.10819659.961491.53139726.421460.10959810.954425.1861
9858.508408.66759869.878402.41289877.902394.68459892.563378.02839893.911377.5023
9903.589375.39299925.555375.04199936.539380.7664 9949.84380.62039957.949379.7148
9968.608 374.2819989.925374.183510008.05372.658310032.44375.627110053.78381.6611
10075.54394.328410119.06423.999710139.85435.363510185.78465.504510219.32  486.22
10242.43497.271410254.01501.554610288.74 513.42710307.65521.318210332.14527.8288
#Mann= 3 , 0 , 0
9632.971  0.0453       09632.971  0.0453       010332.14  0.0453       0
#XS Ineff= 2 , 0
       0                               0
Bank Sta=9632.971,10332.14
Exp/Cntr=0.3,0.1

Type RM Length L Ch R = 1 ,187014.4,497.385500,497.385500,497.385500
XS GIS Cut Line= 6
814630.258053929775402.586793065814729.036399603775368.603886858
814820.163866252775355.467645943815128.450113267775395.741207734
815191.575482905775394.136467502815310.877939882775378.605625632
#Sta/Elev= 30
9651.158467.79289699.264452.94519802.472426.08839852.774411.13069902.955390.8211
9923.081379.57759943.405373.35729984.202368.88229994.401363.942210004.57363.3622
10014.76371.868810024.95376.403910035.15376.188710055.41372.129210065.52365.7688
10085.74363.712310105.87367.6707 10115.9367.156410125.92363.353210135.94362.1962
10145.96364.395210175.99 361.61210195.99365.5801   10216  393.8610226.02401.9703
10266.27426.790510276.33430.323410296.45431.276810316.64 441.17910342.95442.1015
#Mann= 3 , 0 , 0
9651.158  0.0787       09651.158  0.0787       010342.95  0.0787       0
#XS Ineff= 2 , 0
       0                               0
Bank Sta=9651.158,10342.95
Exp/Cntr=0.3,0.1

Type RM Length L Ch R = 1 ,186517.1,497.385600,497.385600,497.385600
XS GIS Cut Line= 6
 814755.83593753 775874.58851105 814849.66007185775852.450708464
815000.017264932775808.511020705 815062.23135069775806.435423404
815118.067424297775800.078859225815326.484862188775770.264896243
#Sta/Elev= 30
9712.455435.40749732.145424.28759752.694407.89069783.518387.29579797.754381.2841
 9824.89373.84689835.344367.33869845.797356.8538 9856.25352.21539877.156349.3061
 9887.61344.22049898.063342.32969918.969343.22439929.422339.04819939.784329.5859
9950.079339.96849960.375340.07099970.555337.606610000.69334.767210030.72336.6674
10060.91 349.20510081.04352.458410091.13355.954210111.33373.969610131.54382.8539
10161.84402.247810182.05410.270110232.55435.990110252.76443.997310294.67454.3243
#Mann= 3 , 0 , 0
9712.455   0.056       09712.455   0.056       010294.67   0.056       0
#XS Ineff= 2 , 0
       0                               0
Bank Sta=9712.455,10294.67
Exp/Cntr=0.3,0.1

Type RM Length L Ch R = 1 ,186019.7,497.385500,497.385500,497.385500
XS GIS Cut Line= 6
814478.623089343776292.918509722814759.788363516776289.708979502
814970.010822892776280.957911417815064.651755393776285.919333026
815291.259317338776283.991842404815370.639808631776281.682641882
#Sta/Elev= 30
 9473.93403.2941 9520.31389.77139540.311 374.9169550.312361.21249560.313358.2315
9590.315360.41149610.316356.66329630.317359.19179650.319366.46429660.319363.9826
9700.322339.79149730.324 332.6299750.325320.60079760.328318.97269800.346325.0112
9900.435321.73769920.461317.84759940.486309.59979950.499313.1765 9990.55308.3502
10050.64309.982910070.65 326.79210100.65359.673710120.65371.670210130.65373.8085
10230.66384.978110260.66373.791810320.67362.645610330.68363.367510366.33386.6497
#Mann= 3 , 0 , 0
 9473.93  0.0734       0 9473.93  0.0734       010366.33  0.0734       0
#XS Ineff= 2 , 0
       0                               0
Bank Sta=9473.93,10366.33
Exp/Cntr=0.3,0.1

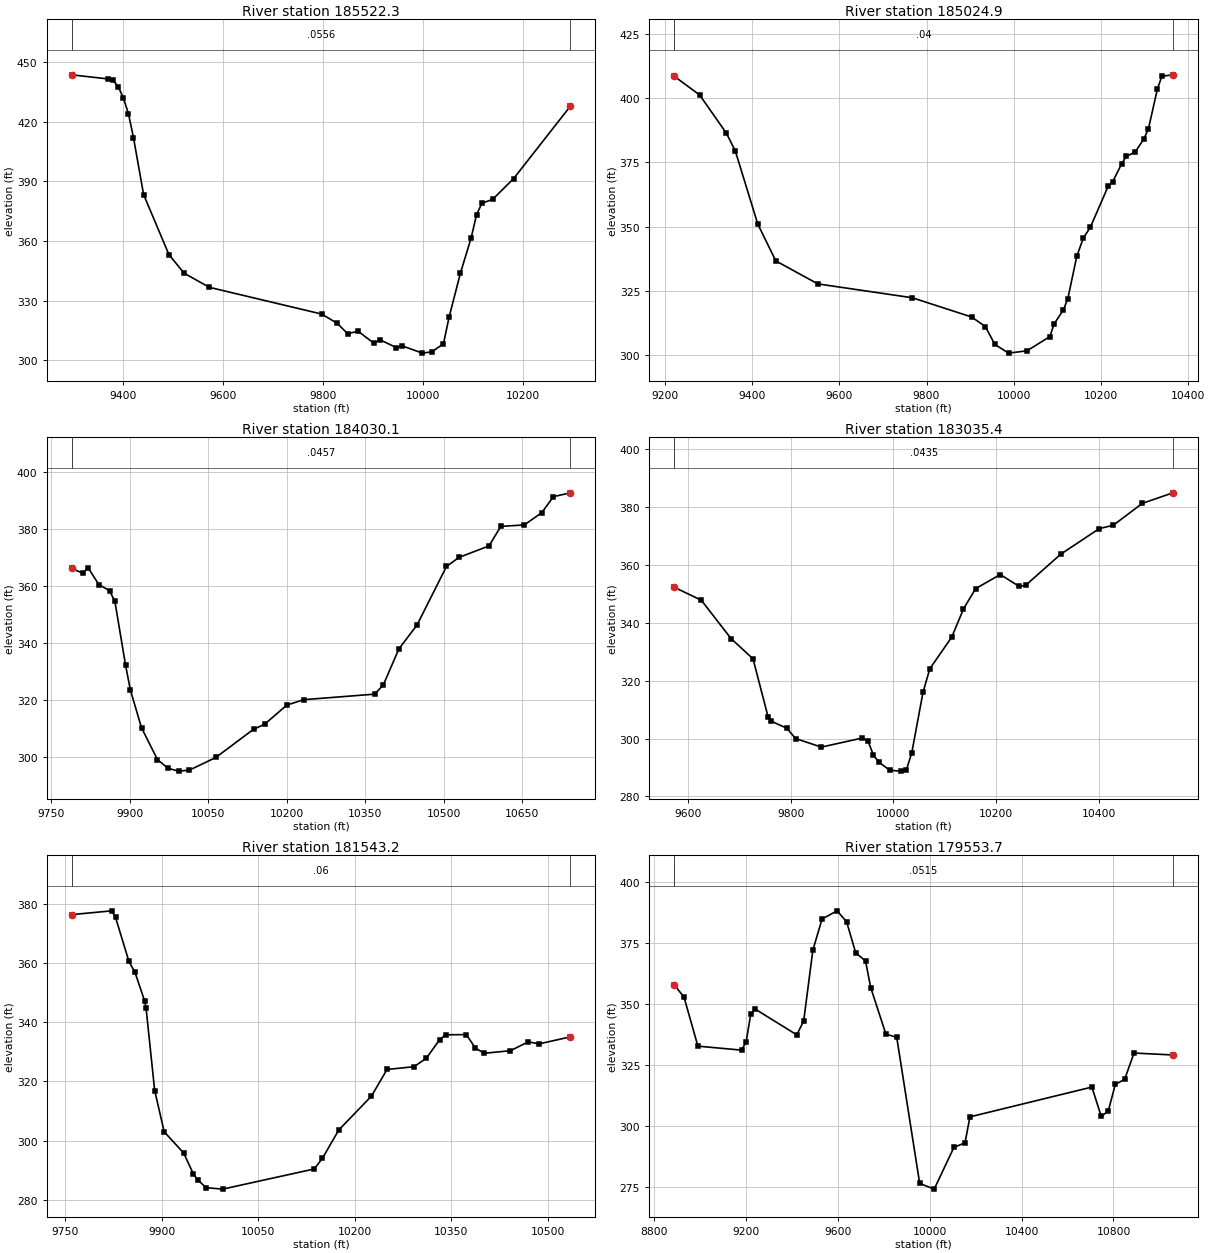
Type RM Length L Ch R = 1 ,185522.3,497.385600,497.385600,497.385600
XS GIS Cut Line= 6
814312.151426196776603.799326435814576.414542049776640.066407531
814819.892064214776689.445570603814913.888248652776721.329990625
815103.637329757776821.905657902815264.936776767776865.397920325
#Sta/Elev= 30
9297.533443.65999370.908441.58519380.988440.86479391.069 437.5089401.149432.0118
9411.229424.0636 9421.31412.01239441.512383.40739492.079353.21579522.419343.8266
9573.021336.69549797.489323.25089828.617318.60779849.529313.37389870.441314.5976
9902.604308.44519913.379310.39699946.765306.39099958.339307.2609    9999303.5762
10017.81304.236510041.16308.248710052.47321.715610074.99343.750810096.58361.6254
10107.38373.311510118.18379.041710139.44380.954510181.48391.4347 10294.7427.7923
#Mann= 3 , 0 , 0
9297.533  0.0556       09297.533  0.0556       0 10294.7  0.0556       0
#XS Ineff= 2 , 0
       0                               0
Bank Sta=9297.533,10294.7
Exp/Cntr=0.3,0.1

Type RM Length L Ch R = 1 ,185024.9,994.771100,994.771100,994.771100
XS GIS Cut Line= 6
814077.925113231777019.220732957814247.852469921777055.098481521
814383.549814582777090.678051993814869.455661178777245.321533889
815044.299844861777290.998716041815179.960718326777319.602903734
#Sta/Elev= 30
9221.624408.46339279.739401.19179341.182386.31019361.666379.34319413.041351.0011
9454.393336.66999550.802327.72829767.207322.34699903.506314.85549935.139311.1079
9956.273304.24769987.973300.813410030.28301.710510082.51307.2056 10092.9312.2784
10113.69317.570410124.01322.007410144.62338.545510159.74345.636210175.52349.7045
10216.73365.802610227.03367.515310247.51374.452910257.75377.284710278.22 378.973
 10298.7384.184510308.94388.150410329.42403.5733 10339.6408.453410364.97 409.019
#Mann= 3 , 0 , 0
9221.624    0.04       09221.624    0.04       010364.97    0.04       0
#XS Ineff= 2 , 0
       0                               0
Bank Sta=9221.624,10364.97
Exp/Cntr=0.3,0.1

Type RM Length L Ch R = 1 ,184030.1,994.771100,994.771100,994.771100
XS GIS Cut Line= 6
814304.066093709778187.871619615 814597.87948823778131.249906868
814693.196753532778103.482417241814796.750727445 778056.77523607
  815044.0069139777916.043226391815183.949117541777846.261994436
#Sta/Elev= 30
9788.604366.30189810.002364.58519820.223 366.4889840.666  360.619861.109358.4759
 9871.33 354.7059891.753332.31179900.869323.67739922.237310.3431 9952.72299.1752
9973.043296.09949993.365295.117610013.64295.456510064.52 299.93410136.54309.8282
10157.51311.563610199.97318.299810232.43   320.2 10368.1322.141610384.49325.4034
10414.28338.038310448.91 346.41310505.19366.9564 10529.3370.162710586.49374.1687
10609.04381.028610653.99381.541510687.34385.846910709.58391.459610741.76392.8101
#Mann= 3 , 0 , 0
9788.604  0.0457       09788.604  0.0457       010741.76  0.0457       0
#XS Ineff= 2 , 0
       0                               0
Bank Sta=9788.604,10741.76
Exp/Cntr=0.3,0.1

Type RM Length L Ch R = 1 ,183035.4,1492.156600,1492.156600,1492.156600
XS GIS Cut Line= 6
815064.545557439 778827.16257821815249.210422665778649.401091531
 815293.37360993778579.952807441815415.151549548778326.144475147
815527.945442021778182.237561807815646.528645933778064.039626732
#Sta/Elev= 30
9572.933 352.3439625.673347.85619683.622334.58949726.424327.5883 9755.64307.6159
9762.417305.99719792.378303.5818 9809.28300.03669859.567297.06859939.577 300.208
9950.551   299.29961.202294.23339971.852291.85719993.153 289.04910014.47288.7594
10025.13289.015610035.95295.155810057.74315.969910070.98324.146610113.92335.1304
 10136.7344.870510160.37351.867810208.32356.743410245.44352.624710257.82353.0156
10326.22363.7744 10401.2372.610810428.73373.783610485.35381.368410544.97385.0007
#Mann= 3 , 0 , 0
9572.933  0.0435       09572.933  0.0435       010544.97  0.0435       0
#XS Ineff= 2 , 0
       0                               0
Bank Sta=9572.933,10544.97
Exp/Cntr=0.3,0.1

Type RM Length L Ch R = 1 ,181543.2,1989.542200,1989.542200,1989.542200
XS GIS Cut Line= 6
815308.398867577780070.422696829815509.540029764 779892.66844511
815665.080445111779770.742642447 815744.16680339779702.348102778
815822.704926997779626.496286631815888.665143671 779558.11670464
#Sta/Elev= 30
9760.243 376.2849822.702 377.5679828.513375.35429849.352360.48019858.775356.7967
9873.906347.04699876.002344.67439889.326316.94779904.167303.01389934.429295.8558
 9949.56288.76039955.951286.86029969.276284.17399994.953283.685110137.26290.4865
10149.97294.070610175.38303.628910226.21315.071810250.38324.053910292.31324.9866
10311.53327.857310332.03334.067110341.45335.750110373.73335.809410387.64331.2507
10401.54329.518110442.14330.377810469.94333.376310486.54332.673510535.06335.0463
#Mann= 3 , 0 , 0
9760.243    0.06       09760.243    0.06       010535.06    0.06       0
#XS Ineff= 2 , 0
       0                10384.66       0
Bank Sta=9760.243,10535.06
Exp/Cntr=0.3,0.1

Type RM Length L Ch R = 1 ,179553.7,1989.542100,1989.542100,1989.542100
XS GIS Cut Line= 6
 817638.18921721780717.608196244817664.076336324780039.350748092
817503.128981233779850.349115759817146.957912326779478.888281345
816977.833944142 779216.23859489 817056.61098963778808.785370737
#Sta/Elev= 30
8888.982 357.9178931.621352.76588991.665332.75859181.803 331.1289201.818334.5603
9221.832346.01149241.847347.89389421.978337.4035    9452343.06729492.029372.1346
9532.058 384.8889597.273388.23769638.918383.76569678.209371.07219721.153367.6775
9743.696356.77569809.773337.70599856.964336.37099956.811276.481710019.99274.1439
10105.83291.2721 10154.1293.1278 10175.4 303.76710706.19315.983810746.93303.9502
10777.49306.199310808.04317.051710848.78319.170810889.52329.936111058.81 329.144
#Mann= 3 , 0 , 0
8888.982  0.0515       08888.982  0.0515       011058.81  0.0515       0
#XS Ineff= 2 , 0
       0                               0
Bank Sta=8888.982,11058.81
Exp/Cntr=0.3,0.1

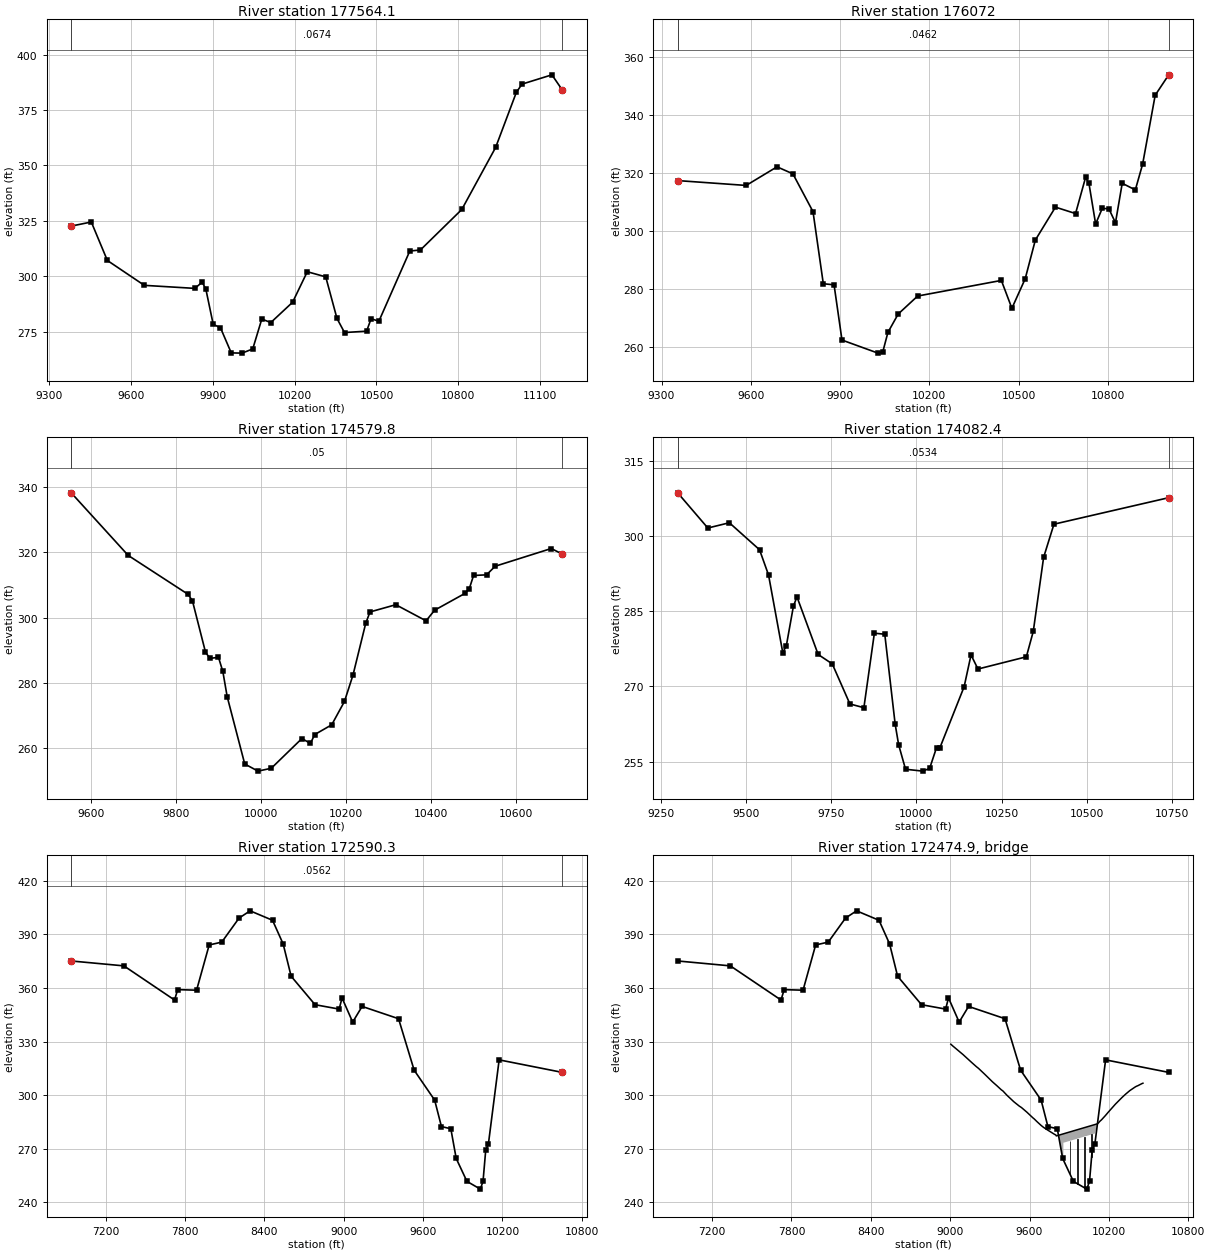
Type RM Length L Ch R = 1 ,177564.1,1492.156700,1492.156700,1492.156700
XS GIS Cut Line= 6
818355.620094806779990.035875589818423.212756723779872.016338348
818538.641203701779730.151330203818619.641322941779650.399871454
819091.206658185779227.220953405819601.152372757778697.854441724
#Sta/Elev= 30
9379.936322.66539453.636324.51399512.521307.17029648.186295.95379833.482294.5863
9860.431297.39389873.905294.24919900.853278.39159927.621276.80389967.101265.5029
10006.56265.398210045.96267.286110079.19280.768810112.13279.169410192.15288.3336
10246.04 302.09510313.75299.779910355.04281.018410382.67274.678410463.73275.2979
10480.27280.931310508.64279.757210622.15311.423810661.08311.896310812.91 330.151
10937.11358.118511013.03382.928511033.71386.664811143.63390.859111181.58384.0433
#Mann= 3 , 0 , 0
9379.936  0.0674       09379.936  0.0674       011181.58  0.0674       0
#XS Ineff= 2 , 0
       0                10284.88       0
Bank Sta=9379.936,11181.58
Exp/Cntr=0.3,0.1

Type RM Length L Ch R = 1 ,  176072,1492.156600,1492.156600,1492.156600
XS GIS Cut Line= 6
819309.348864892780659.100144507819550.146137741780610.772584062
819714.379817482780555.004109249 820227.98532261780218.489659789
820546.036519932780048.430087716820775.956621921779936.666544923
#Sta/Elev= 30
9354.296317.44559584.414315.77539688.102322.18859741.528319.77249809.066 306.744
9843.691281.91789879.844281.53329906.442262.514810027.46258.009310043.34258.3386
10060.83265.154710095.38271.484510160.76277.677610442.05283.055210477.46273.4526
 10522.2283.629610556.27296.958710623.85308.301110691.43306.088710725.22318.5783
10736.48316.455310758.88302.497710781.11307.862910803.35307.743310825.59302.9248
10848.25316.5162 10892.3314.236110916.87323.124710959.02346.849111004.56353.8796
#Mann= 3 , 0 , 0
9354.296  0.0462       09354.296  0.0462       011004.56  0.0462       0
#XS Ineff= 2 , 0
       0                               0
Bank Sta=9354.296,11004.56
Exp/Cntr=0.3,0.1

Type RM Length L Ch R = 1 ,174579.8,497.385500,497.385500,497.385500
XS GIS Cut Line= 6
818891.761039585781676.086225957819186.890676618781637.266499221
819389.549088269781584.235378131819469.240481317781573.112184256
 819628.52159211781584.972600892820030.574647299781659.532765752
#Sta/Elev= 30
9552.983338.1296 9687.22318.99999828.537307.08359838.653305.06399869.211289.4725
9879.442287.52969899.906287.84929910.138283.5329 9920.37275.8434 9961.73255.2542
9993.055253.071210024.34253.9534 10096.4263.0314 10116.5  261.5410126.55264.2473
10166.62267.228710196.62274.359810216.67282.394510246.79298.275610256.88301.7253
10317.59303.933810388.83299.015710409.18 302.26310480.42307.3809 10490.6308.7847
10500.78312.867610531.31313.062610551.66315.689610683.82 321.10710709.74319.4087
#Mann= 3 , 0 , 0
9552.983    0.05       09552.983    0.05       010709.74    0.05       0
#XS Ineff= 2 , 0
       0                               0
Bank Sta=9552.983,10709.74
Exp/Cntr=0.3,0.1

Type RM Length L Ch R = 1 ,174082.4,1492.156600,1492.156600,1492.156600
XS GIS Cut Line= 6
818750.905543357782267.955451518819072.720794559782167.024834976
819300.302852094782108.663202718819785.622953653782028.766373649
819947.233258039782006.447464705820159.580478331781985.698451784
#Sta/Elev= 30
9299.669308.57389388.132301.55779451.248302.6071 9539.84297.22639566.246292.1918
9608.016276.70589618.458278.08489639.324286.0126 9649.68287.82729711.815276.3463
9753.238274.46799804.924266.48239845.975265.73669876.725280.58759907.261 280.384
9937.797262.41799947.954258.33999968.163253.466210018.67 253.08910038.86253.6298
10059.06257.762910069.16257.777110140.05269.910910160.34276.257710180.63273.4448
10322.65275.882410342.94280.947910373.33295.718610403.61 302.32110740.37 307.605
#Mann= 3 , 0 , 0
9299.669  0.0534       09299.669  0.0534       010740.37  0.0534       0
#XS Ineff= 2 , 0
       0  9837.5                       0
Bank Sta=9299.669,10740.37
Exp/Cntr=0.3,0.1

Type RM Length L Ch R = 1 ,172590.3,204.173200,204.173200,204.173200
XS GIS Cut Line= 6
817292.889654487 783943.55833739818533.868869454 783103.24431397
818763.439195424783081.586736053819036.324677229 783107.57582958
819488.968055844783337.146155536820665.661225071783560.333656172
#Sta/Elev= 30
6939.905375.06897338.131372.33017721.155353.21677744.958359.03727887.772 358.712
7982.982384.02848078.192385.61938209.105399.08768292.414403.12888462.068 397.843
8542.423384.55848602.689366.52768783.498350.59648965.808348.14578987.501354.4013
9068.022340.86439139.347349.63979414.817  342.769532.777313.94949687.783297.2213
9739.108282.39799810.133281.19049850.719264.56779931.891251.740210033.35247.3995
10053.65251.800510073.94269.219910094.23272.6761 10175.4319.729710652.66312.7283
#Mann= 3 , 0 , 0
6939.905  0.0562       06939.905  0.0562       010652.66  0.0562       0
#XS Ineff= 2 , 0
       0                               0
Bank Sta=6939.905,10652.66
Exp/Cntr=0.3,0.1

Type RM Length L Ch R = 3 ,172474.9,,,
BEGIN DESCRIPTION:
END DESCRIPTION:
Bridge Culvert--1,0,-1,-1, 0
Deck Dist Width WeirC Skew NumUp NumDn MinLoCord MaxHiCord MaxSubmerge Is_Ogee
79.086600,46.000000,2.6,0, 45, 42, , , 0.95, 0, 0,0,,
 9005.06 9019.66 9097.39 9164.01 9197.32 9214.74 9260.76 9319.45 9352.80 9386.08
 9398.82 9429.47 9481.41 9522.96 9536.96 9543.74 9580.47 9625.54 9635.73 9656.12
 9686.70 9696.90 9707.09 9737.67 9788.64 9798.83 9802.50 9856.06 9856.0610114.22
10122.0610122.0610133.8310143.9710174.3910195.0910249.4210301.3010327.0610357.64
10398.4010408.5910418.7810449.3610457.64
  328.50  327.52  322.69  318.18  315.99  314.95  311.73  307.48  305.30  303.02
  302.34  299.92  296.30  293.84  293.17  292.77  290.44  287.30  286.68  285.19
  283.12  282.50  281.91  280.44  278.08  277.70  277.17  278.34  278.34  283.97
  284.54  284.54  285.50  286.15  288.61  290.42  294.95  298.82  300.57  302.49
  304.53  304.96  305.26  306.42  306.67
 -671.50 -672.48 -677.31 -681.82 -684.01 -685.05 -688.27 -692.52 -694.70 -696.98
 -697.66 -700.08 -703.70 -706.16 -706.83 -707.23 -709.56 -712.70 -713.32 -714.81
 -716.88 -717.50 -718.09 -719.56 -721.92 -722.30 -722.83 -721.66  273.34  278.97
  279.54 -715.46 -714.50 -713.85 -711.39 -709.58 -705.05 -701.18 -699.43 -697.51
 -695.47 -695.04 -694.74 -693.58 -693.33
 9005.06 9019.66 9097.39 9164.01 9197.32 9214.74 9260.76 9319.45 9352.80 9386.08
 9398.82 9429.47 9481.41 9522.96 9536.96 9543.74 9580.47 9625.54 9635.73 9656.12
 9686.70 9696.90 9707.09 9737.67 9788.64 9798.83 9802.50 9826.28 9826.2810092.28
10092.2810114.2210133.8310143.9710174.3910204.8110255.7310301.3010347.4510367.83
10405.0710457.64
  328.50  327.52  322.69  318.18  315.99  314.95  311.73  307.48  305.30  303.02
  302.34  299.92  296.30  293.84  293.17  292.77  290.44  287.30  286.68  285.19
  283.12  282.50  281.91  280.44  278.08  277.70  277.17  277.69  277.69  283.50
  283.50  283.97  285.50  286.15  288.61  291.24  295.44  298.82  301.89  303.03
  304.82  306.67
 -671.50 -672.48 -677.31 -681.82 -684.01 -685.05 -688.27 -692.52 -694.70 -696.98
 -697.66 -700.08 -703.70 -706.16 -706.83 -707.23 -709.56 -712.70 -713.32 -714.81
 -716.88 -717.50 -718.09 -719.56 -721.92 -722.30 -722.83 -722.31  272.69  278.50
 -716.50 -716.03 -714.50 -713.85 -711.39 -708.76 -704.56 -701.18 -698.11 -696.97
 -695.18 -693.33
Pier Skew, UpSta & Num, DnSta & Num=  ,9908.66, 2 ,9878.88, 2 , 0 , 0 , 0 ,,
    2.00    2.00
 -720.51  279.49
    2.00    2.00
 -721.16  278.84
Pier Skew, UpSta & Num, DnSta & Num=  ,9962.26, 2 ,9932.48, 2 , 0 , 0 , 0 ,,
    2.00    2.00
 -719.34  280.66
    2.00    2.00
 -719.99  280.01
Pier Skew, UpSta & Num, DnSta & Num=  ,10015.86, 2 ,9986.08, 2 , 0 , 0 , 0 ,,
    2.00    2.00
 -718.17  281.83
    2.00    2.00
 -718.82  281.18
Pier Skew, UpSta & Num, DnSta & Num=  ,10069.46, 2 ,10039.68, 2 , 0 , 0 , 0 ,,
    2.00    2.00
 -717.00  283.00
    2.00    2.00
 -717.65  282.35
BR Coef=-1 , 0 , 0 ,, 0 ,,,0.8,0,1,0,
WSPro=,,,, 1 ,,,, 0 ,,,, 0 ,,,,-1 ,-1 ,-1 , 0 , 0 , 0 , 0 , 0
BC Design=,, 0 ,, 0 ,,,,,,

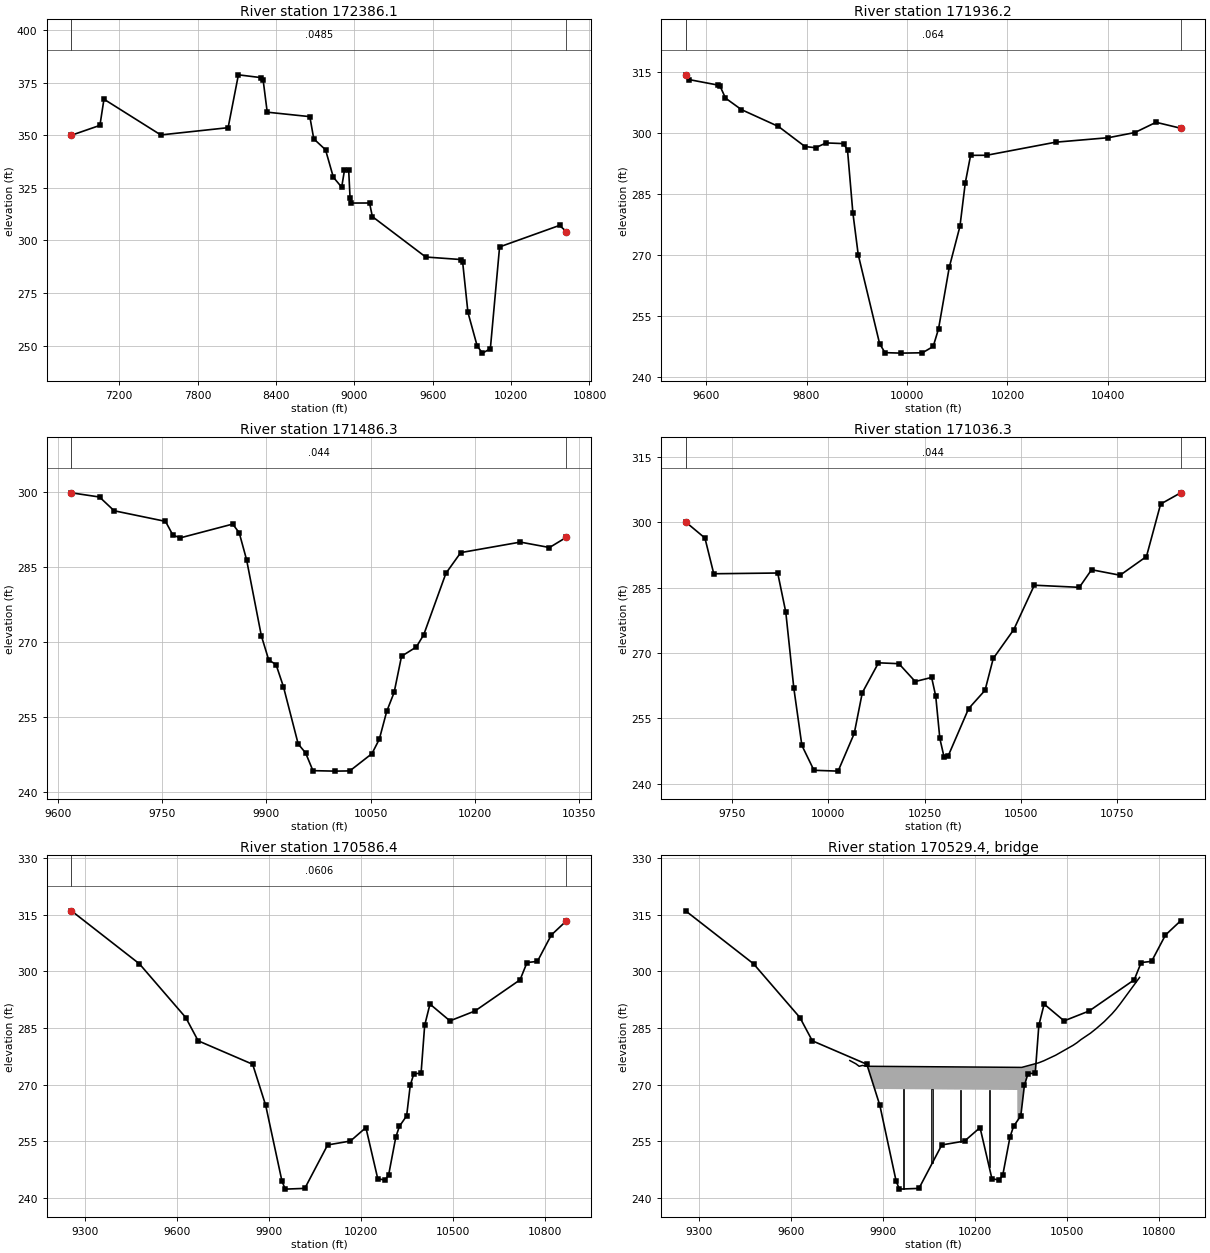
Type RM Length L Ch R = 1 ,172386.1,449.915400,449.915400,449.915400
XS GIS Cut Line= 6
817381.685723931784402.698989362818191.679138273783657.678308815
818681.140399337783295.996757492818977.849216878783295.996757492
819790.008388996783610.031637385820688.458614079783731.314073741
#Sta/Elev= 30
6835.001349.94717053.177354.64327084.066367.08247518.843350.09868034.285353.5437
8113.071378.6633 8289.19377.3112 8302.13376.29528333.672360.91098659.782358.7933
8689.782348.23748779.782343.05688839.782 329.9918903.587325.24198924.919333.3584
8956.917333.66278967.583320.26098978.249317.72399116.906317.7513 9138.31311.2859
  9546.8292.07639819.408290.86399829.501289.61319869.877 265.7699940.535249.8176
 9980.91246.399310041.47248.486210112.13296.878710570.81307.096410624.27304.1288
#Mann= 3 , 0 , 0
6835.001  0.0485       06835.001  0.0485       010624.27  0.0485       0
#XS Ineff= 2 , 0
       0                               0
Bank Sta=6835.001,10624.27
Exp/Cntr=0.3,0.1

Type RM Length L Ch R = 1 ,171936.2,449.915400,449.915400,449.915400
XS GIS Cut Line= 6
819779.273478895784224.428453311819852.544816613784201.255670562
820063.848217934784130.072300926 820286.61177972784047.823805287
820427.136961192 783998.76548554820711.711848915783905.713334993
#Sta/Elev= 30
9559.276314.20929565.282313.05899623.706311.69049628.211311.34379638.715308.4839
9670.371305.65789744.236301.50279796.997296.56389818.102296.28759839.206297.4641
9873.804 297.2959881.629295.70099892.283280.29159902.936269.9889 9945.55248.0785
9956.204245.88779988.164245.767810030.83245.854810052.17247.399210062.83251.7408
10084.17266.872910105.44276.959210116.03 287.61110126.63294.4071 10158.4294.4238
10295.79297.640410401.06298.7505 10453.7300.015910495.81302.536710544.81301.0788
#Mann= 3 , 0 , 0
9559.276   0.064       09559.276   0.064       010544.81   0.064       0
#XS Ineff= 2 , 0
       0                               0
Bank Sta=9559.276,10544.81
Exp/Cntr=0.3,0.1

Type RM Length L Ch R = 1 ,171486.3,449.915400,449.915400,449.915400
XS GIS Cut Line= 6
819986.599982917784629.954314604820088.082266748784596.757338285
820345.126191974784505.866700754820347.012313843784505.201460719
820393.214391381 784488.76996626820657.981257353784392.245213346
#Sta/Elev= 30
9619.586299.86289659.988299.02639681.031296.27479754.911294.15259765.518291.4171
9776.124290.84949851.617293.60899860.978291.87599871.585286.47679892.799271.2817
9903.405266.43969914.012265.48539924.619261.07179945.832249.61279956.439247.8381
9967.046244.27889998.866244.183610020.09244.227910051.94247.681110062.58250.5816
10073.23256.148910083.87259.934410094.51267.1659 10115.8269.022210126.44271.4703
10158.38283.765610179.66   287.910265.42290.004810307.39288.920810331.85 290.982
#Mann= 3 , 0 , 0
9619.586   0.044       09619.586   0.044       010331.85   0.044       0
#XS Ineff= 2 , 0
       0                               0
Bank Sta=9619.586,10331.85
Exp/Cntr=0.3,0.1

Type RM Length L Ch R = 1 ,171036.3,449.915400,449.915400,449.915400
XS GIS Cut Line= 6
820147.103859425785036.967146382820388.653713167784960.449952811
820611.374857664784892.782628134820728.463949919784851.985211223
821126.406943351784706.536126405 821364.55691201784627.885001256
#Sta/Elev= 30
9629.993 300.0419680.194296.34169703.124288.1541 9869.05 288.3239889.999279.3557
9910.875 261.9249931.751248.81669963.065243.110310025.76242.917710067.62251.5526
10088.55260.894410130.58267.743710183.53267.541910225.89263.452910268.43 264.392
 10279.1260.092110289.76250.400310300.42246.261210311.08246.331310364.38257.2412
10407.03261.445510428.35268.742510481.66275.360410534.91285.528610651.73285.0411
10683.48289.075910757.44287.817610825.92292.106110862.62304.126410914.65306.7021
#Mann= 3 , 0 , 0
9629.993   0.044       09629.993   0.044       010914.65   0.044       0
#XS Ineff= 2 , 0
       0                10213.83       0
Bank Sta=9629.993,10914.65
Exp/Cntr=0.3,0.1

Type RM Length L Ch R = 1 ,170586.4,130.723800,130.723800,130.723800
XS GIS Cut Line= 6
819954.394731005785479.510120725 820097.09075886785472.811106741
820417.217935681785432.491432071820878.816912949785267.012553424
821170.582304269785086.292199105821448.872882575 784939.59858945
#Sta/Elev= 30
9255.448316.03819477.012302.00929628.197287.77699668.513281.62929846.265275.4141
9888.758264.52249941.873244.44319952.497 242.36110016.24242.5581 10090.6254.0572
10164.96255.093510215.33258.650310254.07245.106310277.59244.782110289.36246.0554
10312.88256.134210324.65258.998110348.17 261.75610359.94269.8433 10371.7272.9343
10395.22 273.02510406.99285.720110424.23291.346710489.33286.906810571.01289.5241
10717.96297.774810740.57302.346810774.48302.6551 10819.7309.626810869.29313.4047
#Mann= 3 , 0 , 0
9255.448  0.0606       09255.448  0.0606       010869.29  0.0606       0
#XS Ineff= 2 , 0
       0                               0
Bank Sta=9255.448,10869.29
Exp/Cntr=0.3,0.1

Type RM Length L Ch R = 3 ,170529.4,,,
BEGIN DESCRIPTION:
END DESCRIPTION:
Bridge Culvert--1,0,-1,-1, 0
Deck Dist Width WeirC Skew NumUp NumDn MinLoCord MaxHiCord MaxSubmerge Is_Ogee
46.361900,38.000000,2.6,0, 23, 23, , , 0.95, 0, 0,0,,
 9790.93 9810.61 9821.31 9832.00 9845.01 9874.64 9874.6410336.6410336.6410351.24
10406.3010423.2010461.5410518.7210531.4110544.1010575.2010594.8810620.2610645.65
10658.3410672.6310735.34
  276.40  275.54  274.88  275.11  274.89  274.87  274.87  274.60  274.60  274.59
  275.80  276.34  277.80  280.44  281.13  281.94  283.64  284.92  286.71  288.79
  289.97  291.46  298.40
 -723.60 -724.46 -725.12 -724.89 -725.11 -725.13  268.87  268.60 -725.40 -725.41
 -724.20 -723.66 -722.20 -719.56 -718.87 -718.06 -716.36 -715.08 -713.29 -711.21
 -710.03 -708.54 -701.60
 9790.93 9810.61 9821.31 9832.00 9845.01 9859.25 9859.2510321.2510321.2510351.24
10406.3010423.2010461.5410518.7210531.4110544.1010575.2010594.8810620.2610645.65
10658.3410672.6310735.34
  276.40  275.54  274.88  275.11  274.89  274.88  274.88  274.61  274.61  274.59
  275.80  276.34  277.80  280.44  281.13  281.94  283.64  284.92  286.71  288.79
  289.97  291.46  298.40
 -723.60 -724.46 -725.12 -724.89 -725.11 -725.12  268.88  268.61 -725.39 -725.41
 -724.20 -723.66 -722.20 -719.56 -718.87 -718.06 -716.36 -715.08 -713.29 -711.21
 -710.03 -708.54 -701.60
Pier Skew, UpSta & Num, DnSta & Num=  ,9965.84, 2 ,9950.45, 2 , 0 , 0 , 0 ,,
    4.00    4.00
 -725.18  274.82
    4.00    4.00
 -725.17  274.83
Pier Skew, UpSta & Num, DnSta & Num=  ,10059.04, 2 ,10043.65, 2 , 0 , 0 , 0 ,,
    4.00    4.00
 -725.23  274.77
    4.00    4.00
 -725.23  274.77
Pier Skew, UpSta & Num, DnSta & Num=  ,10152.24, 2 ,10136.85, 2 , 0 , 0 , 0 ,,
    4.00    4.00
 -725.29  274.71
    4.00    4.00
 -725.28  274.72
Pier Skew, UpSta & Num, DnSta & Num=  ,10245.44, 2 ,10230.05, 2 , 0 , 0 , 0 ,,
    4.00    4.00
 -725.34  274.66
    4.00    4.00
 -725.33  274.67
BR Coef=-1 , 0 , 0 ,, 0 ,,,0.8,0,1,0,
WSPro=,,,, 1 ,,,, 0 ,,,, 0 ,,,,-1 ,-1 ,-1 , 0 , 0 , 0 , 0 , 0
BC Design=,, 0 ,, 0 ,,,,,,