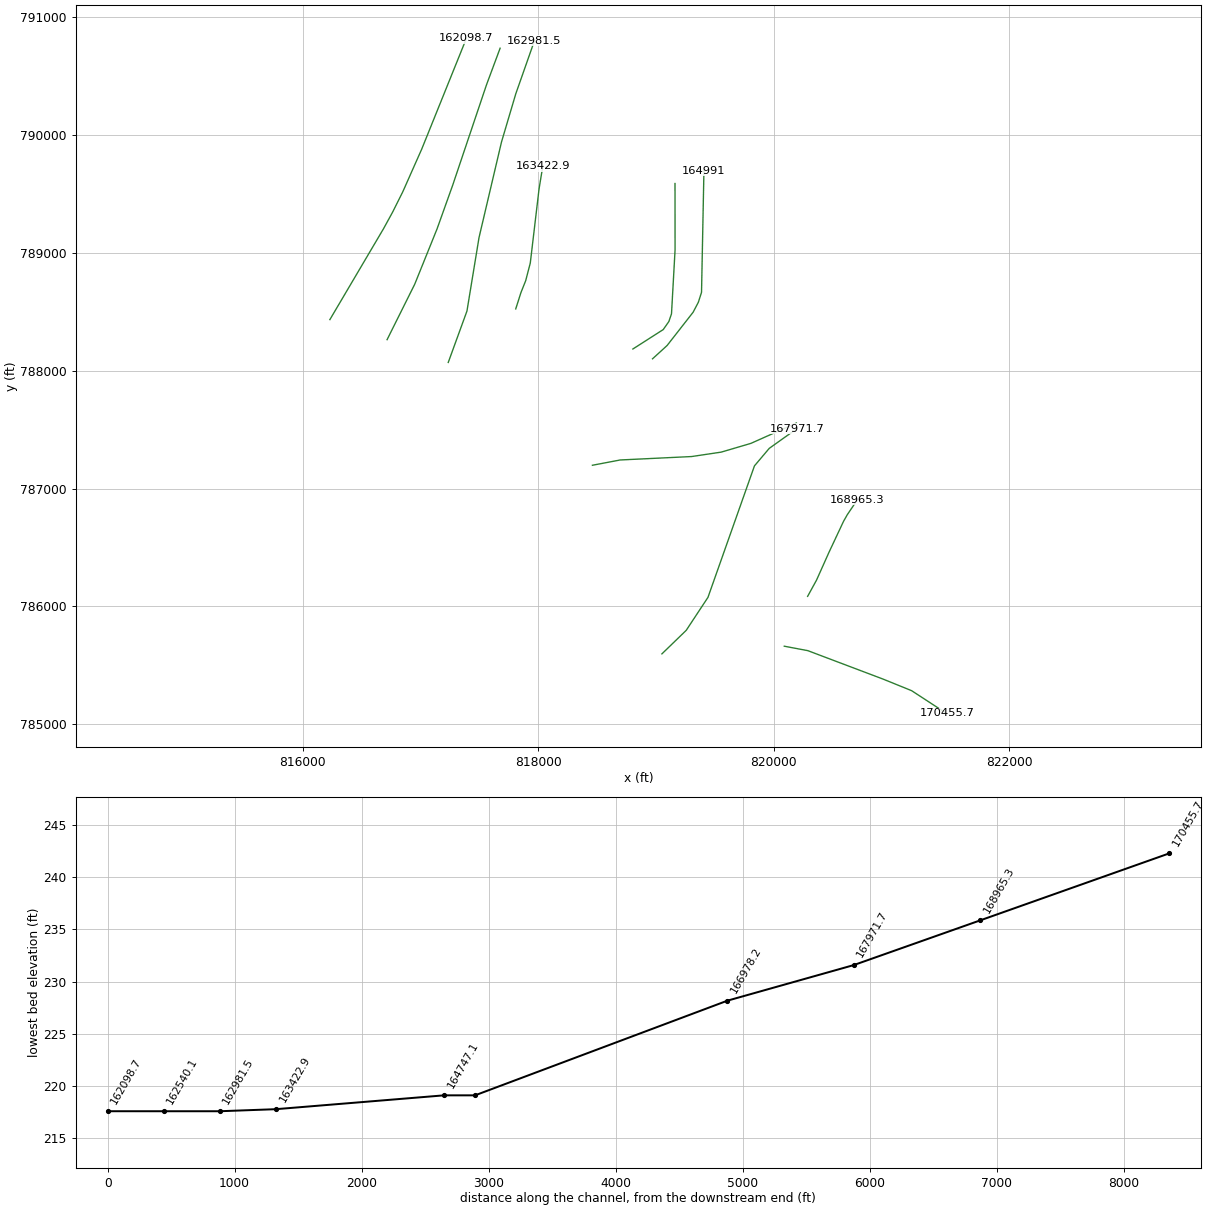
HEC-RAS study 17203_ras.prj: 17203

--- 17203_ras.g01 (geometry) --- (continued)

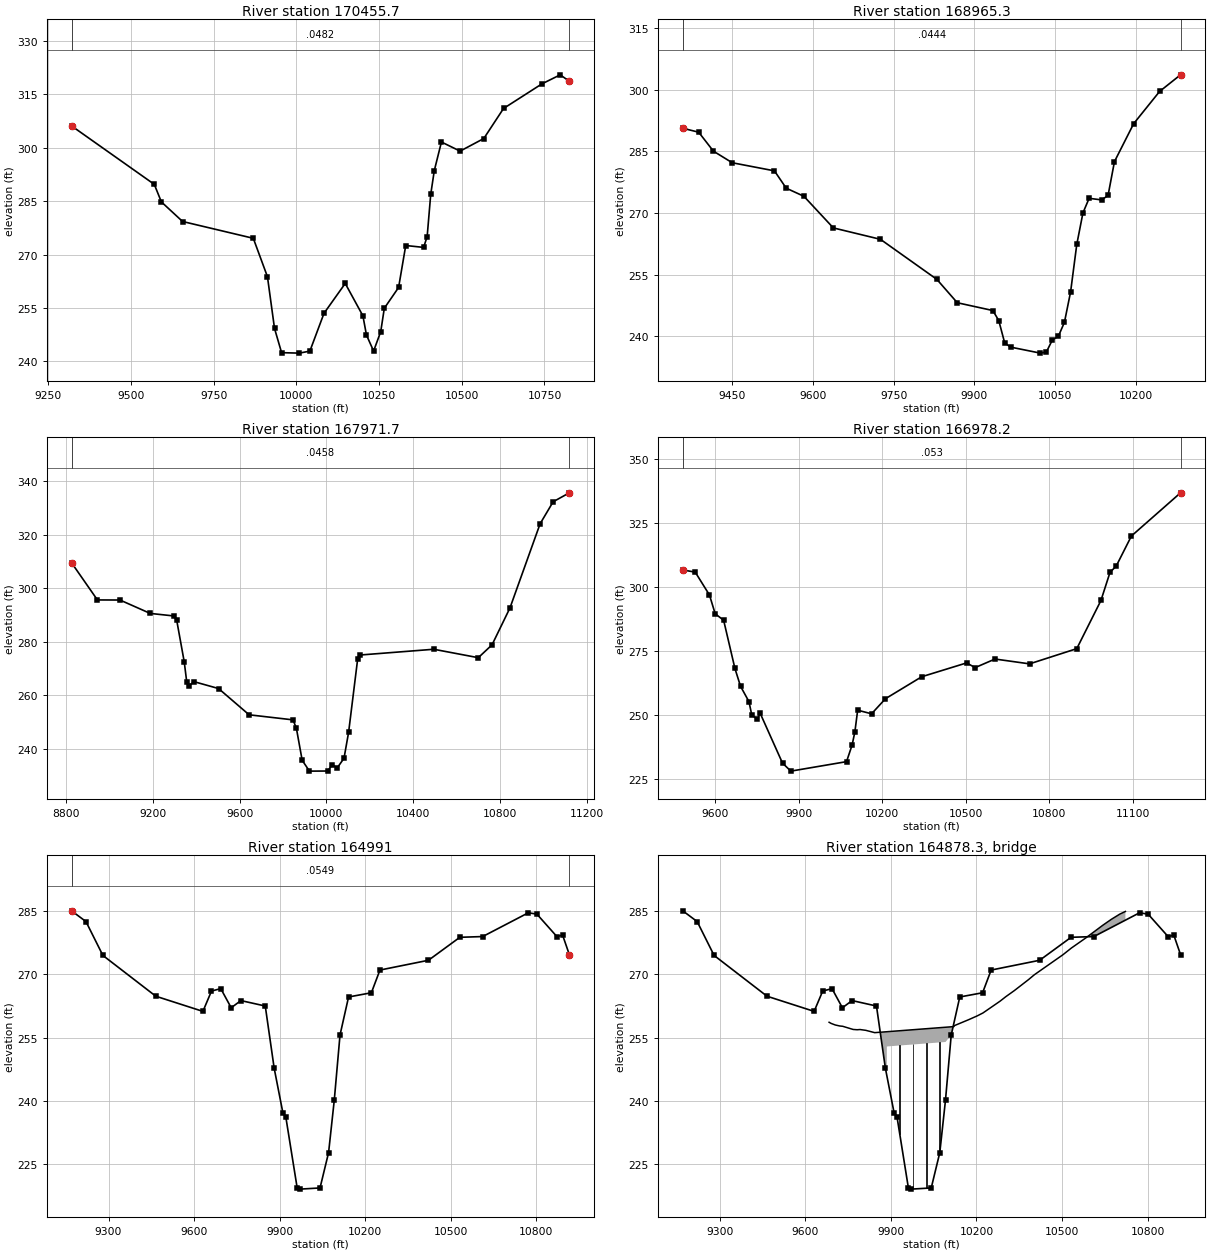
Type RM Length L Ch R = 1 ,170455.7,1490.376800,1490.376800,1490.376800
XS GIS Cut Line= 6
820091.451546825785661.733387257820290.931423068785624.098554716
820931.073400974785382.412297755821172.759657949 785284.43138276
821447.106219918785105.888382137821472.745521039785091.678648993
#Sta/Elev= 30
9320.358306.13839570.462289.7162 9591.84284.78849655.974279.28189869.753274.5611
9912.509263.76939933.887249.24579955.265242.426710008.71242.298710040.78242.8631
10083.53253.496110147.67261.877410201.11252.772710211.84247.381310233.42242.8864
   10255248.355210265.79254.907510308.96260.745110330.54272.537710384.49 272.008
10395.28 275.01210406.07286.880110416.86293.578310438.44301.614910494.93299.0535
10566.52 302.59410626.17311.038610742.35317.958510797.56320.492310825.04318.6895
#Mann= 3 , 0 , 0
9320.358  0.0482       09320.358  0.0482       010825.04  0.0482       0
#XS Ineff= 2 , 0
       0                               0
Bank Sta=9320.358,10825.04
Exp/Cntr=0.3,0.1

Type RM Length L Ch R = 1 ,168965.3,993.584500,993.584500,993.584500
XS GIS Cut Line= 6
820289.687978208786085.048067465820365.800122887786223.913307056
820471.174306512786459.052301407820594.837049395786721.866899714
820626.140212685 786777.29229179820713.485581595786906.446678685
#Sta/Elev= 30
9357.572 290.6429387.181289.68629414.592285.06699449.667282.24029528.156280.2679
9550.072276.04379582.947274.07449637.738266.36649725.404263.5878 9830.37253.8289
9868.395 248.1359934.518246.23729945.539243.80499956.559238.3571 9967.58237.3254
10022.97235.859210034.14236.134410045.31239.071110056.48239.970910067.75243.3663
10079.23250.783310090.72262.3414 10102.2270.023510113.69 273.57710136.99273.1892
10148.92 274.26810160.84282.5189 10196.6291.765110244.82299.610510283.78303.6624
#Mann= 3 , 0 , 0
9357.572  0.0444       09357.572  0.0444       010283.78  0.0444       0
#XS Ineff= 2 , 0
       0                               0
Bank Sta=9357.572,10283.78
Exp/Cntr=0.3,0.1

Type RM Length L Ch R = 1 ,167971.7,993.584500,993.584500,993.584500
XS GIS Cut Line= 6
819051.729634762785596.632383034819258.184593707785796.367080092
819442.877454191 786076.06232883819837.862368345 787192.24937357
819963.558187872787341.009834126820198.407078975787507.995950508
#Sta/Elev= 30
8825.199309.48988944.437295.59079048.482295.55749187.952290.55059297.617289.5963
9309.485288.26729344.772272.44559356.323264.93939367.874263.51779389.382 265.041
9503.129262.45619644.019252.63749846.197250.74839861.909247.63469888.601235.6405
9922.176231.5763 10006.7231.615710027.46234.032510049.75232.722210081.55236.4015
10102.76246.092910144.77273.674410155.13 274.99310495.43277.146910700.69273.9961
10764.06278.797310846.84292.609810985.74324.069211045.87332.297211120.49335.6438
#Mann= 3 , 0 , 0
8825.199  0.0458       08825.199  0.0458       011120.49  0.0458       0
#XS Ineff= 2 , 0
       0                               0
Bank Sta=8825.199,11120.49
Exp/Cntr=0.3,0.1

Type RM Length L Ch R = 1 ,166978.2,1987.169000,1987.169000,1987.169000
XS GIS Cut Line= 6
818461.406367902787197.480438578818698.050657169787242.428633581
819303.708935658787271.471906524819555.299253757787308.986753265
819807.762666346787383.276581574820194.594695173787555.923061102
#Sta/Elev= 30
9483.227306.58319528.088305.7257 9579.24296.81059599.685289.50649630.128286.9807
9670.703268.19259690.896261.23479721.185255.24649731.248 250.0659751.343248.4506
9761.391250.74219841.764231.28969871.792228.164310071.93231.859610091.93238.3327
10101.93243.475610111.93 251.91410161.94250.510910211.97256.398910342.25264.9554
10503.69270.3487 10534.1268.509110605.63271.8564 10729.8269.975710899.56275.9042
 10986.5  294.6911019.22305.704611041.04308.025411096.02319.810911272.54336.6413
#Mann= 3 , 0 , 0
9483.227   0.053       09483.227   0.053       011272.54   0.053       0
#XS Ineff= 2 , 0
       0                               0
Bank Sta=9483.227,11272.54
Exp/Cntr=0.3,0.1

Type RM Length L Ch R = 1 ,  164991,243.918700,243.918700,243.918700
XS GIS Cut Line= 6
818972.113831647 788100.98065022819096.062156022788214.072187066
819317.050005287788496.540036887819361.149073511788580.555638373
819388.310732245788665.469274566819408.754003462789698.535949444
#Sta/Elev= 30
9170.472285.10259220.945282.55649280.291274.52069465.808 264.8439630.915261.2458
9660.978266.06759693.584266.64679730.043262.10219763.997 263.8119849.493 262.517
9880.737247.75319911.429237.11819921.429236.23139961.433219.32929971.434219.0763
10041.44219.356410071.44227.739810091.44240.215710111.45255.615610141.45 264.663
10221.46265.664610251.46271.050110421.52 273.37210531.57278.820610611.61278.9979
10771.69284.6395 10801.7284.316710871.73278.989910891.74279.343410915.29274.7246
#Mann= 3 , 0 , 0
9170.472  0.0549       09170.472  0.0549       010915.29  0.0549       0
#XS Ineff= 2 , 0
       0                               0
Bank Sta=9170.472,10915.29
Exp/Cntr=0.3,0.1

Type RM Length L Ch R = 3 ,164878.3,,,
BEGIN DESCRIPTION:
END DESCRIPTION:
Bridge Culvert--1,0,-1,-1, 0
Deck Dist Width WeirC Skew NumUp NumDn MinLoCord MaxHiCord MaxSubmerge Is_Ogee
105.959350,32.000000,2.6,0, 31, 31, , , 0.95, 0, 0,0,,
 9683.43 9690.53 9705.03 9720.92 9731.05 9767.60 9781.70 9791.83 9812.09 9843.32
 9885.77 9885.7710115.7710115.7710120.9210122.7010172.7210202.7210222.7310282.74
10302.7410332.7510382.7610402.7710502.7910532.7910582.8010642.8110672.8210702.83
10722.07
  258.66  258.39  258.02  257.78  257.71  256.96  256.89  256.94  256.75  256.20
  256.42  256.42  257.61  257.61  257.64  257.87  259.28  260.18  260.87  263.67
  264.73  266.18  268.80  269.93  274.67  276.28  278.65  281.68  283.09  284.34
  284.95
 -741.34 -741.61 -741.98 -742.22 -742.29 -743.04 -743.11 -743.06 -743.25 -743.80
 -743.58  252.92  254.11 -742.39 -742.36 -742.13 -740.72 -739.82 -739.13 -736.33
 -735.27 -733.82 -731.20 -730.07 -725.33 -723.72 -721.35 -718.32 -716.91 -715.66
 -715.05
 9683.43 9690.53 9705.03 9720.92 9731.05 9767.60 9781.70 9791.83 9812.09 9843.32
 9856.42 9856.4210086.4210086.4210120.9210122.7010172.7210202.7210222.7310282.74
10302.7410332.7510382.7610402.7710502.7910532.7910582.8010642.8110672.8210702.83
10722.07
  258.66  258.39  258.02  257.78  257.71  256.96  256.89  256.94  256.75  256.20
  256.26  256.26  257.46  257.46  257.64  257.87  259.28  260.18  260.87  263.67
  264.73  266.18  268.80  269.93  274.67  276.28  278.65  281.68  283.09  284.34
  284.95
 -741.34 -741.61 -741.98 -742.22 -742.29 -743.04 -743.11 -743.06 -743.25 -743.80
 -743.74  252.76  253.96 -742.54 -742.36 -742.13 -740.72 -739.82 -739.13 -736.33
 -735.27 -733.82 -731.20 -730.07 -725.33 -723.72 -721.35 -718.32 -716.91 -715.66
 -715.05
Pier Skew, UpSta & Num, DnSta & Num=  ,9930.87, 2 ,9901.52, 2 , 0 , 0 , 0 ,,
    3.00    3.00
 -743.35  256.65
    3.00    3.00
 -743.50  256.50
Pier Skew, UpSta & Num, DnSta & Num=  ,9977.47, 2 ,9948.12, 2 , 0 , 0 , 0 ,,
    3.00    3.00
 -743.11  256.89
    3.00    3.00
 -743.26  256.74
Pier Skew, UpSta & Num, DnSta & Num=  ,10024.07, 2 ,9994.72, 2 , 0 , 0 , 0 ,,
    3.00    3.00
 -742.86  257.14
    3.00    3.00
 -743.02  256.98
Pier Skew, UpSta & Num, DnSta & Num=  ,10070.67, 2 ,10041.32, 2 , 0 , 0 , 0 ,,
    3.00    3.00
 -742.62  257.38
    3.00    3.00
 -742.77  257.23
BR Coef=-1 , 0 , 0 ,, 0 ,,,0.8,0,1,0,
WSPro=,,,, 1 ,,,, 0 ,,,, 0 ,,,,-1 ,-1 ,-1 , 0 , 0 , 0 , 0 , 0
BC Design=,, 0 ,, 0 ,,,,,,

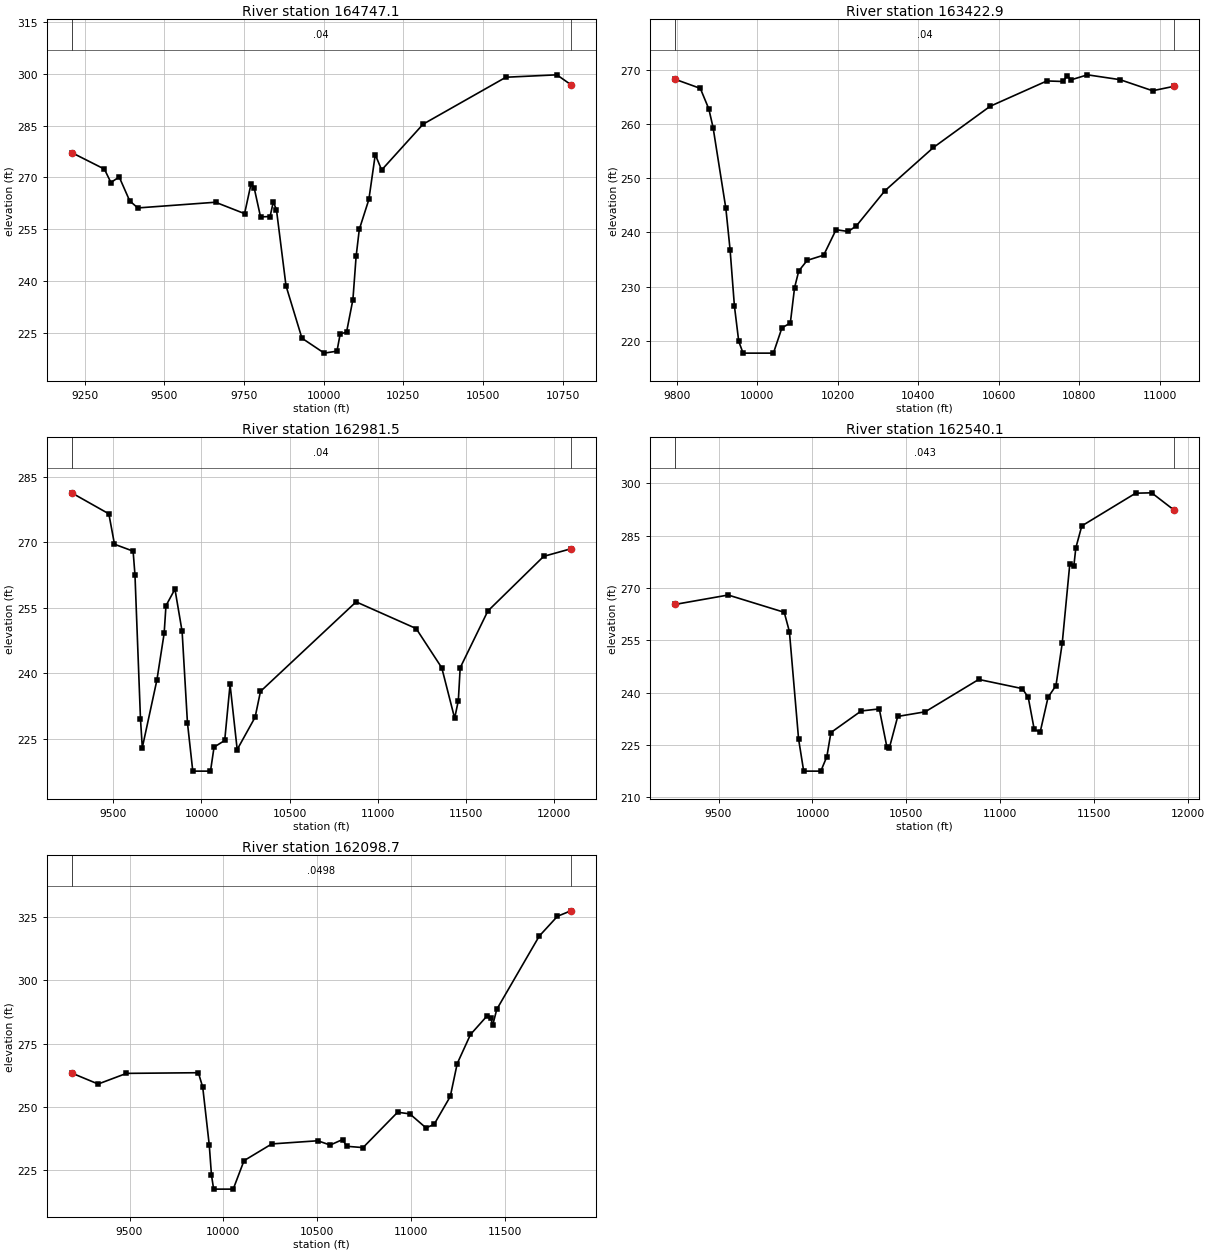
Type RM Length L Ch R = 1 ,164747.1,1324.182200,1324.182200,1324.182200
XS GIS Cut Line= 6
818805.101883281788184.221719363819063.257691592 788349.29590188
819111.005386144788417.838498399819133.310726166788483.323903039
819163.549749523789026.233796105819162.995939349789588.890043939
#Sta/Elev= 30
9208.763277.18479311.696272.39289331.967268.51239358.127270.11219391.173 263.177
9416.576261.14269660.481262.7938 9751.76259.4946  9771.8268.01149781.821266.9882
9801.847258.55969831.851258.64449841.852262.87229851.854260.63719881.858238.5765
9931.865223.403510001.87219.0763 10041.9219.6518 10051.9224.630310071.92 225.158
10091.93234.610110101.94247.075910111.96254.922710142.03263.603110162.08276.5977
10182.13272.137110312.27285.410810572.27299.011510732.28299.708710776.18296.8588
#Mann= 3 , 0 , 0
9208.763    0.04       09208.763    0.04       010776.18    0.04       0
#XS Ineff= 2 , 0
       0                               0
Bank Sta=9208.763,10776.18
Exp/Cntr=0.3,0.1

Type RM Length L Ch R = 1 ,163422.9,441.394100,441.394100,441.394100
XS GIS Cut Line= 6
817810.031132283788524.451680149 817853.84588299788661.819235596
817894.689073711788764.342877547817933.696441166788914.187838037
818008.056289569   789541.892502818040.143103584789737.756818695
#Sta/Elev= 30
9795.437 268.2519858.443  266.569879.583262.76189890.158259.33669921.883244.4217
9932.458236.75029943.099226.45489953.882  219.919964.664217.7476   10040217.7476
10061.17222.403610082.07223.306410092.52229.794510102.97 232.89510123.88234.8505
 10164.9235.8108 10195.6240.501510226.05240.175710246.28241.229410316.97247.6813
10437.63255.6681 10578.4263.260210719.34267.932210759.66267.832310769.75268.9168
10779.83268.144610820.15269.060710901.07268.169410982.06266.126211035.67266.9513
#Mann= 3 , 0 , 0
9795.437    0.04       09795.437    0.04       011035.67    0.04       0
#XS Ineff= 2 , 0
       0                               0
Bank Sta=9795.437,11035.67
Exp/Cntr=0.3,0.1

Type RM Length L Ch R = 1 ,162981.5,441.394000,441.394000,441.394000
XS GIS Cut Line= 6
817236.761045796788070.065295355817395.728724866788506.411384228
817498.317418793789130.452071808817688.958625978789940.523161688
817810.174864595790349.304559249817968.645989094790799.467462786
#Sta/Elev= 30
9262.832281.31079474.139276.49859506.093 269.5329611.879267.94799622.376262.5301
9653.702229.51089664.089222.93159746.972238.43719788.064249.12259798.337255.4438
9849.342259.24919890.021249.55049920.331228.6252 9950.61217.550810051.17217.5508
10071.28223.048210131.83224.576110162.19 237.40610202.65222.491510304.39229.8971
10334.92235.816110877.79256.3288 11218.6250.216211364.11241.221111437.17 229.663
11458.09233.718511468.56241.228611625.57254.230311942.72266.759112096.85268.4873
#Mann= 3 , 0 , 0
9262.832    0.04       09262.832    0.04       012096.85    0.04       0
#XS Ineff= 2 , 0
       09839.173        10748.81       0
Bank Sta=9262.832,12096.85
Exp/Cntr=0.3,0.1

Type RM Length L Ch R = 1 ,162540.1,441.394100,441.394100,441.394100
XS GIS Cut Line= 6
816717.150244115788263.408849464816952.154054524788734.468026714
 817141.82296971789203.865115218817274.565184885789574.664335521
817561.511529899790426.055274497817677.323886407790737.041297908
#Sta/Elev= 30
9268.052265.31299551.322268.00669849.648263.05799877.098257.52749925.951226.7565
9953.141217.550810044.38217.5508 10076.6221.735110098.07228.604410259.16 234.785
10355.45235.3749 10396.2224.412210408.79224.124210453.64233.222410599.87234.5462
10884.84243.820811116.72241.193811148.34238.668411179.95229.575711211.57228.6815
11253.73238.694111295.89242.066111329.21254.216811369.71277.034711390.89276.2211
11401.48281.488111433.25 287.80211719.94297.184111805.17297.2865 11925.1292.3133
#Mann= 3 , 0 , 0
9268.052   0.043       09268.052   0.043       0 11925.1   0.043       0
#XS Ineff= 2 , 0
       0                10778.82       0
Bank Sta=9268.052,11925.1
Exp/Cntr=0.3,0.1

Type RM Length L Ch R = 1 ,162098.7,441.394000,441.394000,441.394000
XS GIS Cut Line= 6
  816231.3364751788433.819781823816687.220183375789205.634512495
816764.643712943789346.768345874816850.236982463789517.715453884
817012.339448857789882.885016608817391.152637754 790820.98143418
#Sta/Elev= 30
 9191.47263.41249332.661259.06599483.675263.27249866.805263.53219890.025257.7684
9924.854234.89749936.464223.14439948.074 217.55210052.41 217.55210109.96228.7972
10258.05235.409810503.06236.654210569.08234.9598 10635.1237.147910656.91234.4746
10743.96233.954310928.29 247.921 10993.1247.285611079.51241.746511122.64243.1133
11208.83254.149711245.82  267.1311316.56278.631311402.75285.790111424.29285.0823
11435.07282.353811456.61 288.57411682.86317.494211779.82325.323611851.29327.4779
#Mann= 3 , 0 , 0
 9191.47  0.0498       0 9191.47  0.0498       011851.29  0.0498       0
#XS Ineff= 2 , 0
       0                10769.32       0
Bank Sta=9191.47,11851.29
Exp/Cntr=0.3,0.1