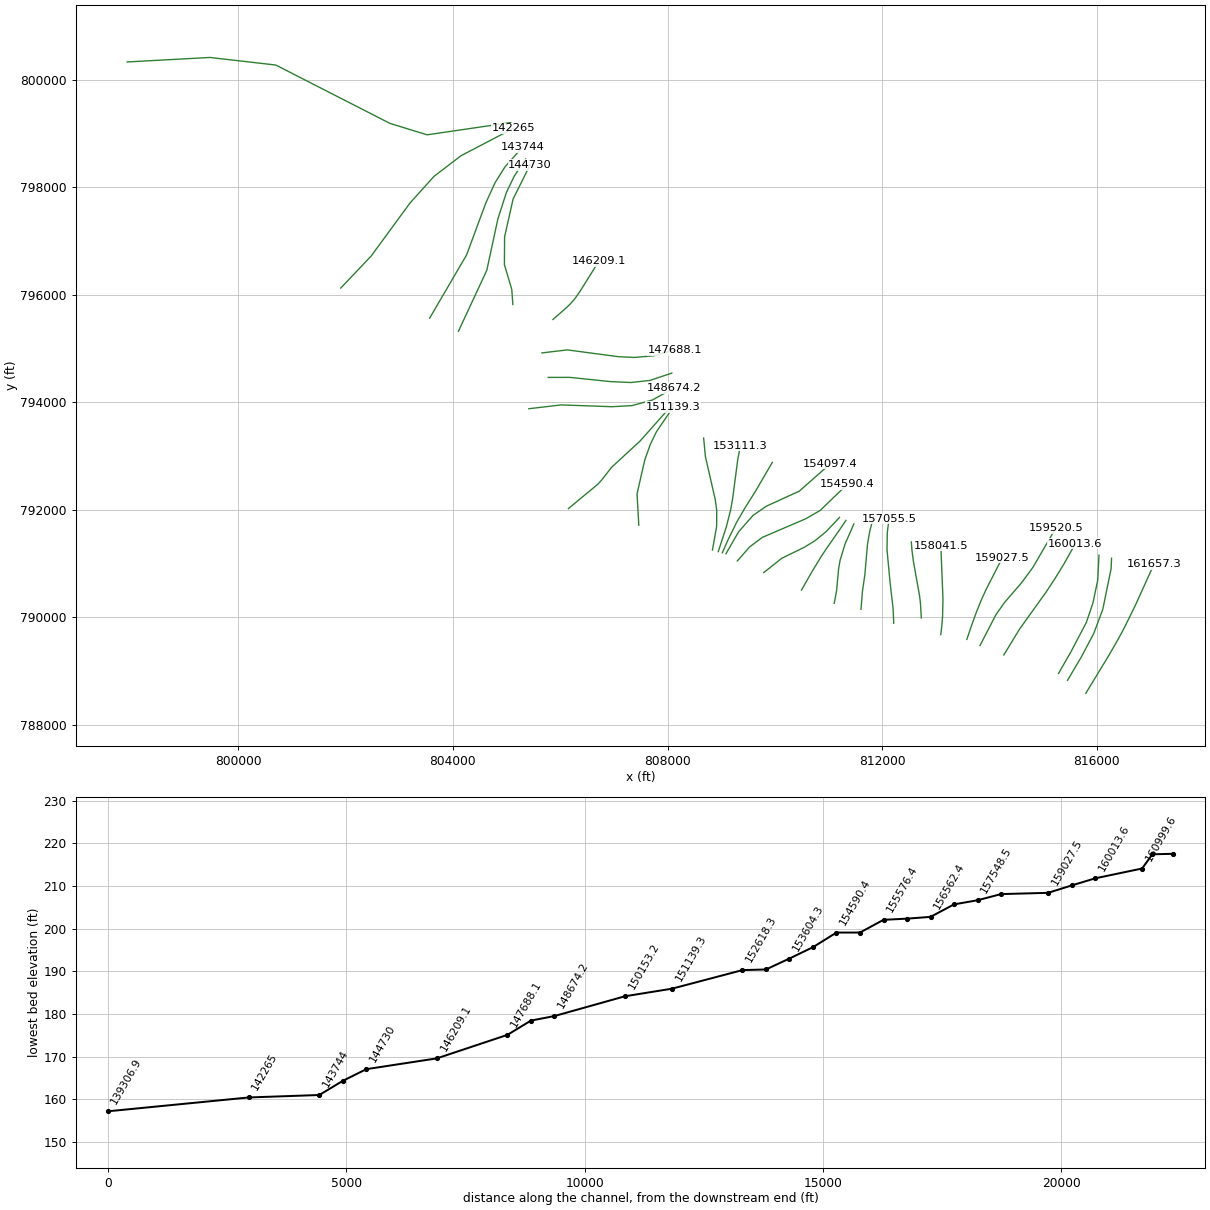
HEC-RAS study 17203_ras.prj: 17203

--- 17203_ras.g01 (geometry) --- (continued)

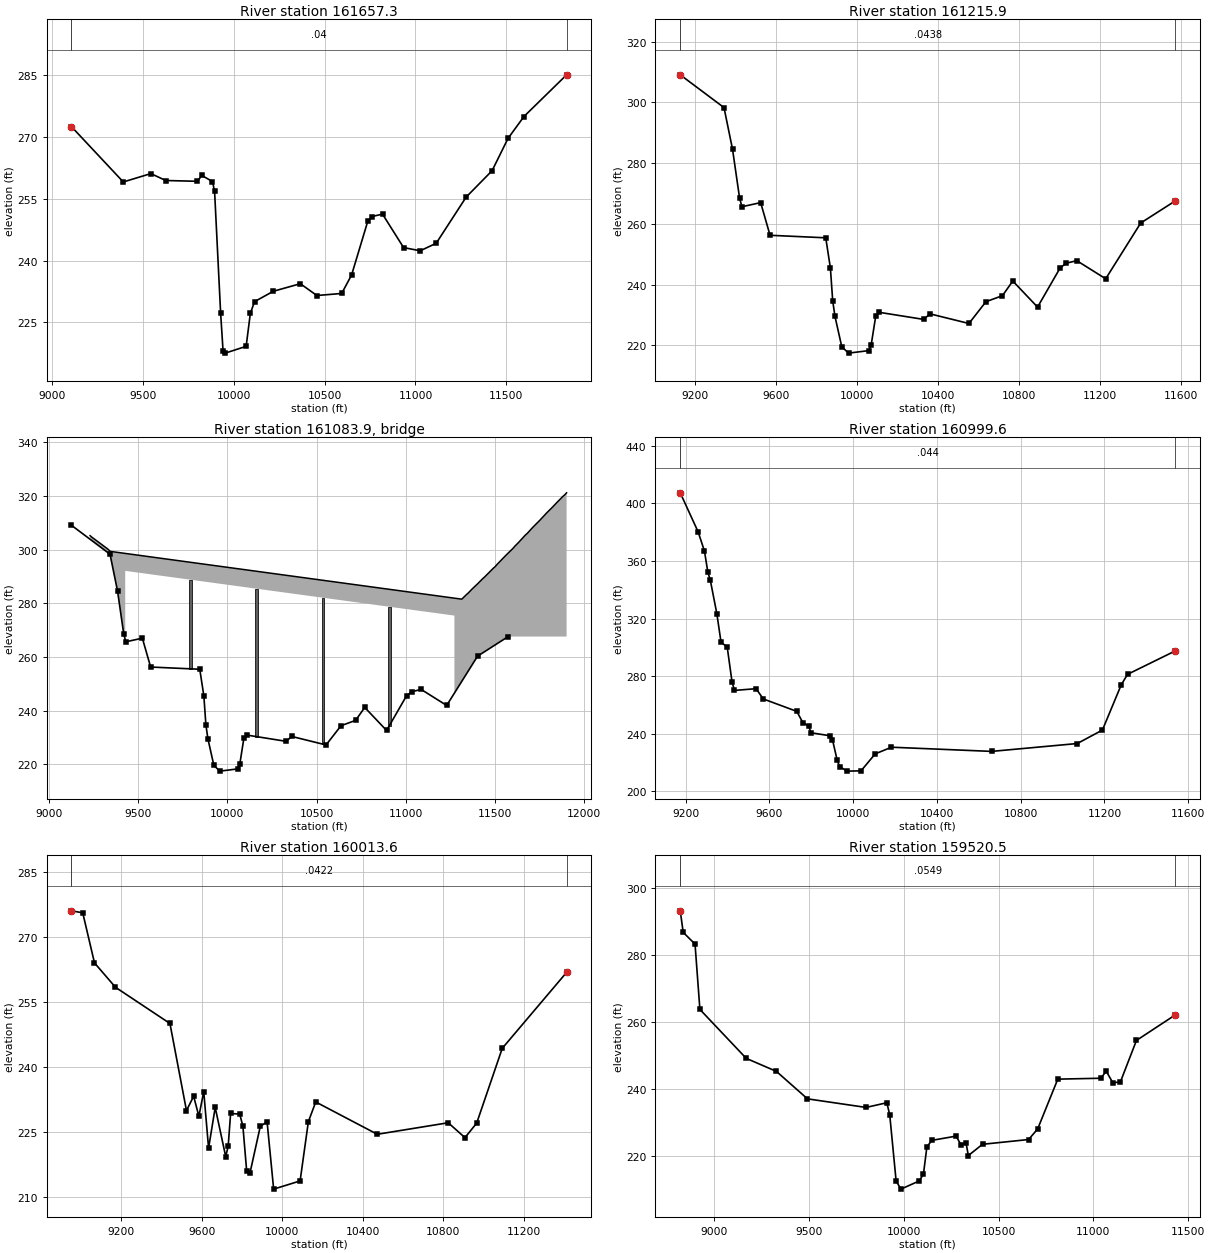
Type RM Length L Ch R = 1 ,161657.3,441.394000,441.394000,441.394000
XS GIS Cut Line= 6
815794.506229982788581.778413224816221.625961469789283.487177048
816394.426817999789583.394628934816514.407845208789805.413493256
  816719.5469931 790223.64005498817066.555402466 790989.05582997
#Sta/Elev= 30
9105.722272.47929391.166259.05879543.155261.08549624.995259.41139798.607259.2189
 9823.75260.63079882.208259.16179893.899256.79399927.205 227.2459940.544218.1003
 9952.13 217.55210067.66219.197610090.72227.171110113.77230.036310217.54232.5575
10366.09234.383910457.03231.523210593.68232.020210648.41236.5236   10738249.6376
10760.37250.670710818.48251.262110934.56243.140611026.05242.370511114.06244.1903
11279.07255.396911421.68261.782711509.43269.617711597.17 274.92511831.96285.0368
#Mann= 3 , 0 , 0
9105.722    0.04       09105.722    0.04       011831.96    0.04       0
#XS Ineff= 2 , 0
       0                               0
Bank Sta=9105.722,11831.96
Exp/Cntr=0.3,0.1

Type RM Length L Ch R = 1 ,161215.9,216.320600,216.320600,216.320600
XS GIS Cut Line= 6
815454.041612169788822.805501468815713.016746342789261.864973471
815943.102993071789696.692466095816111.156321496790145.195110127
816266.044292122 790902.79931435816274.158950315   791096.391874
#Sta/Elev= 30
9126.374309.10389342.744 298.3129384.955284.53899419.701268.52239431.284265.6566
 9523.94267.01079570.268 256.2519845.653255.4238 9868.67245.46049879.949234.7469
9891.163229.55579924.807219.5488 9958.45217.4405 10059.2218.276410070.39220.2112
10092.75229.634610110.08230.880710329.28228.552910361.32 230.36810553.54227.2012
10637.56234.378510719.22236.367310770.25241.191410892.73232.599511005.01245.5863
11035.63247.087111086.66 247.89311229.56241.929611402.64260.298811574.18267.6049
#Mann= 3 , 0 , 0
9126.374  0.0438       09126.374  0.0438       011574.18  0.0438       0
#XS Ineff= 2 , 0
       0                10808.36       0
Bank Sta=9126.374,11574.18
Exp/Cntr=0.3,0.1

Type RM Length L Ch R = 3 ,161083.9,,,
BEGIN DESCRIPTION:
END DESCRIPTION:
Bridge Culvert--1,0,-1,-1, 0
Deck Dist Width WeirC Skew NumUp NumDn MinLoCord MaxHiCord MaxSubmerge Is_Ogee
78.660300,59.000000,2.6,0, 32, 32, , , 0.95, 0, 0,0,,
 9230.97 9241.93 9329.13 9344.30 9427.87 9427.8711272.8711272.8711314.1411341.10
11351.1111371.1311401.1511431.1711441.1811491.2211501.2211511.2311561.2711601.30
11611.3111631.3211671.3511681.3611711.3811751.4111791.4411821.4711851.4911881.51
11891.5211901.65
  305.23  304.62  300.30  299.37  298.61  298.61  281.93  281.93  281.56  283.31
  283.89  285.29  287.17  289.18  289.77  293.11  293.67  294.46  297.90  300.50
  301.29  302.62  305.52  306.09  308.29  310.96  313.82  315.79  317.90  319.91
  320.48  321.20
 -694.77 -695.38 -699.70 -700.63 -701.39  292.11  275.43 -718.07 -718.44 -716.69
 -716.11 -714.71 -712.83 -710.82 -710.23 -706.89 -706.33 -705.54 -702.10 -699.50
 -698.71 -697.38 -694.48 -693.91 -691.71 -689.04 -686.18 -684.21 -682.10 -680.09
 -679.52 -678.80
 9230.97 9241.93 9329.13 9344.30 9407.29 9407.2911252.2911252.2911314.1411341.10
11351.1111371.1311401.1511431.1711441.1811491.2211501.2211511.2311561.2711601.30
11611.3111631.3211671.3511681.3611711.3811751.4111791.4411821.4711851.4911881.51
11891.5211901.65
  305.23  304.62  300.30  299.37  298.80  298.80  282.12  282.12  281.56  283.31
  283.89  285.29  287.17  289.18  289.77  293.11  293.67  294.46  297.90  300.50
  301.29  302.62  305.52  306.09  308.29  310.96  313.82  315.79  317.90  319.91
  320.48  321.20
 -694.77 -695.38 -699.70 -700.63 -701.20  292.30  275.62 -717.88 -718.44 -716.69
 -716.11 -714.71 -712.83 -710.82 -710.23 -706.89 -706.33 -705.54 -702.10 -699.50
 -698.71 -697.38 -694.48 -693.91 -691.71 -689.04 -686.18 -684.21 -682.10 -680.09
 -679.52 -678.80
Pier Skew, UpSta & Num, DnSta & Num=  ,9792.07, 2 ,9771.49, 2 , 0 , 0 , 0 ,,
   16.00   16.00
 -704.68  295.32
   16.00   16.00
 -704.49  295.51
Pier Skew, UpSta & Num, DnSta & Num=  ,10164.27, 2 ,10143.69, 2 , 0 , 0 , 0 ,,
   16.00   16.00
 -708.05  291.95
   16.00   16.00
 -707.86  292.14
Pier Skew, UpSta & Num, DnSta & Num=  ,10536.47, 2 ,10515.89, 2 , 0 , 0 , 0 ,,
   16.00   16.00
 -711.41  288.59
   16.00   16.00
 -711.22  288.78
Pier Skew, UpSta & Num, DnSta & Num=  ,10908.67, 2 ,10888.09, 2 , 0 , 0 , 0 ,,
   16.00   16.00
 -714.77  285.23
   16.00   16.00
 -714.59  285.41
BR Coef=-1 , 0 , 0 ,, 0 ,,,0.8,0,1,0,
WSPro=,,,, 1 ,,,, 0 ,,,, 0 ,,,,-1 ,-1 ,-1 , 0 , 0 , 0 , 0 , 0
BC Design=,, 0 ,, 0 ,,,,,,

Type RM Length L Ch R = 1 ,160999.6,986.033300,986.033300,986.033300
XS GIS Cut Line= 6
815286.153423064788951.447100935815516.683130751789352.386711347
815804.340126455 789900.35272184815926.503054112790260.178072423
816017.569963813790693.301179603 816039.78140521791153.078016475
#Sta/Elev= 30
9174.619407.32019260.038380.23249290.354366.82229306.491352.16999318.104346.7624
9349.355323.44349369.423 303.6049398.933300.21639421.904276.0835 9433.39270.1387
 9536.76271.33839571.217264.20619731.006255.59259759.915247.83979787.823245.3126
9799.187240.74039890.094238.64899901.458 235.9649924.185221.54049935.548217.2958
9970.465 214.10510037.93214.297510105.41226.078610183.35230.708810661.48 227.806
11070.23233.257411190.54242.628311280.64274.140311310.68281.317811539.02297.6199
#Mann= 3 , 0 , 0
9174.619   0.044       09174.619   0.044       011539.02   0.044       0
#XS Ineff= 2 , 0
       0                10800.54       0
Bank Sta=9174.619,11539.02
Exp/Cntr=0.3,0.1

Type RM Length L Ch R = 1 ,160013.6,493.016700,493.016700,493.016700
XS GIS Cut Line= 6
814266.927035011789295.839526224814560.832244749789777.710786818
  815053.6668127  790465.0287025815232.382506825790737.017197975
815384.708494069790986.071057262815598.312972594791363.906679578
#Sta/Elev= 30
 8951.46276.07239007.633275.6189 9066.15264.04279170.418258.41689441.298250.0537
9523.451229.94079559.175233.25089585.147228.60729609.284234.33239633.421221.2535
9666.347 230.6689718.506219.31789730.724221.65159742.942229.2695 9788.25229.1151
9804.032226.31499822.763215.97499839.667215.61979890.379226.27259924.187227.3835
9956.932211.792910088.46213.689910129.52227.384910166.21231.924710472.16 224.461
10824.88227.121310908.06223.685510966.43227.042211093.49244.315911413.42261.8546
#Mann= 3 , 0 , 0
 8951.46  0.0422       0 8951.46  0.0422       011413.42  0.0422       0
#XS Ineff= 2 , 0
       09810.301        10672.35       0
Bank Sta=8951.46,11413.42
Exp/Cntr=0.3,0.1

Type RM Length L Ch R = 1 ,159520.5,493.016600,493.016600,493.016600
XS GIS Cut Line= 6
813822.756872837789470.711608645814119.604721093790044.532943685
814282.683784576790276.216570469814591.000492794790630.779640344
814809.199010093790926.930973746 815233.52606884791655.736202611
#Sta/Elev= 30
8821.101293.26368836.715286.83368899.148283.3144 8924.77263.81479169.266249.1832
9328.423245.29299492.168237.09259801.111234.52669910.773235.9291 9926.01232.3442
 9959.71212.56419985.063210.119710081.57212.568410103.92214.626510122.09222.7646
10148.37224.693610275.95225.953610303.03223.260710328.27223.954910340.73220.1547
10415.49223.514710658.55224.938910706.31 228.10610812.39242.978811040.05243.2499
11067.64245.381811102.07241.960811142.17242.075311227.34 254.54511432.83262.1923
#Mann= 3 , 0 , 0
8821.101  0.0549       08821.101  0.0549       011432.83  0.0549       0
#XS Ineff= 2 , 0
       09816.018         10537.9       0
Bank Sta=8821.101,11432.83
Exp/Cntr=0.3,0.1

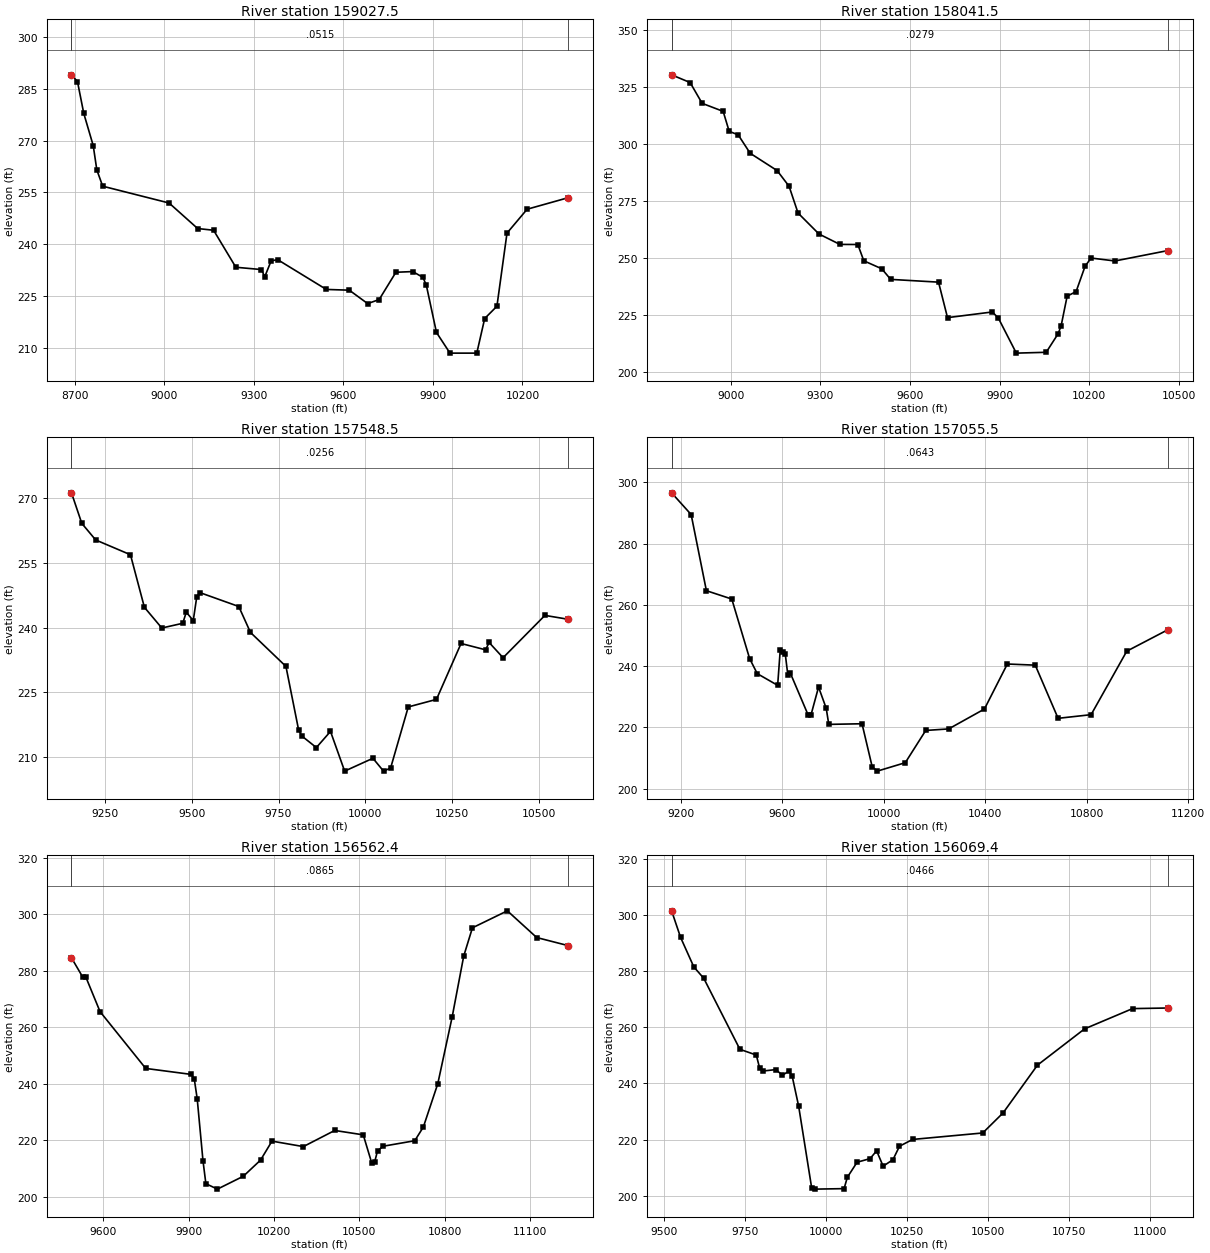
Type RM Length L Ch R = 1 ,159027.5,986.033300,986.033300,986.033300
XS GIS Cut Line= 6
813578.018657274789585.945471255813666.059158959789845.329145279
813753.955114879790087.332425002813846.059439332790316.044049028
813942.545996028790526.335137533814240.330950944791106.973955974
#Sta/Elev= 30
8689.745289.08718709.823287.13048730.897277.90168762.551268.56058774.663261.5002
8794.251256.7973 9016.51251.92519112.262244.52259165.611244.0246 9240.11233.2948
9326.031232.62599336.771230.50999358.269235.12939379.931235.50969543.187 226.863
9620.054226.64899681.582222.75419720.031223.93649776.105231.84379832.573232.0452
9866.567230.36089877.898228.11959911.892214.39219957.217208.398510046.97208.3985
 10073.4218.434110114.39221.9931 10148.1243.199610215.52250.122110351.68253.4296
#Mann= 3 , 0 , 0
8689.745  0.0515       08689.745  0.0515       010351.68  0.0515       0
#XS Ineff= 2 , 0
       09771.313        10258.84       0
Bank Sta=8689.745,10351.68
Exp/Cntr=0.3,0.1

Type RM Length L Ch R = 1 ,158041.5,493.016700,493.016700,493.016700
XS GIS Cut Line= 6
813092.023539683789673.580316987813111.105173819789834.414664971
813125.508219879790013.517960633813133.034912807790337.725433928
 813099.59837894791161.425614603813096.771971937791332.154182109
#Sta/Elev= 30
8801.695330.32348863.643 326.9348903.888317.80278974.294314.27058994.374305.5075
9024.495 303.9769064.646 295.8789154.849288.27189194.886281.37559224.914269.6195
9294.977260.41539364.978255.8501 9424.98255.8034 9444.98248.65219504.996245.1502
9535.009240.48629695.128239.27389725.167223.68569875.364226.1826 9895.39223.4804
9955.446208.101910055.52208.470210095.55 216.64910105.55220.178110125.57233.1136
10155.59235.128810185.61246.249410205.63249.861610285.68248.577110462.87253.1481
#Mann= 3 , 0 , 0
8801.695  0.0279       08801.695  0.0279       010462.87  0.0279       0
#XS Ineff= 2 , 0
       0                               0
Bank Sta=8801.695,10462.87
Exp/Cntr=0.3,0.1

Type RM Length L Ch R = 1 ,157548.5,493.016600,493.016600,493.016600
XS GIS Cut Line= 6
812729.436858577789985.333348196812714.245921016790245.802356631
812698.004513949790390.224364877812580.896861553791045.831463277
812553.569255799 791257.50031276812543.817759246791400.764693007
#Sta/Elev= 30
 9153.63271.29029183.322264.19589223.356260.34389323.509256.91369363.629244.7041
9413.779239.89369474.154240.99399484.217243.57299504.343241.62619514.406247.1073
9524.469248.08979635.469244.89079669.109238.86969771.297230.97789807.972216.1485
9818.157214.74259858.894212.13219899.631215.88389940.368206.659710021.84209.6441
 10052.4206.659710072.76207.380710123.61221.568310204.84223.322710275.65236.3013
10346.35234.831210356.44236.5332 10396.7232.9961 10517.2242.826210583.06 241.941
#Mann= 3 , 0 , 0
 9153.63  0.0256       0 9153.63  0.0256       010583.06  0.0256       0
#XS Ineff= 2 , 0
       0                 10333.2       0
Bank Sta=9153.63,10583.06
Exp/Cntr=0.3,0.1

Type RM Length L Ch R = 1 ,157055.5,493.016600,493.016600,493.016600
XS GIS Cut Line= 6
812215.169559062789887.958310366812204.099650204790156.507345855
812148.619333744790633.207894057812090.414638937791250.503702775
812095.569643348791574.640160039812128.092492014791835.568326786
#Sta/Elev= 30
9163.338296.58969240.385289.49699300.465264.62299400.613261.89659470.843242.4592
9500.986237.52749581.368233.71429591.415245.10439601.463244.7446 9611.52243.8348
9621.601237.01929631.681  237.649702.246223.88949712.326223.90649742.568233.1498
 9772.81226.19929782.891220.96179913.931221.16399954.077207.0887 9974.15205.6905
10084.54208.450310165.03218.975810255.62219.482210396.45225.9761 10486.7240.6782
 10596.8240.302510686.82222.938510816.93224.129810957.48244.868611119.69251.8804
#Mann= 3 , 0 , 0
9163.338  0.0643       09163.338  0.0643       011119.69  0.0643       0
#XS Ineff= 2 , 0
       0                10515.15       0
Bank Sta=9163.338,11119.69
Exp/Cntr=0.3,0.1

Type RM Length L Ch R = 1 ,156562.4,493.016700,493.016700,493.016700
XS GIS Cut Line= 6
811605.491361842790144.895568684811631.824498087790474.929032594
811677.711152911790792.957733765811726.717112929 791357.98250179
811766.604585767791588.582113951811838.862511933 791870.17704235
#Sta/Elev= 30
9488.428284.6319 9528.66277.70549538.692277.88819588.851265.59079749.359245.4859
9910.237243.36189920.309241.57389930.436234.67719950.702 212.7729960.834204.6857
10001.36202.759410092.52207.322510152.99213.031410193.16219.7504 10303.5217.8144
10413.78223.529210514.04221.973110544.16211.899310554.22212.418710564.28216.3423
 10584.4217.956710695.07  219.8910725.36224.769210775.99240.065710826.62263.7411
10867.19285.270210897.77295.262211020.54301.276911123.67291.823211232.99288.9924
#Mann= 3 , 0 , 0
9488.428  0.0865       09488.428  0.0865       011232.99  0.0865       0
#XS Ineff= 2 , 0
       0                10635.74       0
Bank Sta=9488.428,11232.99
Exp/Cntr=0.3,0.1

Type RM Length L Ch R = 1 ,156069.4,493.016600,493.016600,493.016600
XS GIS Cut Line= 6
811107.096679568790257.726903081811150.837520748790493.624162287
811188.247478992790899.409840941811215.645865619791057.604150787
811306.586374968791356.805004194811472.283717785791733.411289183
#Sta/Elev= 30
9522.687301.41219550.522291.91979591.345281.43879621.962277.40029733.597252.1138
9784.193250.07659794.278245.55029804.363244.38069844.702244.8965 9864.86242.8927
9884.941244.35219894.982242.59219915.063 231.8629955.194202.81469965.213202.3441
10055.39202.521210065.41206.555110095.49211.9188 10135.7 213.207 10155.8215.9858
10175.93210.512610206.26212.821210226.48 217.61910267.07220.0319 10483.5222.3347
10546.45229.484510652.62246.488310798.08259.390610946.18266.603211055.42266.8212
#Mann= 3 , 0 , 0
9522.687  0.0466       09522.687  0.0466       011055.42  0.0466       0
#XS Ineff= 2 , 0
       0                               0
Bank Sta=9522.687,11055.42
Exp/Cntr=0.3,0.1

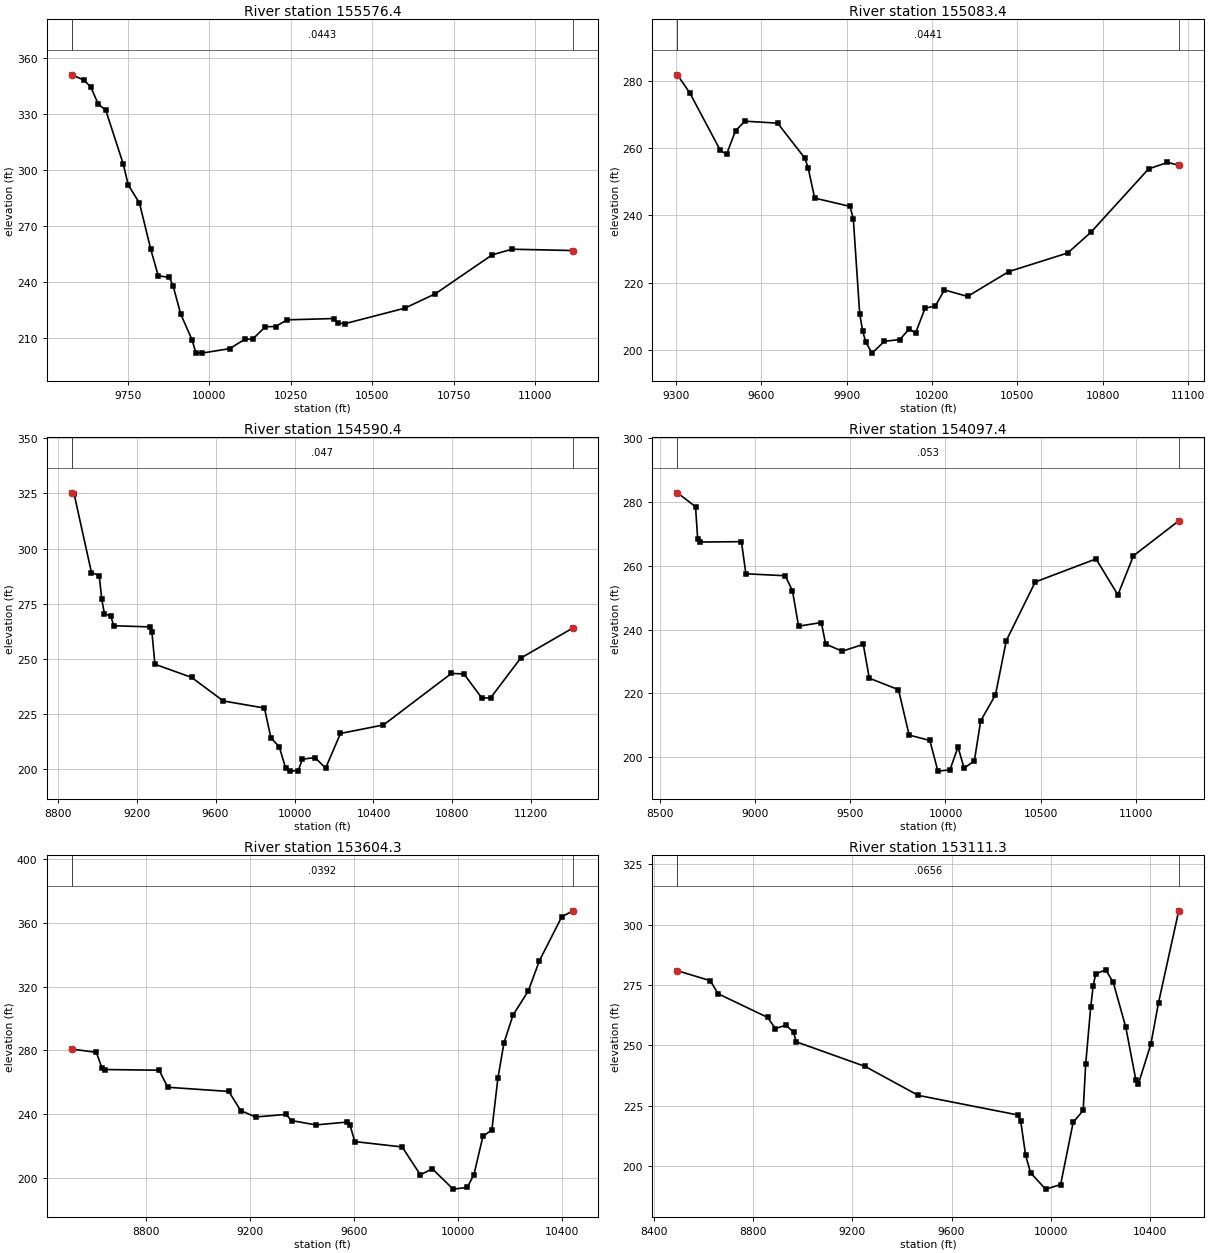
Type RM Length L Ch R = 1 ,155576.4,493.016700,493.016700,493.016700
XS GIS Cut Line= 6
810496.690782934790504.323104158810706.199910372790870.000393137
810863.236910105791127.818471581810964.951616317791280.054879814
811227.104671299791655.887845472811324.480396284791800.687283792
#Sta/Elev= 30
9577.555351.20379614.499348.44599635.901344.72649658.928335.49089681.954332.2709
9735.568303.47999751.034 292.1999785.574282.44499820.114 257.7449843.141243.5151
9877.681242.62119889.194237.81599912.248222.93979946.949209.17769958.515202.3659
9976.715202.0665 10062.9204.484710109.37209.559910132.67209.477110171.78216.2007
10203.34216.323410238.68219.900210381.69220.604410393.72218.150810417.77217.9202
10599.75226.136110693.83233.866110867.98254.702410928.94257.754211116.71257.0361
#Mann= 3 , 0 , 0
9577.555  0.0443       09577.555  0.0443       011116.71  0.0443       0
#XS Ineff= 2 , 0
       0                               0
Bank Sta=9577.555,11116.71
Exp/Cntr=0.3,0.1

Type RM Length L Ch R = 1 ,155083.4,493.016600,493.016600,493.016600
XS GIS Cut Line= 6
809793.395222992790829.243658423810130.719585598791096.520710975
810552.046616644791302.034253344810751.259150803791424.950285569
810958.670823991791594.500493109811204.643447727791855.233756925
#Sta/Elev= 30
9305.373281.76649349.199276.35339456.256 259.307 9478.07258.15549510.072 265.214
9542.902267.98789657.541267.41089753.058 257.0199764.593254.18659787.663245.1453
9912.314242.66389923.453238.94779945.849210.84469956.511205.5453 9967.41202.3473
9989.209 199.08110032.66202.587610086.99203.115110119.98206.291510141.99 205.016
10175.56212.413110211.96213.116110243.48217.857910324.82215.927610469.72223.3073
10676.63228.8347 10758.3234.987810960.72253.795911027.34255.747711066.81254.9179
#Mann= 3 , 0 , 0
9305.373  0.0441       09305.373  0.0441       011066.81  0.0441       0
#XS Ineff= 2 , 0
       0                               0
Bank Sta=9305.373,11066.81
Exp/Cntr=0.3,0.1

Type RM Length L Ch R = 1 ,154590.4,493.016600,493.016600,493.016600
XS GIS Cut Line= 6
809300.379214615791045.736203879809531.345008224791307.723217621
809766.813719422791484.425073311 810578.40663144791832.365815356
810844.900654852791986.113812834811349.303540754792472.402938893
#Sta/Elev= 30
8871.349325.25728883.001324.8789 8971.34289.08879010.588 287.7529023.671276.9228
9036.754270.49759069.421269.34199084.072 264.9919265.929264.47469277.636261.9862
9292.844247.53989478.483241.57419639.469230.87859847.702227.68759880.073214.2272
9922.809210.11289954.834200.47629976.184 199.08110018.84199.331910040.15204.5059
10104.08205.237210157.63200.427910232.93216.1678 10450.6220.008910794.95243.3839
10858.41243.138710948.77232.260110993.06232.241711145.26250.2664 11411.3264.0224
#Mann= 3 , 0 , 0
8871.349   0.047       08871.349   0.047       0 11411.3   0.047       0
#XS Ineff= 2 , 0
       0                               0
Bank Sta=8871.349,11411.3
Exp/Cntr=0.3,0.1

Type RM Length L Ch R = 1 ,154097.4,493.016700,493.016700,493.016700
XS GIS Cut Line= 6
809088.987822755791180.023086603809322.540868133791584.908321545
809592.191629976791892.350814044809843.245604664 792065.99584499
810455.138064504792345.072840959811037.311992973792858.110839456
#Sta/Elev= 30
8590.024282.86648685.435278.51718696.758268.39238708.081267.44938926.796267.5585
8950.241257.49649157.218256.87989195.315252.15169227.217241.06929347.048 242.218
9369.644235.45899456.864233.2313 9567.62235.38869599.276224.77529752.772221.1812
9808.838206.94129917.711205.26579960.085195.651210023.48196.053510065.87 203.198
10097.88196.564910151.96 198.90910184.98211.391910262.96219.585410319.92236.5643
10472.07254.932610791.64262.156310906.61250.885610988.66263.152511226.61274.0761
#Mann= 3 , 0 , 0
8590.024   0.053       08590.024   0.053       011226.61   0.053       0
#XS Ineff= 2 , 0
       0                               0
Bank Sta=8590.024,11226.61
Exp/Cntr=0.3,0.1

Type RM Length L Ch R = 1 ,153604.3,493.016600,493.016600,493.016600
XS GIS Cut Line= 6
809021.966966531791198.528845413809122.143116593 791426.83663708
 809288.62231189791766.435529515809451.792043656792046.696225554
809636.211188525 792338.35057953809953.319195658792881.589206293
#Sta/Elev= 30
8515.772280.82348610.063278.80628631.923269.01678642.853268.0008  8851.5267.5735
8884.664256.88599119.274254.2492  9164.6242.3053 9221.82238.22219338.577239.8476
9360.563 235.9649454.039233.27139572.541235.03019584.413233.3611 9603.53222.8093
9785.347219.44059855.117201.99429901.226205.72359981.074192.993710035.26194.0487
10061.12202.121210095.45226.085710129.91230.127410153.21262.7113 10176.5284.7384
10211.45302.240910269.69317.2102 10312.8336.320610398.77363.855310441.93367.5417
#Mann= 3 , 0 , 0
8515.772  0.0392       08515.772  0.0392       010441.93  0.0392       0
#XS Ineff= 2 , 0
       0                               0
Bank Sta=8515.772,10441.93
Exp/Cntr=0.3,0.1

Type RM Length L Ch R = 1 ,153111.3,493.016700,493.016700,493.016700
XS GIS Cut Line= 6
 808945.43880203791219.659756508809092.548275173791668.003141776
809173.609937996791984.073358074809213.321463048792204.653258368
809308.688454539792931.542970344809358.289291114793194.781144068
#Sta/Elev= 30
8493.569280.86968626.228276.73968657.878271.33558857.639261.5391 8889.05256.9128
 8930.93258.31238962.341255.4935 8972.76251.44749251.813241.21079465.703229.2451
9868.897221.11129878.962 218.7899899.122204.44819919.289197.15689979.792190.4196
10040.42192.292110090.96 218.073 10131.4223.0138 10141.5242.106410161.72265.6947
10171.83274.687210181.94279.503510222.37281.272410252.71276.055910303.48257.4362
 10344.1235.579910354.26233.980610405.03250.649510435.52 267.631 10517.1305.6752
#Mann= 3 , 0 , 0
8493.569  0.0656       08493.569  0.0656       0 10517.1  0.0656       0
#XS Ineff= 2 , 0
       0                               0
Bank Sta=8493.569,10517.1
Exp/Cntr=0.3,0.1

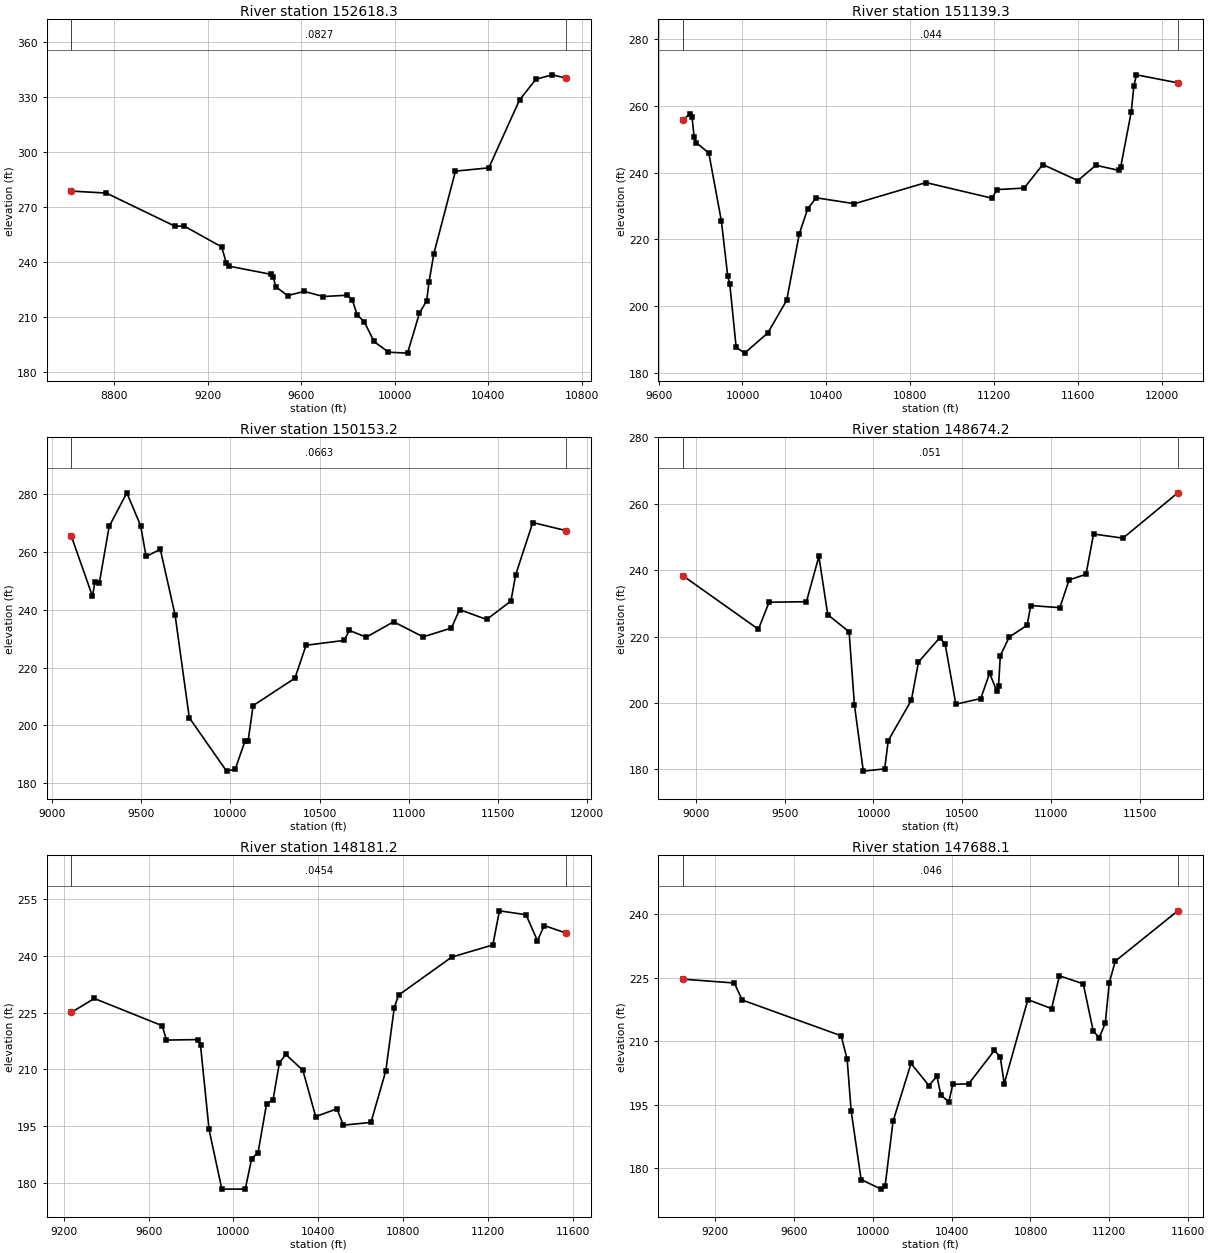
Type RM Length L Ch R = 1 ,152618.3,1479.049900,1479.049900,1479.049900
XS GIS Cut Line= 6
808837.093247861 791249.57606627 808915.02635029 791683.65864788
808917.701444924791981.689349756808890.684252173792183.571418941
808706.667752802792987.554870054808673.398714823793334.130577557
#Sta/Elev= 30
8616.322278.56938765.659277.50319059.151259.45289099.241259.50459259.368248.1461
9279.371239.32469289.372237.68959470.167233.22759480.303231.86079490.439226.5119
9541.118221.6304 9612.62 223.8949694.565 221.1259797.821 221.827 9818.48219.2093
9839.139211.19679870.128207.20999911.446 196.613 9973.08190.778410054.69 190.273
 10105.9212.094910136.66218.807310146.92229.266310167.42244.474310259.71289.4492
10402.57291.234610533.88328.188810604.18339.539210674.33341.931410733.49340.1272
#Mann= 3 , 0 , 0
8616.322  0.0827       08616.322  0.0827       010733.49  0.0827       0
#XS Ineff= 2 , 0
       0                               0
Bank Sta=8616.322,10733.49
Exp/Cntr=0.3,0.1

Type RM Length L Ch R = 1 ,151139.3,986.033300,986.033300,986.033300
XS GIS Cut Line= 6
807464.643952936791712.273345217807432.569910318792294.679178357
807574.374378145792919.081525087807678.189376265793212.689899847
807792.710141361793449.434758529808107.604989704793912.335034967
#Sta/Elev= 30
9716.622255.84599749.367257.53269759.368256.59119769.369250.57119779.369248.9468
 9839.38  245.869899.476225.4621 9929.59209.0149 9939.64206.5456 9969.79187.6895
 10010.2185.913810120.97191.963610211.14201.761910271.17221.662510311.23229.1468
10351.43232.4377 10534.5230.662910875.55236.996311191.74232.300111213.23234.8866
11343.95235.342911433.05242.400611600.18237.5988 11686.3242.180111794.29240.6763
11804.82 241.68711855.01258.118511867.42265.886811879.83269.268712077.32266.8641
#Mann= 3 , 0 , 0
9716.622   0.044       09716.622   0.044       012077.32   0.044       0
#XS Ineff= 2 , 0
       0                               0
Bank Sta=9716.622,12077.32
Exp/Cntr=0.3,0.1

Type RM Length L Ch R = 1 ,150153.2,1479.049900,1479.049900,1479.049900
XS GIS Cut Line= 6
806153.760362754792021.155048931 806701.04936263792473.579357684
806769.720229477792548.164048046806957.877987385792789.340280384
807484.418026894  793273.7021496808109.645182461793976.805125996
#Sta/Elev= 30
9108.366 265.4679226.576244.68359240.418249.63839265.106249.3498  9320.1268.8691
9419.226280.52369496.285 269.1989527.271258.47459606.952260.96629689.793238.2114
9769.478202.6263 9978.49184.135510027.33184.856310082.41194.648510099.05194.4409
10127.47206.821110361.85216.325210424.29227.733710637.42229.397310667.39232.8728
10761.61230.5271 10915.2 235.85611081.12230.638611239.54 233.69711285.19240.0641
11437.36236.663411573.24243.031211599.78252.127511695.78270.232411882.93267.4273
#Mann= 3 , 0 , 0
9108.366  0.0663       09108.366  0.0663       011882.93  0.0663       0
#XS Ineff= 2 , 0
       0                               0
Bank Sta=9108.366,11882.93
Exp/Cntr=0.3,0.1

Type RM Length L Ch R = 1 ,148674.2,493.016600,493.016600,493.016600
XS GIS Cut Line= 6
805416.236038831793879.935316615806019.693078488793950.961198106
806965.597522348793917.294035882807337.294702411 793937.84378463
807719.442217439794042.274297342808118.795043886794265.940745279
#Sta/Elev= 30
8928.594238.28099352.403222.20049412.547230.34239622.643230.49379692.654244.1196
9742.667226.59579862.731221.43669892.754199.39959942.793179.494410062.91180.1711
10082.94188.670310213.11 200.86510253.17212.339610373.33219.689810403.37217.6495
10463.39199.636210603.41201.350910653.45208.965910693.49203.5868 10703.5205.0887
10713.52214.2528 10763.7219.847810864.46223.420110884.76 229.34211048.45228.7021
11100.58237.045611195.68238.759711238.35250.874711403.57249.624811712.35263.2723
#Mann= 3 , 0 , 0
8928.594   0.051       08928.594   0.051       011712.35   0.051       0
#XS Ineff= 2 , 0
       0                10377.09       0
Bank Sta=8928.594,11712.35
Exp/Cntr=0.3,0.1

Type RM Length L Ch R = 1 ,148181.2,493.016700,493.016700,493.016700
XS GIS Cut Line= 6
  805777.1853064794462.901054442806178.000689775794463.719266564
806937.095975459794384.808084816807315.182185769794367.673127845
807673.572456777794407.042677656808079.822573404794543.207212464
#Sta/Elev= 30
 9235.72225.04919343.722228.70859664.018221.52079684.087217.7379 9834.73217.8668
 9844.78216.31049884.978194.15729945.275178.426810055.78178.433910085.97186.4702
10116.17188.066810156.44200.971110186.64201.945610216.85211.747510247.05213.9581
10327.59209.751610387.99197.558310488.38199.611810518.48195.296510648.67196.0256
10718.67209.616810758.67226.286910778.67229.578611029.65239.623511223.61242.8326
11254.47251.822211380.18250.793211433.83243.937411466.02247.928911569.31245.9507
#Mann= 3 , 0 , 0
 9235.72  0.0454       0 9235.72  0.0454       011569.31  0.0454       0
#XS Ineff= 2 , 0
       0                10270.19       0
Bank Sta=9235.72,11569.31
Exp/Cntr=0.3,0.1

Type RM Length L Ch R = 1 ,147688.1,1479.049900,1479.049900,1479.049900
XS GIS Cut Line= 6
805660.234431565794919.290729359806133.544032246794975.026424453
807091.099945515794848.202121913807384.481772482794834.706100315
807742.578015387794865.641035065808138.643979637794974.564191507
#Sta/Elev= 30
9037.384224.70879297.214223.80669337.349219.7865 9839.32211.33019869.688205.8293
9889.943193.64249940.582177.343610041.88175.080410062.15175.711110102.69191.1227
10193.87204.781210284.84199.559310325.27201.777210345.42197.283610385.69195.7059
10405.82199.858910486.33199.963710616.67207.862810646.69206.318710666.71199.9881
10786.75219.879110906.86217.755210946.95225.513411067.73223.607111118.26212.4561
11148.69210.886311179.27  214.2511199.66223.874511230.25228.975311547.46240.8674
#Mann= 3 , 0 , 0
9037.384   0.046       09037.384   0.046       011547.46   0.046       0
#XS Ineff= 2 , 0
       0                10253.48       0
Bank Sta=9037.384,11547.46
Exp/Cntr=0.3,0.1

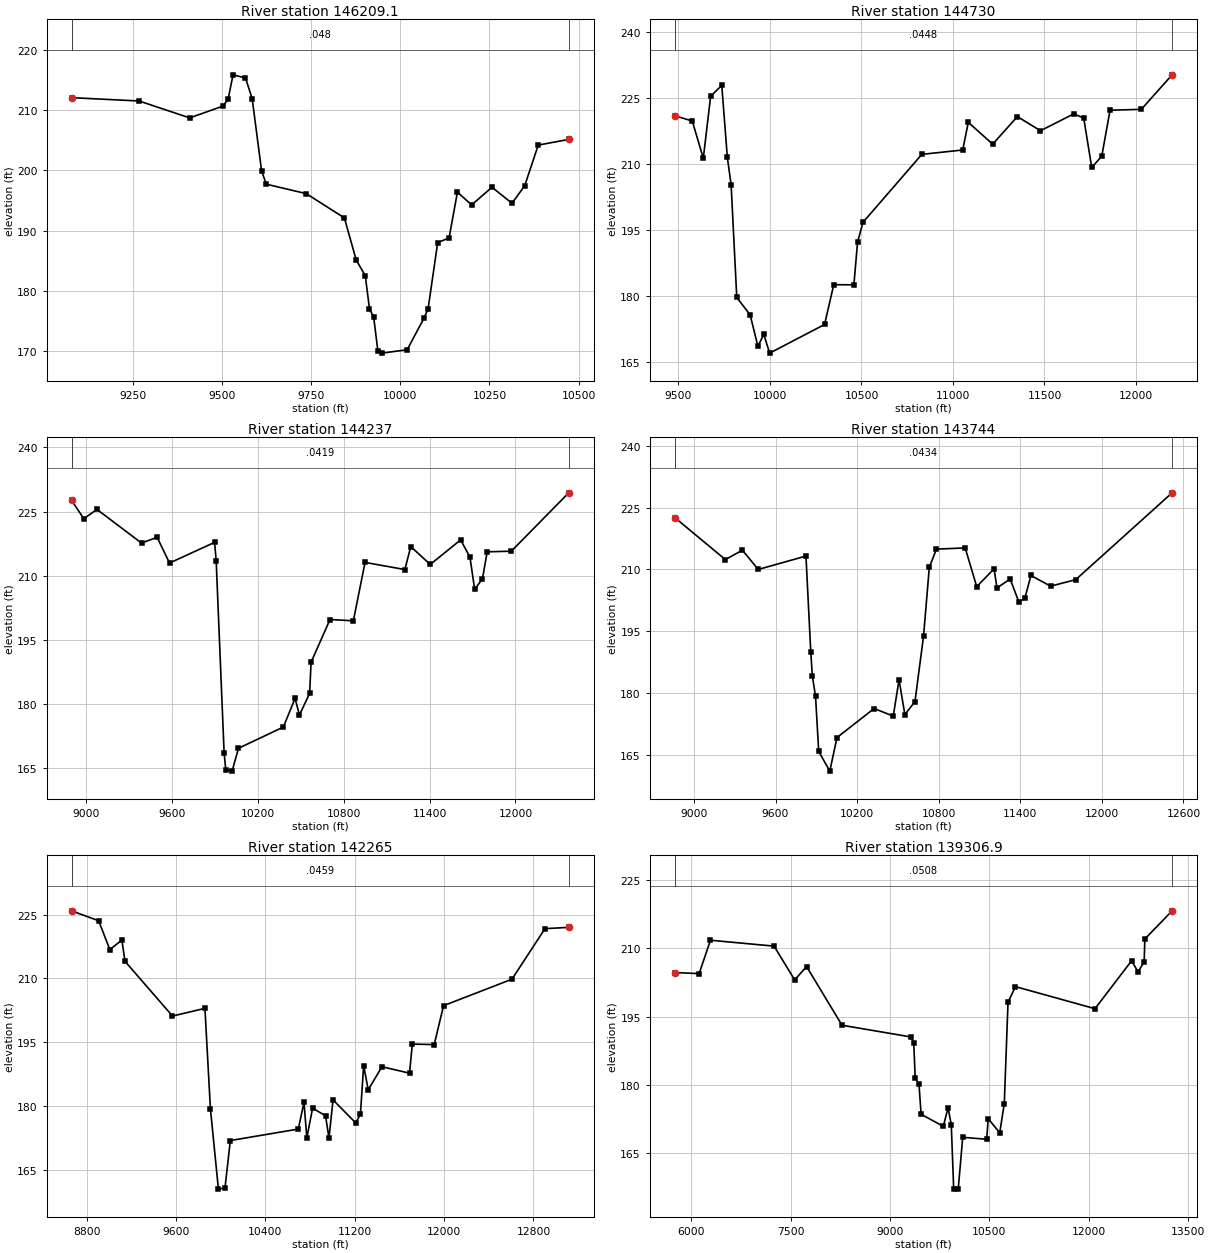
Type RM Length L Ch R = 1 ,146209.1,1479.049900,1479.049900,1479.049900
XS GIS Cut Line= 6
805865.106443241795541.561329449 806119.31525737795763.212067202
 806191.51534462795834.441107497806270.905505776795924.532481775
806371.847884327796069.386273876806722.355604427796628.082289539
#Sta/Elev= 30
9077.319212.13519266.925211.58179408.836208.76139502.593210.7397  9516.8211.9322
 9530.47215.94059565.411215.4209 9584.18211.96739610.469199.98759623.613197.7184
9735.982196.14189842.868192.10319876.001 185.0859901.591182.45929913.336176.9208
9925.081175.58319936.825169.9339 9948.57169.568610019.06170.134210066.07175.3888
10077.82176.971210104.64187.986910136.57188.759210160.07196.395310199.84194.2661
10256.97 197.20710313.26194.538610348.96197.484210386.81204.234410472.39205.1779
#Mann= 3 , 0 , 0
9077.319   0.048       09077.319   0.048       010472.39   0.048       0
#XS Ineff= 2 , 0
       0                10210.68       0
Bank Sta=9077.319,10472.39
Exp/Cntr=0.3,0.1

Type RM Length L Ch R = 1 ,  144730,493.016700,493.016700,493.016700
XS GIS Cut Line= 6
805118.301242819795819.991147183805098.231250197 796100.37798062
804960.799625993796561.156766728804963.946701407797079.454281121
805122.848984957797784.116581246805438.837943226798417.377389073
#Sta/Elev= 30
9480.523220.90549575.561219.70769635.684211.26199675.887225.32519736.618227.8188
9767.108211.46189787.719205.23659818.635179.66359891.615175.73279934.137168.5842
9966.181171.31589998.224167.038410298.26173.5352 10348.5182.566310458.59182.5377
 10478.6 192.25810508.61196.741810829.95212.145311053.04213.136811083.67219.4057
 11217.1214.463311351.87220.718711477.89217.505711659.77 221.32811714.38220.3872
11758.06209.166911813.07211.744411858.12222.162912029.07222.362312197.28230.1951
#Mann= 3 , 0 , 0
9480.523  0.0448       09480.523  0.0448       012197.28  0.0448       0
#XS Ineff= 2 , 0
       09659.182                       0
Bank Sta=9480.523,12197.28
Exp/Cntr=0.3,0.1

Type RM Length L Ch R = 1 ,  144237,493.016600,493.016600,493.016600
XS GIS Cut Line= 6
804103.904048273795321.172802672 804633.20166719 796458.11389637
804837.650864005797407.252773345804996.839889437797903.602786124
805146.878718227798215.049803138  805357.8886756798528.781996235
#Sta/Elev= 30
8899.376227.65158985.187223.31689076.743225.50679388.256217.6311 9497.24218.9797
9583.968212.96359898.708217.79599909.681213.49389965.183168.54429976.388164.6717
10021.13164.303410065.59169.648110379.11 174.61510460.71181.332510491.23177.4155
10562.42 182.47110572.59189.769610704.82 199.75610867.83199.454910949.54213.1074
11227.37211.441111268.96216.807211404.88212.631111617.38218.3733 11682.3214.3348
11715.09206.791511769.75209.303111802.54215.586211971.26 215.73212372.27229.3786
#Mann= 3 , 0 , 0
8899.376  0.0419       08899.376  0.0419       012372.27  0.0419       0
#XS Ineff= 2 , 0
       0                               0
Bank Sta=8899.376,12372.27
Exp/Cntr=0.3,0.1

Type RM Length L Ch R = 1 ,  143744,1479.049900,1479.049900,1479.049900
XS GIS Cut Line= 6
 803568.31639732795566.855211335804257.283661246796745.644240946
804613.550365418797708.620915636804785.553478748798085.683468074
804971.308629423798382.284836233805301.702729464798753.525780872
#Sta/Elev= 30
8859.987222.57489230.815212.40199356.608214.66819472.788209.9904 9823.84213.2474
9859.002190.02769870.722 184.1329894.163179.16329917.604165.7777    9999160.9775
10052.04169.140810325.01176.194810465.65174.357210508.42183.192210550.93  174.73
10625.34177.858210688.75193.873110730.93210.544110783.65214.935210994.77215.2273
11079.48205.802911207.14210.163211228.51205.503811325.41207.666311390.35201.9933
 11434.2203.079711478.05208.524611622.83205.933511807.14207.505112516.32 228.616
#Mann= 3 , 0 , 0
8859.987  0.0434       08859.987  0.0434       012516.32  0.0434       0
#XS Ineff= 2 , 0
       0                               0
Bank Sta=8859.987,12516.32
Exp/Cntr=0.3,0.1

Type RM Length L Ch R = 1 ,  142265,2958.099900,2958.099900,2958.099900
XS GIS Cut Line= 6
801911.161147509796125.918386141802477.244905412796721.750029087
803198.795228958797705.704007924803646.743151516 798204.29655385
804154.551679045798591.458047405805126.509095103799099.333461061
#Sta/Elev= 30
8664.946225.89898907.753223.56589007.623 216.776 9115.73219.01129143.319214.0258
9568.765 201.1329859.164202.95049907.989179.36049979.685160.399910038.66160.7106
10086.47171.836710694.61 174.53110745.74180.798110771.41172.499910822.74 179.446
10938.52177.683510969.33172.413511005.95181.4126 11209.5175.954711250.93178.0639
11279.67189.474711320.79183.792211443.85189.202611690.25187.692411715.78194.5356
11911.43194.4164 11995.2203.581712607.39209.808112902.79221.699113115.72222.0063
#Mann= 3 , 0 , 0
8664.946  0.0459       08664.946  0.0459       013115.72  0.0459       0
#XS Ineff= 2 , 0
       0                               0
Bank Sta=8664.946,13115.72
Exp/Cntr=0.3,0.1

Type RM Length L Ch R = 1 ,139306.9,1479.049900,1479.049900,1479.049900
XS GIS Cut Line= 6
797930.870187193800335.943394884799473.399952739 800419.60497348
800702.018586993800278.227013484802829.169665843799191.403941944
803520.989063293798979.401965886805077.686272055 799207.25759621
#Sta/Elev= 30
5752.747204.71226118.661204.46276289.266 211.7967250.184210.50247560.385203.0861
7740.774206.00718275.216193.13419313.273190.56779357.666189.32189379.863181.5386
9436.564180.26669468.838173.58969803.789170.93649876.046175.02179924.237 171.307
9960.658157.178710029.13157.151910097.09168.5314 10458.3168.099710481.65172.6213
10655.63169.5144 10724.3175.927910780.77198.172910893.12201.610912093.52196.7655
12646.81207.309312742.15204.844112835.35207.036412845.71212.064113257.36218.2542
#Mann= 3 , 0 , 0
5752.747  0.0508       05752.747  0.0508       013257.36  0.0508       0
#XS Ineff= 2 , 0
       09676.891        11056.22       0
Bank Sta=5752.747,13257.36
Exp/Cntr=0.3,0.1