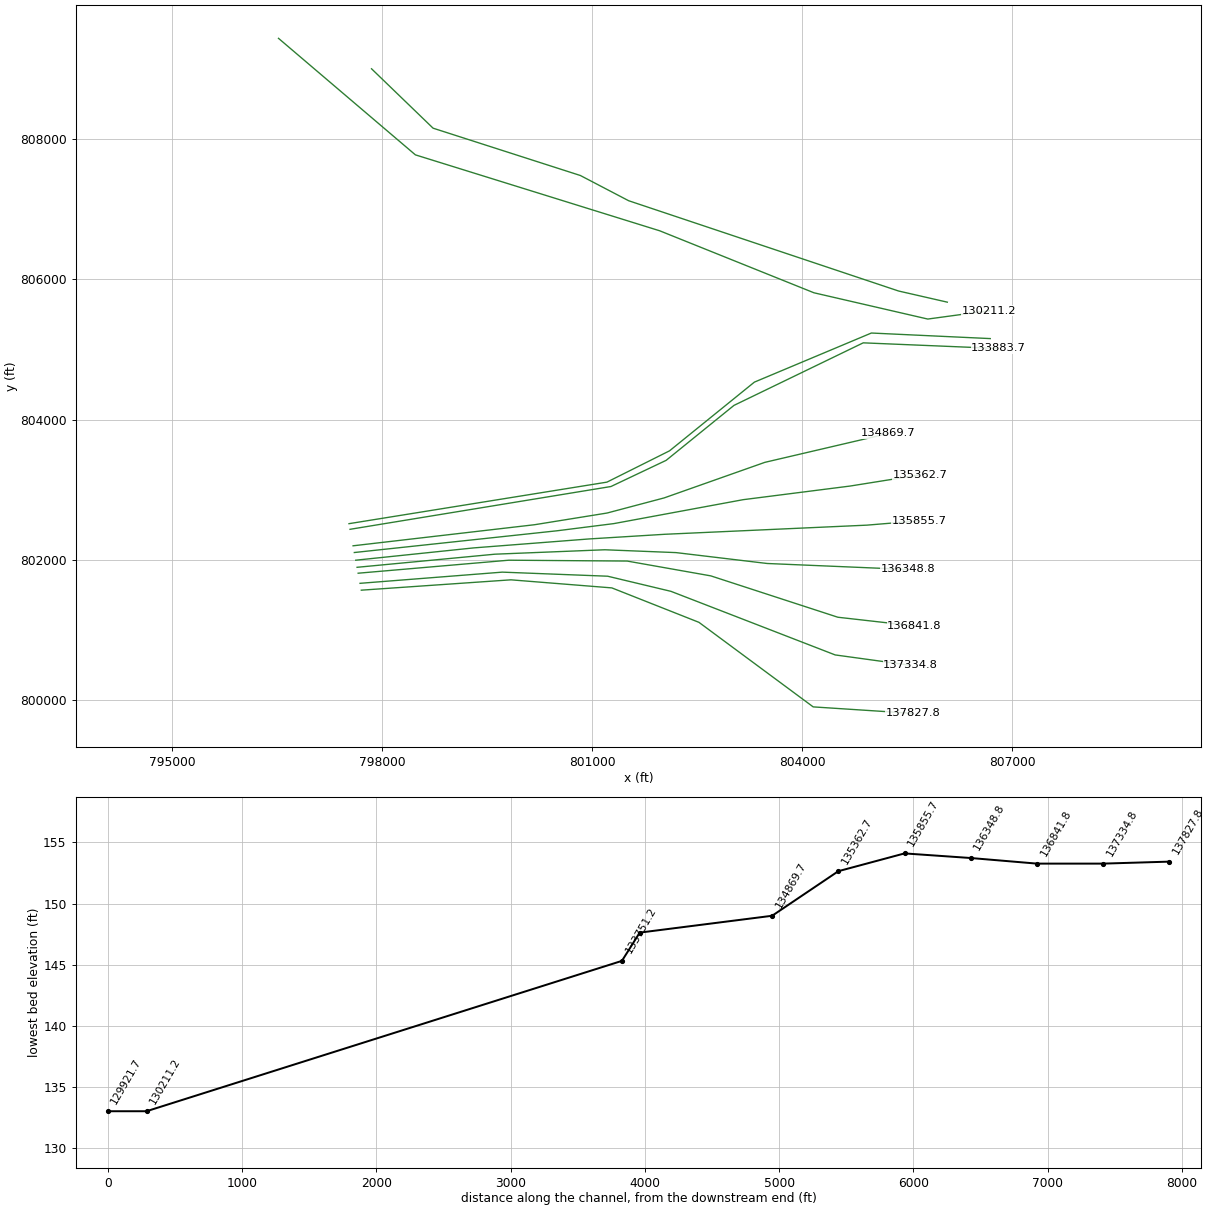
HEC-RAS study 17203_ras.prj: 17203

--- 17203_ras.g01 (geometry) --- (continued)

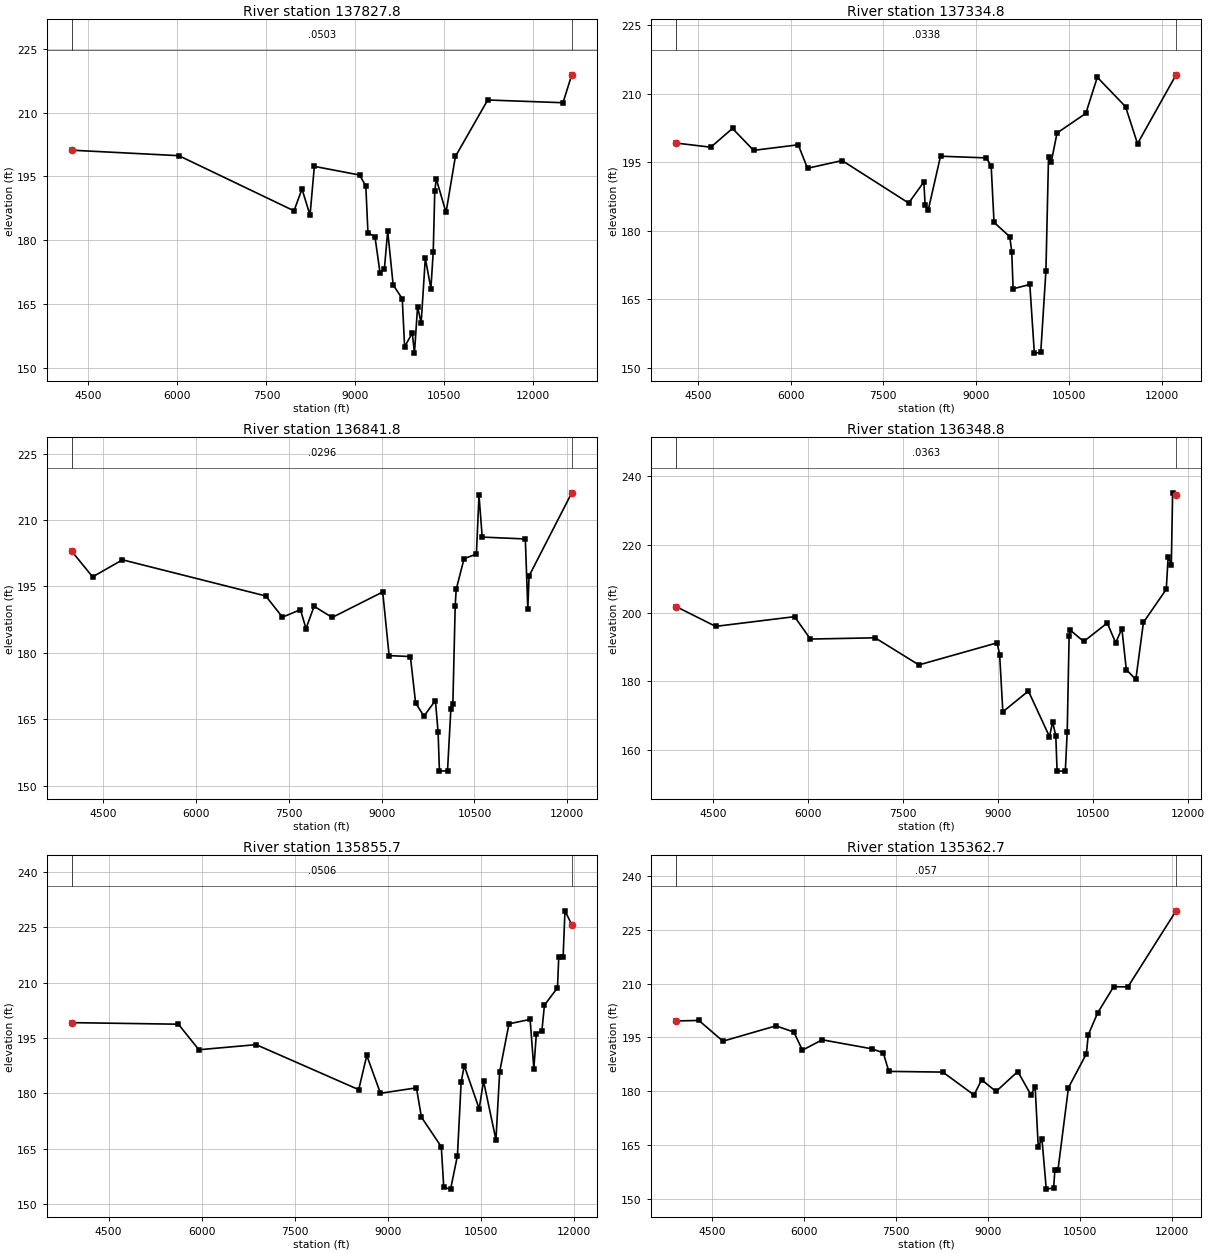
Type RM Length L Ch R = 1 ,137827.8,493.016700,493.016700,493.016700
XS GIS Cut Line= 6
797703.609278053801563.152304143799840.151440978801710.842502415
801281.098545343801595.613187179802524.629253209801103.874801561
804155.949287325799896.654187664805580.673732936799804.009101883
#Sta/Elev= 30
4216.327201.1808 6023.66199.88767964.799186.90658099.271  192.048235.018185.8924
8307.659197.37159070.612195.33349175.574192.72869211.135181.79929330.261180.7492
9414.625172.37369487.916 173.1429544.396182.1573 9636.28169.48379789.805166.2312
9829.462154.91459958.758158.15329995.332153.4268 10048.1164.349510108.38160.5156
10178.57175.776110272.74168.624310312.23177.293410338.05 191.62110363.74194.3753
10527.82186.531110685.71199.698311230.71212.991412499.53212.350612647.73 218.914
#Mann= 3 , 0 , 0
4216.327  0.0503       04216.327  0.0503       012647.73  0.0503       0
#XS Ineff= 2 , 0
       08911.263        10491.18       0
Bank Sta=4216.327,12647.73
Exp/Cntr=0.3,0.1

Type RM Length L Ch R = 1 ,137334.8,493.016600,493.016600,493.016600
XS GIS Cut Line= 6
797685.489253134 801661.00043875799716.616497546801820.622370899
 801220.76535064801762.516229928802125.270430237801546.359569564
804469.734156847800638.543590143805545.687868357800490.606694713
#Sta/Elev= 30
4147.692199.1986 4710.37198.28915061.843202.38945402.883197.5973 6123.98 198.817
 6274.05193.68636834.113195.36617909.695186.08058154.892190.68998175.406185.6943
8226.914184.60858424.159196.31849165.586195.95159243.255194.16479289.381181.8581
9544.018178.71979575.756175.46659597.812167.32889867.739 168.2759941.236153.2641
10044.68153.405410128.37171.291710170.39196.139410212.55194.951310308.26201.3946
10773.52205.688210958.67213.5843 11415.6207.148911609.03 199.052 12232.2 214.114
#Mann= 3 , 0 , 0
4147.692  0.0338       04147.692  0.0338       0 12232.2  0.0338       0
#XS Ineff= 2 , 0
       08873.029                       0
Bank Sta=4147.692,12232.2
Exp/Cntr=0.3,0.1

Type RM Length L Ch R = 1 ,136841.8,493.016700,493.016700,493.016700
XS GIS Cut Line= 6
797658.754669815801805.367188841799809.605959296801991.074734285
801500.336914182801978.654383734802693.732848555801767.328489885
804508.400040895801176.665471837 805602.39032948801052.850402251
#Sta/Elev= 30
3993.063202.97084331.442197.14884813.944201.00697128.086192.83777398.174  188.05
7688.578189.73757778.847185.46397909.372190.50728201.409187.98169017.873193.7388
9121.345179.36129464.867179.15259549.132 168.6759683.075165.67549869.044 169.216
9912.384162.10429934.173153.264110064.78153.343110118.85167.316310151.03168.4339
10188.92190.629110204.67194.305410332.17 201.27110531.58202.296310573.26215.6162
10625.13 206.14211321.61205.717711362.05189.879411382.27197.362112072.06216.1414
#Mann= 3 , 0 , 0
3993.063  0.0296       03993.063  0.0296       012072.06  0.0296       0
#XS Ineff= 2 , 0
       08779.836                       0
Bank Sta=3993.063,12072.06
Exp/Cntr=0.3,0.1

Type RM Length L Ch R = 1 ,136348.8,493.016600,493.016600,493.016600
XS GIS Cut Line= 6
 797643.14331761801889.668490618799612.402239889802076.952519104
801180.372322351802140.059481964 802197.56957978 802099.50177142
803499.007502526801944.133016825805509.607498109801858.973525137
#Sta/Elev= 30
 3917.17201.89944542.893196.08685787.826198.92976038.381192.37667059.608192.7381
7749.676184.80728983.766191.26049024.055187.84759074.443171.08879478.006177.1633
9810.199163.81089860.264168.1113 9910.33164.02259930.333153.724910060.34153.7221
10090.35165.307110120.36 193.24410140.37194.937210350.78191.660510721.99197.0666
10854.83191.284110952.56195.421611022.72183.4268 11172.9180.542911292.99197.2429
11653.06206.949511683.06216.528511733.07214.089511753.07235.171311807.69234.6165
#Mann= 3 , 0 , 0
 3917.17  0.0363       0 3917.17  0.0363       011807.69  0.0363       0
#XS Ineff= 2 , 0
       08752.909         10284.8       0
Bank Sta=3917.17,11807.69
Exp/Cntr=0.3,0.1

Type RM Length L Ch R = 1 ,135855.7,493.016600,493.016600,493.016600
XS GIS Cut Line= 6
797624.363916755801991.077255234799309.106950492802166.851902962
800953.666718721802294.489784256802036.946519911802361.159809873
804922.168793261 802491.56544821805664.098014057802553.135203049
#Sta/Elev= 30
3903.621199.15365623.561198.73275954.696191.81666877.459193.19598530.693181.0186
8660.821190.2741 8880.99180.03879461.355181.50929541.449173.58399861.837165.5699
9901.885154.539610012.02 154.09910122.14163.164510182.21183.120710232.26187.4825
10472.53175.849510542.61183.369910742.84167.4482 10802.9185.848610953.11 198.836
11293.66200.0281 11353.8186.742611393.89196.103611484.11196.993711524.24203.8925
11735.05208.579811755.14216.888211825.46216.935711855.59229.413311965.21225.6519
#Mann= 3 , 0 , 0
3903.621  0.0506       03903.621  0.0506       011965.21  0.0506       0
#XS Ineff= 2 , 0
       08681.569        10280.29       0
Bank Sta=3903.621,11965.21
Exp/Cntr=0.3,0.1

Type RM Length L Ch R = 1 ,135362.7,493.016700,493.016700,493.016700
XS GIS Cut Line= 6
797604.055393428802100.743281245800498.748249054 802411.13761878
801310.332662255802513.807694748803155.211671203802855.124120191
804683.288276762803049.901007488805680.758599162803209.357957736
#Sta/Elev= 30
3910.166 199.5834283.747199.72384676.183193.93955540.941 198.2175832.445196.4822
5973.172191.43116294.832194.32277099.676191.82567291.091190.70727381.916185.5036
8262.814185.30938772.284 178.9138894.703183.17419130.268179.8934 9485.33185.4663
9697.953  179.019768.602181.08939819.046164.48329879.416166.64639949.781152.6445
10070.33152.967110090.42158.105110140.66158.009210311.79180.961810604.08190.4142
10634.37195.679310785.82201.761611048.34209.139511280.96209.080612066.88230.3205
#Mann= 3 , 0 , 0
3910.166   0.057       03910.166   0.057       012066.88   0.057       0
#XS Ineff= 2 , 0
       08576.498        10343.86       0
Bank Sta=3910.166,12066.88
Exp/Cntr=0.3,0.1

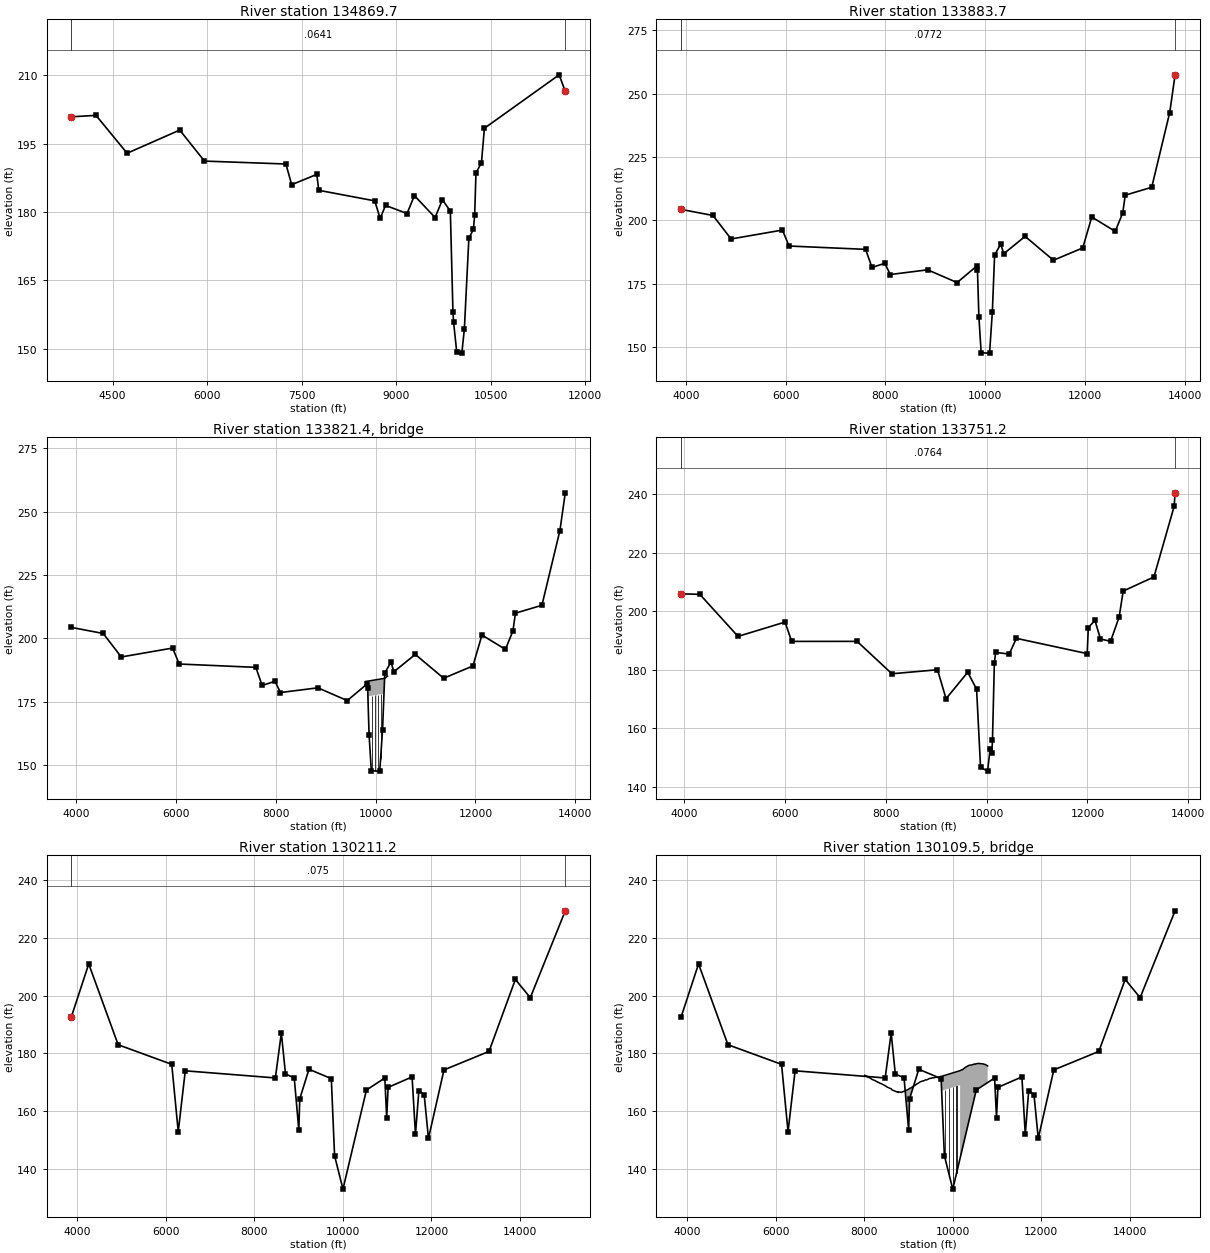
Type RM Length L Ch R = 1 ,134869.7,986.033200,986.033200,986.033200
XS GIS Cut Line= 6
797586.280433506802196.728064761800177.327744365802497.616358072
801213.588612169802664.745849326802027.972085476802880.471559182
803466.009628206803388.366062075805229.526707917803800.370195135
#Sta/Elev= 30
3845.278200.86644236.766201.17874730.093192.86655565.336197.9553  5957.8191.1447
7250.518 190.5077342.025 185.9657740.815188.22767771.687184.73328661.039182.4129
8746.364178.5502 8831.69181.4196  9172.9179.6329 9289.86183.56649618.138178.7618
9734.467182.64799860.363180.18289901.666158.07089911.953155.75589962.537149.1491
10042.76148.9977 10083.1154.322310154.26174.213810225.96176.142710246.54 179.263
10267.14188.569310353.97190.759110401.05198.354311587.22210.0778 11684.6206.4286
#Mann= 3 , 0 , 0
3845.278  0.0641       03845.278  0.0641       0 11684.6  0.0641       0
#XS Ineff= 2 , 0
       08437.068        10386.07       0
Bank Sta=3845.278,11684.6
Exp/Cntr=0.3,0.1

Type RM Length L Ch R = 1 ,133883.7,132.496500,132.496500,132.496500
XS GIS Cut Line= 6
 797542.67933028802432.174021989801268.447000593803043.259733453
802056.355804563803416.819758028803025.056399345804201.740472481
804870.281048685 805094.64851661806802.337934077805013.972204655
#Sta/Elev= 30
3908.921204.29854546.013201.9154 4908.73192.64655936.971196.1648 6068.23189.8646
7602.643188.54947729.208181.42727986.545183.03778095.975178.62258844.688180.4771
9434.176175.44549825.104181.9202 9841.83180.47969870.513161.97349915.922147.7365
10084.45147.619810140.42164.0337 10185.2186.278510308.34 190.65410367.66186.8119
10795.81193.660311364.17184.253911950.52189.111312130.67201.295812601.08195.6387
12751.22 202.94112801.26209.921213331.72213.036513692.03242.527313799.47257.3875
#Mann= 3 , 0 , 0
3908.921  0.0772       03908.921  0.0772       013799.47  0.0772       0
#XS Ineff= 2 , 0
       08384.294                       0
Bank Sta=3908.921,13799.47
Exp/Cntr=0.3,0.1

Type RM Length L Ch R = 3 ,133821.4,,,
BEGIN DESCRIPTION:
END DESCRIPTION:
Bridge Culvert--1,0,-1,-1, 0
Deck Dist Width WeirC Skew NumUp NumDn MinLoCord MaxHiCord MaxSubmerge Is_Ogee
39.248250,54.000000,2.6,0, 22, 22, , , 0.95, 0, 0,0,,
 9800.00 9800.80 9805.14 9812.85 9823.04 9824.90 9826.36 9863.18 9863.1810159.18
10159.1810185.7810186.5410198.5910199.1110210.6510212.3510216.7410223.0310233.56
10235.4610239.45
  183.01  183.03  183.06  183.01  183.06  183.07  183.06  183.18  183.18  184.15
  184.15  184.23  184.24  184.39  184.40  184.65  184.68  184.77  184.89  185.01
  185.04  185.06
 -816.99 -816.97 -816.94 -816.99 -816.94 -816.93 -816.94 -816.82  177.18  178.15
 -815.85 -815.77 -815.76 -815.61 -815.60 -815.35 -815.32 -815.23 -815.11 -814.99
 -814.96 -814.94
 9800.00 9800.80 9805.14 9812.85 9823.04 9824.90 9826.36 9847.07 9847.0710143.07
10143.0710185.7810186.5410198.5910199.1110210.6510212.3510216.7410223.0310233.56
10235.4610239.45
  183.01  183.03  183.06  183.01  183.06  183.07  183.06  183.13  183.13  184.09
  184.09  184.23  184.24  184.39  184.40  184.65  184.68  184.77  184.89  185.01
  185.04  185.06
 -816.99 -816.97 -816.94 -816.99 -816.94 -816.93 -816.94 -816.87  177.13  178.09
 -815.91 -815.77 -815.76 -815.61 -815.60 -815.35 -815.32 -815.23 -815.11 -814.99
 -814.96 -814.94
Pier Skew, UpSta & Num, DnSta & Num=  ,9921.78, 2 ,9905.67, 2 , 0 , 0 , 0 ,,
    2.00    2.00
 -816.63  183.37
    2.00    2.00
 -816.68  183.32
Pier Skew, UpSta & Num, DnSta & Num=  ,9981.38, 2 ,9965.27, 2 , 0 , 0 , 0 ,,
    2.00    2.00
 -816.43  183.57
    2.00    2.00
 -816.49  183.51
Pier Skew, UpSta & Num, DnSta & Num=  ,10040.98, 2 ,10024.87, 2 , 0 , 0 , 0 ,,
    2.00    2.00
 -816.24  183.76
    2.00    2.00
 -816.29  183.71
Pier Skew, UpSta & Num, DnSta & Num=  ,10100.58, 2 ,10084.47, 2 , 0 , 0 , 0 ,,
    2.00    2.00
 -816.05  183.95
    2.00    2.00
 -816.10  183.90
BR Coef=-1 , 0 , 0 ,, 0 ,,,0.8,0,1,0,
WSPro=,,,, 1 ,,,, 0 ,,,, 0 ,,,,-1 ,-1 ,-1 , 0 , 0 , 0 , 0 , 0
BC Design=,, 0 ,, 0 ,,,,,,

Type RM Length L Ch R = 1 ,133751.2,3540.008400,3540.008400,3540.008400
XS GIS Cut Line= 6
797527.777143117802512.645832667801210.680342317803105.738472193
802104.512600332803552.654601201803316.109458745  804533.6512575
804986.786730617805234.720281065806684.322289884805155.339121833
#Sta/Elev= 30
3936.643205.91584306.849205.72935065.036191.36515998.236196.25316130.101189.6502
7428.465189.6604 8119.57178.58719024.236179.95999193.951170.05949624.101179.1006
9800.071173.32939878.861146.606810018.84145.308110067.66152.833610103.42151.5305
10115.68155.938610152.77 182.34610179.63185.898510446.97185.319510589.87190.6944
11995.57185.472212017.12 194.35512148.92196.838112259.05190.474812459.26189.6797
12629.45 197.95712709.54206.8502 13320.2211.687113720.64235.766513739.98240.4328
#Mann= 3 , 0 , 0
3936.643  0.0764       03936.643  0.0764       013739.98  0.0764       0
#XS Ineff= 2 , 0
       08382.556                       0
Bank Sta=3936.643,13739.98
Exp/Cntr=0.3,0.1

Type RM Length L Ch R = 1 ,130211.2,289.424300,289.424300,289.424300
XS GIS Cut Line= 6
796521.320254624809442.464374691798475.984685838807778.715559959
 801964.56782186806694.393716842804166.479274124 805809.41791147
805792.203749269805434.250724897806667.593851268805553.351419047
#Sta/Elev= 30
3868.103192.63084260.519210.94294924.505182.97126134.796 176.195 6281.56152.8814
6440.555173.95528474.957171.48668610.029187.03678703.541172.86628900.954171.5067
9004.855153.46579025.635164.22649233.533174.49019738.334171.2427 9811.95144.5753
10001.25133.008310531.78167.3138 10946.4171.465710988.92 157.61211020.81168.2139
11562.31 171.84911638.72151.931111715.12167.040311835.18165.726611931.78150.5578
12282.67174.2604 13299.6180.667313894.84205.577614231.93199.259515021.73229.3165
#Mann= 3 , 0 , 0
3868.103   0.075       03868.103   0.075       015021.73   0.075       0
#XS Ineff= 2 , 0
       09319.584         10410.9       0
Bank Sta=3868.103,15021.73
Exp/Cntr=0.3,0.1

Type RM Length L Ch R = 3 ,130109.5,,,
BEGIN DESCRIPTION:
END DESCRIPTION:
Bridge Culvert--1,0,-1,-1, 0
Deck Dist Width WeirC Skew NumUp NumDn MinLoCord MaxHiCord MaxSubmerge Is_Ogee
86.712150,116.000000,2.6,0, 60, 60, , , 0.95, 0, 0,0,,
 8012.85 8055.59 8076.59 8129.09 8181.58 8265.58 8276.08 8297.08 8307.58 8328.57
 8344.37 8391.57 8486.06 8507.06 8612.05 8633.05 8738.22 8759.04 8769.54 8780.04
 8822.04 8832.54 8990.02 9042.52 9063.52 9095.02 9147.51 9168.51 9179.01 9200.01
 9210.51 9263.00 9326.00 9336.50 9388.99 9409.99 9472.99 9525.48 9535.98 9577.98
 9619.98 9661.97 9724.97 9751.74 9751.7410166.7410166.7410207.9110218.4110291.90
10365.5410439.3710492.1010503.4610534.9210587.0210692.2310713.5910734.6810789.57
  172.39  172.15  171.82  171.48  170.96  170.42  170.22  170.18  170.00  169.94
  169.73  169.47  168.70  168.42  167.70  167.32  166.65  166.69  166.46  166.62
  166.56  166.44  167.47  167.97  168.06  168.48  168.90  169.22  169.23  169.53
  169.54  170.11  170.47  170.42  170.84  170.79  171.28  171.40  171.55  171.52
  171.74  171.63  172.02  172.06  172.06  174.01  174.01  174.34  174.33  175.22
  175.84  176.02  176.32  176.22  176.42  176.50  176.34  176.17  176.17  175.63
 -827.61 -827.85 -828.18 -828.52 -829.04 -829.58 -829.78 -829.82 -830.00 -830.06
 -830.27 -830.53 -831.30 -831.58 -832.30 -832.68 -833.35 -833.31 -833.54 -833.38
 -833.44 -833.56 -832.53 -832.03 -831.94 -831.52 -831.10 -830.78 -830.77 -830.47
 -830.46 -829.89 -829.53 -829.58 -829.16 -829.21 -828.72 -828.60 -828.45 -828.48
 -828.26 -828.37 -827.98 -827.94  167.06  169.01 -825.99 -825.66 -825.67 -824.78
 -824.16 -823.98 -823.68 -823.78 -823.58 -823.50 -823.66 -823.83 -823.83 -824.37
 8012.85 8055.59 8076.59 8129.09 8181.58 8265.58 8276.08 8297.08 8307.58 8328.57
 8344.37 8391.57 8486.06 8507.06 8612.05 8633.05 8738.22 8759.04 8769.54 8780.04
 8822.04 8832.54 8990.02 9042.52 9063.52 9095.02 9147.51 9168.51 9179.01 9200.01
 9210.51 9263.00 9326.00 9336.50 9388.99 9409.99 9427.44 9472.99 9525.48 9535.98
 9577.98 9619.98 9661.97 9725.03 9725.03 9735.4610140.0310140.0310218.4110291.90
10365.5410439.3710492.1010503.4610534.9210587.0210692.2310713.5910734.6810789.57
  172.39  172.15  171.82  171.48  170.96  170.42  170.22  170.18  170.00  169.94
  169.73  169.47  168.70  168.42  167.70  167.32  166.65  166.69  166.46  166.62
  166.56  166.44  167.47  167.97  168.06  168.48  168.90  169.22  169.23  169.53
  169.54  170.11  170.47  170.42  170.84  170.79  171.00  171.28  171.40  171.55
  171.52  171.74  171.63  172.02  172.02  171.98  173.88  173.88  174.33  175.22
  175.84  176.02  176.32  176.22  176.42  176.50  176.34  176.17  176.17  175.63
 -827.61 -827.85 -828.18 -828.52 -829.04 -829.58 -829.78 -829.82 -830.00 -830.06
 -830.27 -830.53 -831.30 -831.58 -832.30 -832.68 -833.35 -833.31 -833.54 -833.38
 -833.44 -833.56 -832.53 -832.03 -831.94 -831.52 -831.10 -830.78 -830.77 -830.47
 -830.46 -829.89 -829.53 -829.58 -829.16 -829.21 -829.00 -828.72 -828.60 -828.45
 -828.48 -828.26 -828.37 -827.98  167.02  166.98  168.88 -826.12 -825.67 -824.78
 -824.16 -823.98 -823.68 -823.78 -823.58 -823.50 -823.66 -823.83 -823.83 -824.37
Pier Skew, UpSta & Num, DnSta & Num=  ,9833.54, 2 ,9806.83, 2 , 0 , 0 , 0 ,,
    4.00    4.00
 -827.55  172.45
    4.00    4.00
 -827.68  172.32
Pier Skew, UpSta & Num, DnSta & Num=  ,9917.34, 2 ,9890.63, 2 , 0 , 0 , 0 ,,
    4.00    4.00
 -827.16  172.84
    4.00    4.00
 -827.29  172.71
Pier Skew, UpSta & Num, DnSta & Num=  ,10001.14, 2 ,9974.43, 2 , 0 , 0 , 0 ,,
    4.00    4.00
 -826.77  173.23
    4.00    4.00
 -826.89  173.11
Pier Skew, UpSta & Num, DnSta & Num=  ,10084.94, 2 ,10058.23, 2 , 0 , 0 , 0 ,,
    4.00    4.00
 -826.38  173.62
    4.00    4.00
 -826.50  173.50
BR Coef=-1 , 0 , 0 ,, 0 ,,,0.8,0,1,0,
WSPro=,,,, 1 ,,,, 0 ,,,, 0 ,,,,-1 ,-1 ,-1 , 0 , 0 , 0 , 0 , 0
BC Design=,, 0 ,, 0 ,,,,,,

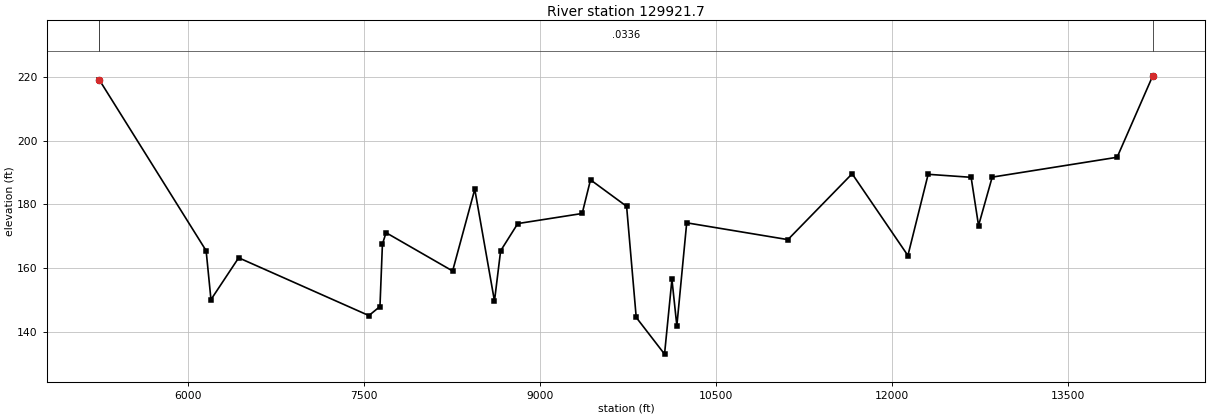
Type RM Length L Ch R = 1 ,129921.7,3948.787600,3948.787600,3948.787600
XS GIS Cut Line= 6
797849.790954202   809007.646366798728.425198793808159.662153229
800832.230295181807483.666949108801520.786530644807123.818464264
805375.562734097805834.522702903806071.130409956805675.430096209
#Sta/Elev= 30
  5239.8219.0984 6150.81165.4746 6192.08150.1292 6428.34163.25287539.164145.1112
7633.696147.95897654.703167.55277685.619 171.1348253.406159.1093 8442.47184.7699
8610.527149.66948663.045165.44818809.164173.99399358.645177.16089429.744187.7243
9737.616179.41179819.643144.540310061.25133.008310124.28 156.46610166.29141.9024
10250.33174.232311113.59168.957711661.47189.631712137.26163.957512310.01189.4631
12676.49188.519512739.93173.368412856.24 188.57613922.12194.811814225.89220.3799
#Mann= 3 , 0 , 0
  5239.8  0.0336       0  5239.8  0.0336       014225.89  0.0336       0
#XS Ineff= 2 , 0
       09222.799        10429.64       0
Bank Sta=5239.8,14225.89
Exp/Cntr=0.3,0.1