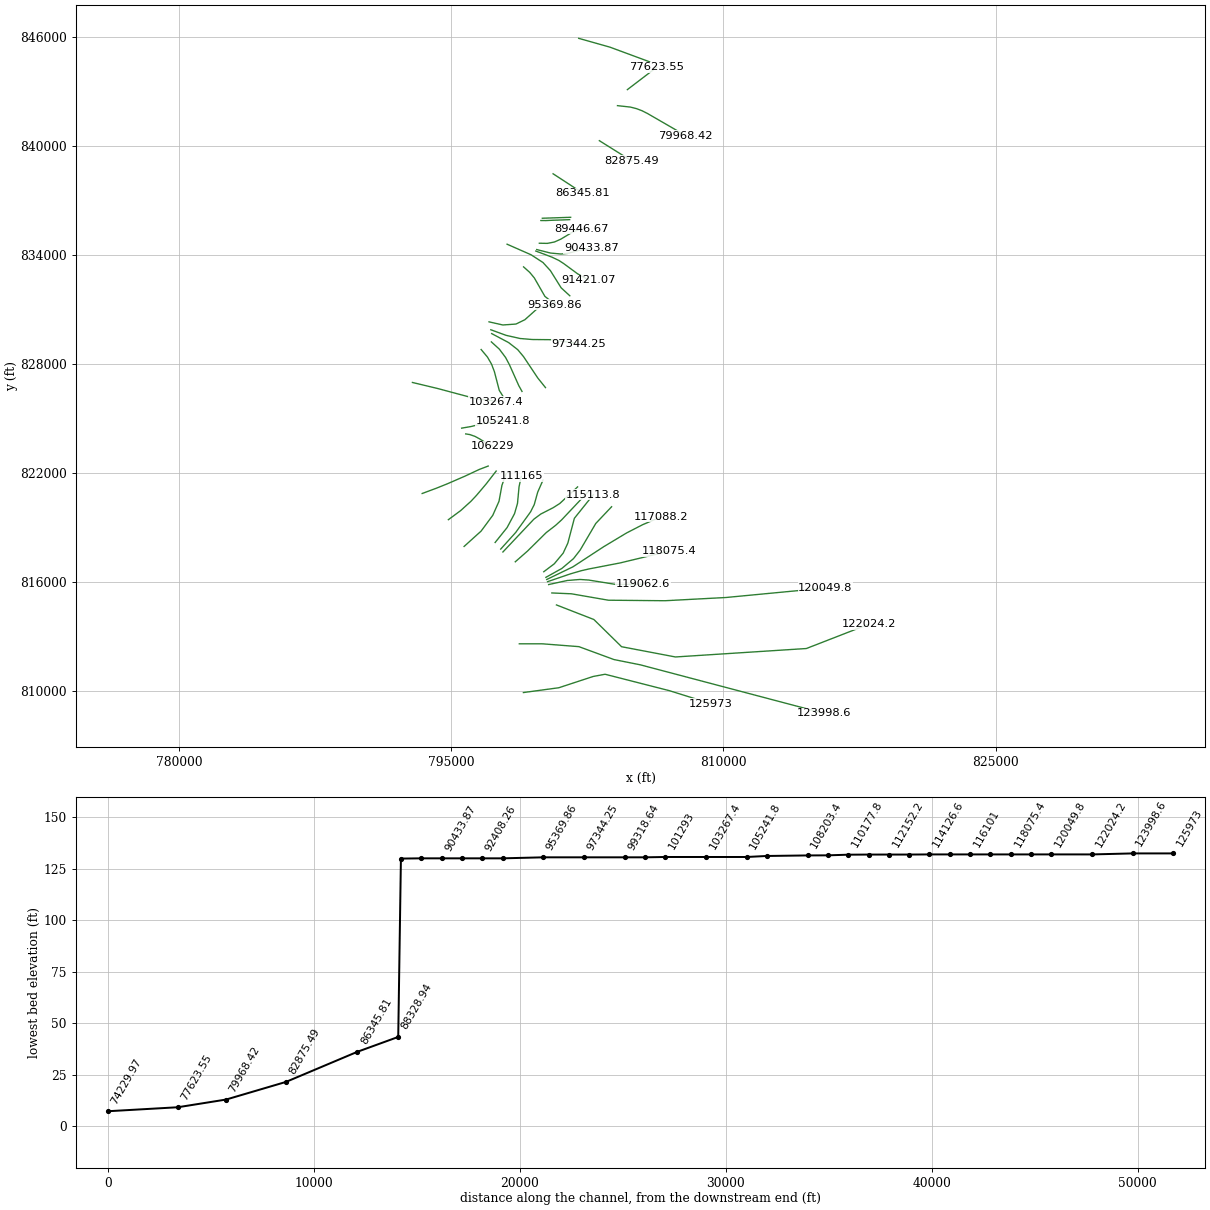
HEC-RAS study 17203_ras.prj: 17203

--- 17203_ras.g01 (geometry) --- (continued)

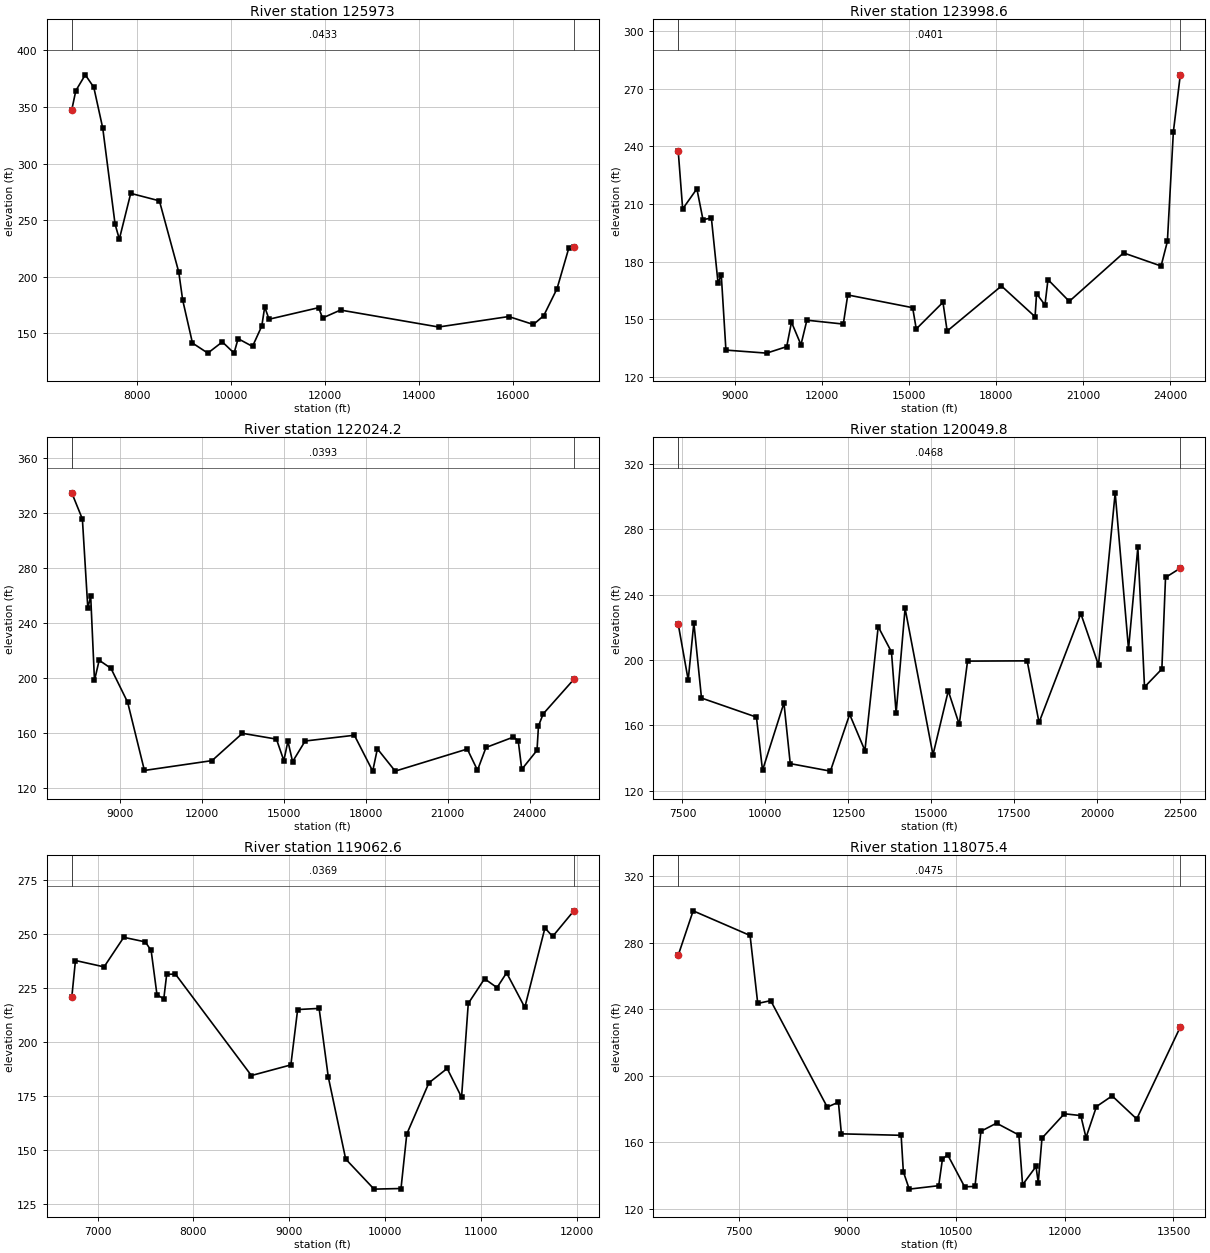
Type RM Length L Ch R = 1 ,  125973,1974.393800,1974.393800,1974.393800
XS GIS Cut Line= 6
798979.212412238809909.831137359800929.004006892810174.567484424
802820.182273239810795.227221742803476.397488892810917.730533466
 807021.79741171810012.297493339809296.102967292809300.491937771
#Sta/Elev= 30
6623.356347.37196709.479364.35566910.259378.3505 7091.05367.39677282.038331.1991
7543.732246.46537634.403233.14027876.555273.62318486.201267.02158897.667204.0841
8980.732179.42719189.214 141.3749515.456132.48019824.109142.400110073.25132.4801
10158.98145.258510465.24 138.39410662.69156.407810724.58173.253710816.76162.4244
11870.97172.637911954.11163.513612335.99170.539214420.82155.562615911.72164.7982
16435.64157.776516655.68165.5477 16938.6189.421517190.08225.458217296.01226.5315
#Mann= 3 , 0 , 0
6623.356  0.0433       06623.356  0.0433       017296.01  0.0433       0
#XS Ineff= 2 , 0
       08846.979        11633.45       0
Bank Sta=6623.356,17296.01
Exp/Cntr=0.3,0.1

Type RM Length L Ch R = 1 ,123998.6,1974.393800,1974.393800,1974.393800
XS GIS Cut Line= 6
798752.618532687812594.914316669800015.283381313812594.890123755
802034.380521208812438.517939851803963.886664659811727.864466235
805418.765101403811436.648954019815546.102967292808762.297493339
#Sta/Elev= 30
7041.064237.45187193.566207.48177683.697  217.967893.711201.93668183.842202.7318
 8414.16168.81768524.364173.27288684.778134.056810089.28132.480110780.36135.8587
10944.71148.580311271.65136.839611476.21149.613512731.31147.596912885.01162.7444
15122.12156.113815246.23145.053416166.74158.915616311.54143.954918183.59167.4107
19341.98151.411419393.69163.427319683.29157.526519786.72170.734620521.06 159.412
 22393.1184.614723685.95177.797923903.15 190.57824110.01247.696924349.03277.2571
#Mann= 3 , 0 , 0
7041.064  0.0401       07041.064  0.0401       024349.03  0.0401       0
#XS Ineff= 2 , 0
       09437.124        12443.55       0
Bank Sta=7041.064,24349.03
Exp/Cntr=0.3,0.1

Type RM Length L Ch R = 1 ,122024.2,1974.393800,1974.393800,1974.393800
XS GIS Cut Line= 6
 800796.97130698814736.271742716802859.042663485813933.004140347
804386.365962327812434.137617111807351.667186469811870.042527497
814565.250084698812335.411962837818011.380745053813675.491937786
#Sta/Elev= 30
7246.732334.9176 7635.34315.81727834.053250.8719 7939.45259.41788077.777198.1326
8249.641 212.8378680.496206.9484 9290.65182.25719905.071132.480112380.07139.6539
13491.28159.558414736.93155.322615007.21139.645115157.32153.812515327.38 138.876
15787.45153.947617588.49158.152218259.99131.987918430.42148.265419082.93131.9879
21720.93148.104422094.31132.644222405.47149.238123411.73156.842623585.71153.9974
23714.46133.2786 24272.4147.175224326.04164.898324497.72173.710625620.43198.9144
#Mann= 3 , 0 , 0
7246.732  0.0393       07246.732  0.0393       025620.43  0.0393       0
#XS Ineff= 2 , 0
       0                11413.58       0
Bank Sta=7246.732,25620.43
Exp/Cntr=0.3,0.1

Type RM Length L Ch R = 1 ,120049.8,987.196900,987.196900,987.196900
XS GIS Cut Line= 6
  800544.7862225815396.156047143801618.214317236815350.079460302
803663.492884393 814996.18458404806785.282643172 814968.40460582
810129.879980923815145.827482057  815608.4015626815668.003655001
#Sta/Elev= 30
7372.003221.9177 7672.37 187.7487842.423222.8789 8072.76 176.7289728.711165.0468
9911.848132.480110557.08173.762510747.18136.586511957.26 131.99612537.32166.7547
12997.33144.561913397.34 220.39613797.38204.955713937.41167.489514207.51231.6316
 15048.2141.970415508.89181.091715839.52160.614716090.11 199.33717886.01199.4966
18243.88161.760619503.25228.402820035.83196.915520538.26302.3327 20940.2206.6612
21221.56 268.95821422.53 183.47121945.06194.492722055.57  250.5322500.97256.2196
#Mann= 3 , 0 , 0
7372.003  0.0468       07372.003  0.0468       022500.97  0.0468       0
#XS Ineff= 2 , 0
       0                10841.99       0
Bank Sta=7372.003,22500.97
Exp/Cntr=0.3,0.1

Type RM Length L Ch R = 1 ,119062.6,987.196900,987.196900,987.196900
XS GIS Cut Line= 6
800367.817936838815859.223061353801392.519987017816082.637761831
802093.003369093816139.970887527802572.078414023816107.278929338
804052.997209966815868.133181944805556.173515648815877.326161608
#Sta/Elev= 30
6730.464220.55466768.904237.63787067.729234.69427272.915248.35577497.668246.2426
7558.898242.26417619.788221.82357690.827219.90167721.272231.26587812.429231.3467
8605.184184.47859017.154189.39279088.005214.97499312.128215.50489407.581183.8694
9589.351 145.8919885.459131.987910166.78132.272910227.07157.445710458.17181.1113
10648.65 187.73610798.83174.455710868.85217.787811038.88229.203511168.88225.1078
 11268.9231.931811458.97215.976811669.16252.689611749.25248.7407 11970.8260.5955
#Mann= 3 , 0 , 0
6730.464  0.0369       06730.464  0.0369       0 11970.8  0.0369       0
#XS Ineff= 2 , 0
       0                10613.38       0
Bank Sta=6730.464,11970.8
Exp/Cntr=0.3,0.1

Type RM Length L Ch R = 1 ,118075.4,987.196900,987.196900,987.196900
XS GIS Cut Line= 6
800307.059255213816018.208278358801553.852650195816443.457667708
802167.710219055 816622.57788673802593.537415266816719.809575424
 804300.63242504817048.853721604807020.342802316817704.157617658
#Sta/Elev= 30
6664.062272.37756869.824299.01587655.701284.22317761.426243.43487940.488 245.108
8721.003181.22468875.175184.14568916.084165.16689740.672164.29119771.154142.4536
9852.439131.9879 10259.2 134.05610310.22149.832610381.65152.693310616.74133.3781
10759.99133.603510841.96166.714811057.36171.578311365.59 164.47411416.98134.6146
 11602.3145.5838 11633.2135.882811684.69162.590511993.64177.2155 12220.2 176.128
12292.29162.911112436.46181.533812652.73187.946212992.39174.091113594.04229.3206
#Mann= 3 , 0 , 0
6664.062  0.0475       06664.062  0.0475       013594.04  0.0475       0
#XS Ineff= 2 , 0
       0                11279.53       0
Bank Sta=6664.062,13594.04
Exp/Cntr=0.3,0.1

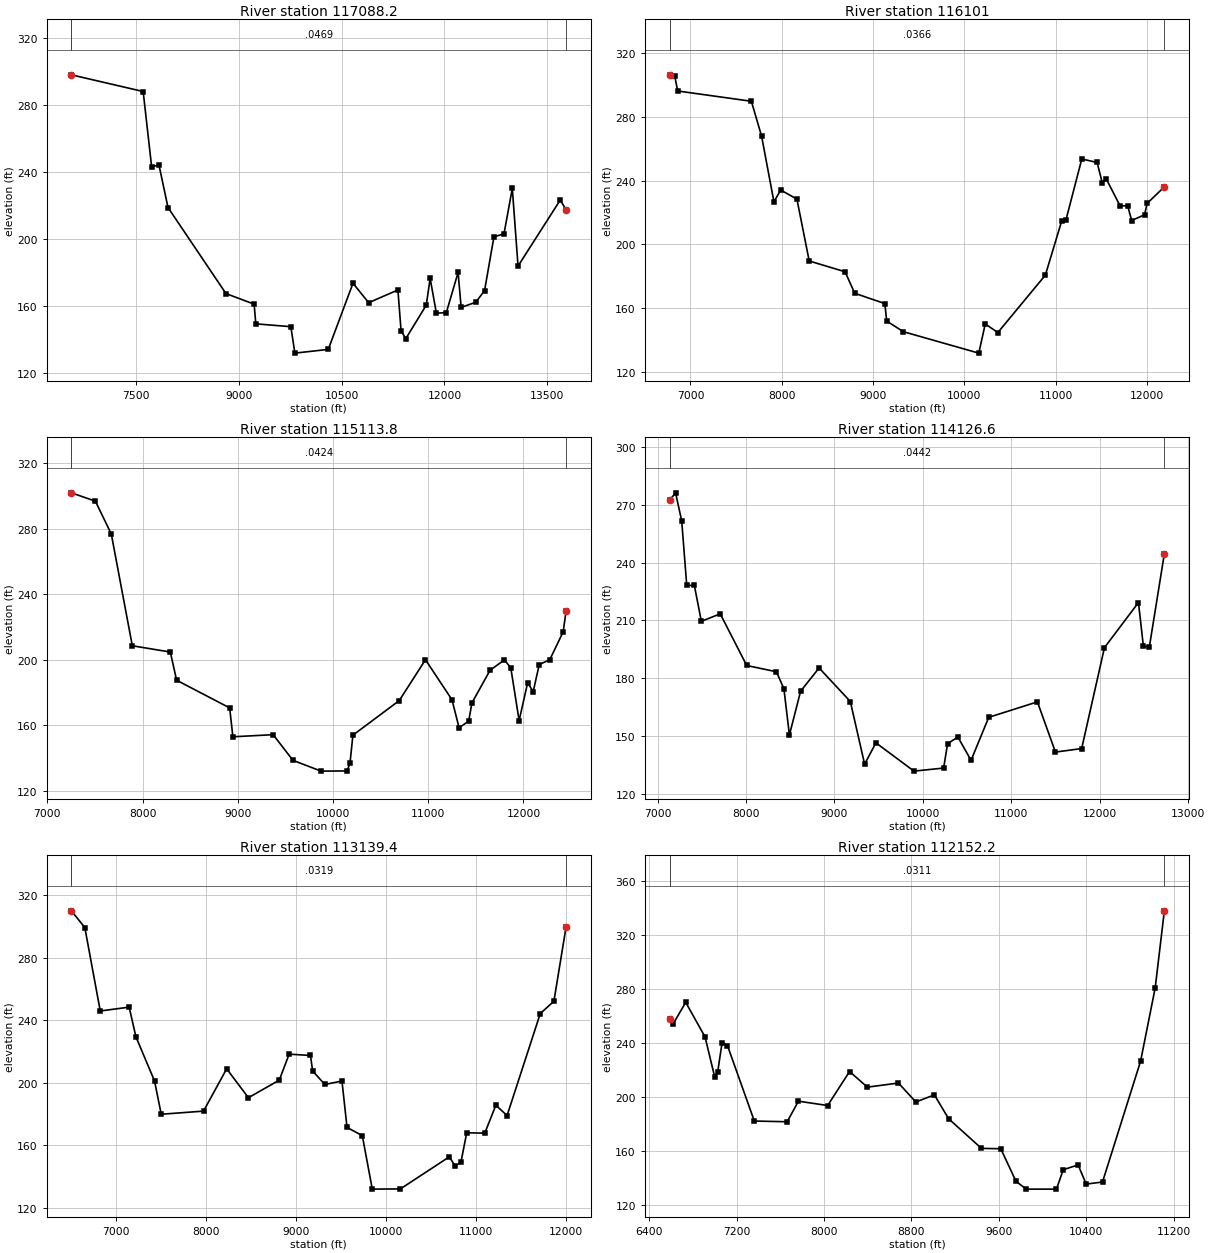
Type RM Length L Ch R = 1 ,117088.2,987.196900,987.196900,987.196900
XS GIS Cut Line= 6
800261.388471118816137.713496615801706.031786086816835.775286165
803400.427381794817944.371240677804663.868603876 818703.14422763
805549.415494137819158.019427978806572.197169212819595.790715401
#Sta/Elev= 30
6558.967297.79727605.616287.85487729.425242.88157835.727244.16687967.975218.7253
8813.847167.4502 9224.09 161.1649248.509149.43899759.721147.73889818.344131.9879
10305.38134.207510665.77173.620310894.42 162.03611321.13169.621211367.28145.2138
11436.51140.636411734.49160.560211791.33176.490111882.27155.787312027.04156.1038
12198.81180.046112243.58159.2247 12455.9162.286212584.77169.197312721.94 201.327
 12867.9202.987112989.54230.091513073.27183.860613688.87223.204113773.49217.4105
#Mann= 3 , 0 , 0
6558.967  0.0469       06558.967  0.0469       013773.49  0.0469       0
#XS Ineff= 2 , 0
       0                11379.97       0
Bank Sta=6558.967,13773.49
Exp/Cntr=0.3,0.1

Type RM Length L Ch R = 1 ,  116101,987.196900,987.196900,987.196900
XS GIS Cut Line= 6
800216.013807803816256.443865672801095.137683809816745.871246621
801736.570044398817287.654656515802105.071922809817760.432349578
802963.746543944819223.777905717803836.636966377820146.134207502
#Sta/Elev= 30
6772.479306.13226826.764 305.5466860.191296.0178 7667.42289.59117779.485267.7258
7914.503226.6634 7988.39234.03678166.365228.37518301.062189.64218693.378182.9101
 8800.24169.41679129.839162.98619150.013152.0395 9332.71145.3928 10158.9131.9879
10229.89150.246310368.02 144.887 10888.1180.756911067.95214.776311112.61214.9917
11287.55253.465811455.81251.283311511.35238.6855 11555.2241.0357 11705.4224.3525
11790.99224.012311834.15214.972311975.63218.564812002.77225.618212192.28236.0613
#Mann= 3 , 0 , 0
6772.479  0.0366       06772.479  0.0366       012192.28  0.0366       0
#XS Ineff= 2 , 0
       0                10995.37       0
Bank Sta=6772.479,12192.28
Exp/Cntr=0.3,0.1

Type RM Length L Ch R = 1 ,115113.8,987.196900,987.196900,987.196900
XS GIS Cut Line= 6
800098.372660905816564.271533385800678.292490631 817003.10432668
801166.930927217817588.531367406 801423.84586665818140.170819044
801784.615529835819509.114893332802825.303494453820806.251452789
#Sta/Elev= 30
7253.215301.88657505.084296.79547672.212276.74447892.836208.51138291.796 204.695
8357.945187.4804 8914.89170.59338948.884 152.9519371.674154.23899579.527138.5604
9874.941131.987910148.07132.111610178.61136.946710209.14153.946510695.79175.0535
10970.93199.996811249.18175.578711323.95158.4725 11424.8162.536311459.16173.6756
11649.39193.567111800.82199.918711867.27194.940411954.45162.839412043.56 185.873
12102.53180.575912165.64197.067612276.14199.981712417.19 217.05512447.16229.6067
#Mann= 3 , 0 , 0
7253.215  0.0424       07253.215  0.0424       012447.16  0.0424       0
#XS Ineff= 2 , 0
       0                10863.99       0
Bank Sta=7253.215,12447.16
Exp/Cntr=0.3,0.1

Type RM Length L Ch R = 1 ,114126.6,987.196900,987.196900,987.196900
XS GIS Cut Line= 6
798529.771357208 817113.11687912799201.852070302817702.218862236
800233.983740687818720.433060929800754.738304377819123.973878309
  801083.5646469819422.983323351802555.188805759820982.560621977
#Sta/Elev= 30
7136.752272.30167202.961276.0795 7272.62261.50327329.426228.14977415.464228.1229
7494.717 209.5277707.911213.44538007.639186.68048343.437183.43428428.199174.6328
8490.368150.71078617.099173.38688825.923185.40359179.362168.03329340.709135.5842
9468.474146.64389899.303131.987910234.32133.578810278.87146.225910395.76149.6241
10544.35137.574410744.21159.845911294.71167.843711498.31141.8553 11795.1 143.665
12052.59195.918512437.11 219.27812493.17196.570812560.49196.305112730.05244.5144
#Mann= 3 , 0 , 0
7136.752  0.0442       07136.752  0.0442       012730.05  0.0442       0
#XS Ineff= 2 , 0
       09544.712        11207.77       0
Bank Sta=7136.752,12730.05
Exp/Cntr=0.3,0.1

Type RM Length L Ch R = 1 ,113139.4,987.196900,987.196900,987.196900
XS GIS Cut Line= 6
797847.871398223817652.858827395799550.239853621819457.755326167
799938.288065404819745.894317746800620.651082069820094.791249871
 800979.98580119820323.668722048801960.879889816821237.131418213
#Sta/Elev= 30
 6501.09310.08726650.457 299.3856821.896245.9724 7143.53248.42657218.408229.4605
7425.513 201.1927500.237179.85477970.463 181.8638227.737208.94938469.569190.4449
8812.759201.68428922.614218.33879159.348217.47849184.599207.53749319.577198.9124
  9510.1201.12889566.438171.41989736.317166.18679847.353131.922310160.14132.0648
10704.62 152.62110768.36146.703210832.64148.971110897.38167.971711098.45167.7714
11221.33185.610211346.35179.034511715.47244.316811867.01252.207212002.19299.6874
#Mann= 3 , 0 , 0
 6501.09  0.0319       0 6501.09  0.0319       012002.19  0.0319       0
#XS Ineff= 2 , 0
       09340.164        10872.13       0
Bank Sta=6501.09,12002.19
Exp/Cntr=0.3,0.1

Type RM Length L Ch R = 1 ,112152.2,987.196900,987.196900,987.196900
XS GIS Cut Line= 6
797726.991761774 817811.62611112798548.609692276818723.488435462
799371.926561087819863.016896427799573.868326962820262.269064263
799764.172036767820946.940290332800059.581502287821619.303658363
#Sta/Elev= 30
6586.367258.1072 6619.55254.37366733.124270.14116910.307244.50116997.747215.0702
7026.276 218.8917066.241240.37577115.193238.19697361.135182.30447662.124181.7731
 7765.09197.00738032.493193.78938233.262218.9543 8396.28207.38048681.027210.4243
8840.179196.39889009.886201.66869140.723183.96719441.286162.05639618.062161.8154
9756.875 137.7459850.975131.922310127.81131.922310189.95146.262810325.91 149.862
10399.81135.646510549.38137.191710898.36226.681111031.89280.911711115.67337.8537
#Mann= 3 , 0 , 0
6586.367  0.0311       06586.367  0.0311       011115.67  0.0311       0
#XS Ineff= 2 , 0
       0                               0
Bank Sta=6586.367,11115.67
Exp/Cntr=0.3,0.1

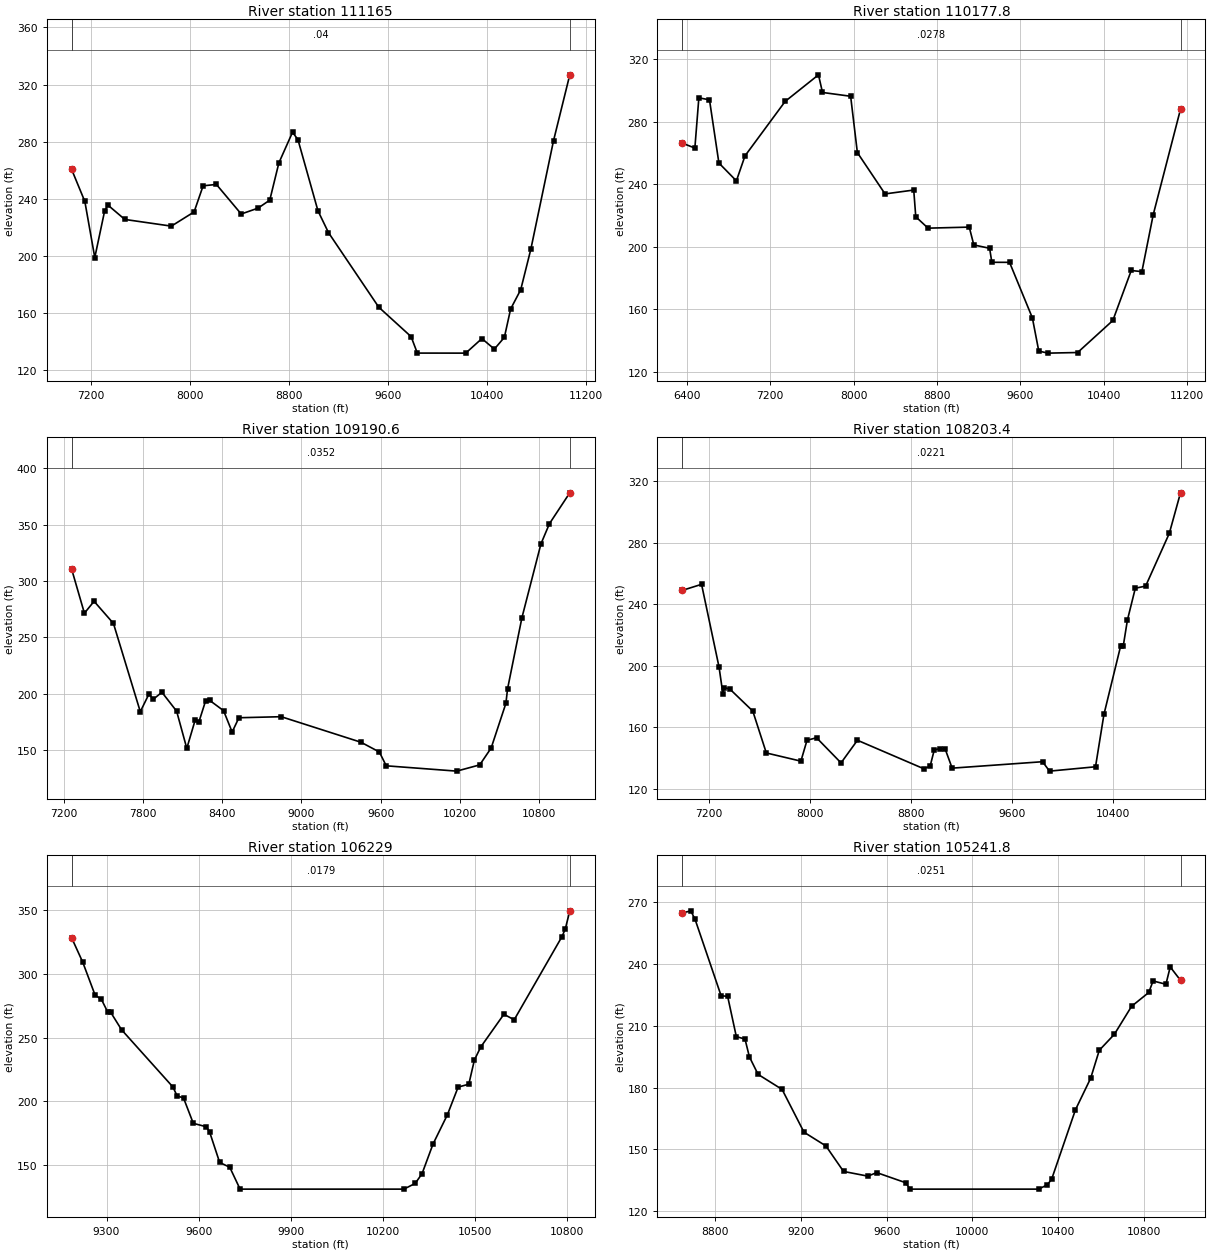
Type RM Length L Ch R = 1 ,  111165,987.196900,987.196900,987.196900
XS GIS Cut Line= 6
797420.108471096818177.036019877798078.541716009818998.174435228
798489.902816892819767.491947964798651.490816861820329.515312806
798737.775204301821248.976921126798861.501382309821819.779216291
#Sta/Elev= 30
7046.453260.67717153.607238.1237 7233.81198.85617314.013231.77457340.748235.5255
7476.346225.55517851.985220.8687 8035.73230.82248108.372249.10098215.445250.0804
8415.992229.3594 8551.72233.46868646.596239.0823 8720.01265.14848830.296286.6273
 8874.13281.43079035.717231.57519120.707216.30439526.497164.10029787.641143.4651
9837.818131.9508 10228.6 131.91810359.12142.105810459.84134.742110540.63142.9743
 10591.2162.852110672.45176.295510754.02204.594510937.27280.641711068.72326.8422
#Mann= 3 , 0 , 0
7046.453    0.04       07046.453    0.04       011068.72    0.04       0
#XS Ineff= 2 , 0
       0                               0
Bank Sta=7046.453,11068.72
Exp/Cntr=0.3,0.1

Type RM Length L Ch R = 1 ,110177.8,987.196900,987.196900,987.196900
XS GIS Cut Line= 6
795709.733335495817957.862519592796647.081337929818804.420793861
 797289.48658973  819673.2787617797633.689395458820448.332992777
797792.818563491821319.205895737798021.737327933821976.369386271
#Sta/Elev= 30
6355.292 266.3796475.901263.26516514.165 295.4246616.204294.16576706.565253.6695
6874.437242.22826957.047258.2417 7342.69293.15027662.341 310.1687700.838298.8681
7970.992296.43638035.608260.33318301.177233.87118576.589236.34758596.176219.2168
8713.994211.92969109.456212.59689153.261201.17529304.885199.0221 9326.25190.0497
9496.141190.02689715.218154.46229776.826133.12469868.342131.856710149.72132.2492
 10487.5152.762210664.26184.8012 10766.4184.064110875.23220.571511137.02288.1279
#Mann= 3 , 0 , 0
6355.292  0.0278       06355.292  0.0278       011137.02  0.0278       0
#XS Ineff= 2 , 0
       0                               0
Bank Sta=6355.292,11137.02
Exp/Cntr=0.3,0.1

Type RM Length L Ch R = 1 ,109190.6,987.196900,987.196900,987.196900
XS GIS Cut Line= 6
794844.248985082819433.112924963795524.468660504819936.584019467
796080.179793298820439.637877166796390.814144611820769.710724607
796913.788170427821387.671931788797476.881687015822110.799910188
#Sta/Elev= 30
 7257.21310.76147354.409271.52027427.709  282.077574.548262.44517778.069184.2158
7843.596199.82747876.359195.16847941.764201.47368053.441184.68438130.608151.6879
 8194.82177.13288221.908175.0029 8272.35193.5308 8302.83194.34528409.275185.1172
8474.309166.19018525.614178.85598846.423179.77569451.405 157.1169590.284148.4934
9642.157136.2549 10176.5131.538110350.97137.069810437.69152.054610549.37191.6343
10561.89204.404910670.83267.522410814.84332.909810879.48350.859511033.61378.2084
#Mann= 3 , 0 , 0
 7257.21  0.0352       0 7257.21  0.0352       011033.61  0.0352       0
#XS Ineff= 2 , 0
       09607.043                       0
Bank Sta=7257.21,11033.61
Exp/Cntr=0.3,0.1

Type RM Length L Ch R = 1 ,108203.4,1974.393800,1974.393800,1974.393800
XS GIS Cut Line= 6
793401.604415208820875.757494837794218.954371274821180.663871109
794783.395275265821408.135350794795752.311439812821828.195176467
796541.568152487822197.962070346797038.526366323822388.383139357
#Sta/Elev= 30
6991.294249.09627143.648253.03567281.936199.21257312.494181.76987324.596185.8798
7370.038184.69357548.872170.56227655.973143.31497929.535 137.9877977.829151.5667
8053.165153.21948247.099136.85558376.753151.58358901.244133.05878951.723134.6906
8984.462145.26539028.028146.17349071.593145.7008 9126.05133.43429841.132 137.619
9896.452131.495810260.16134.3276 10326.8 168.40510458.37212.723610480.16213.1707
10512.51229.784310574.99250.501410656.69251.895310843.97286.2207 10932.5312.5664
#Mann= 3 , 0 , 0
6991.294  0.0221       06991.294  0.0221       0 10932.5  0.0221       0
#XS Ineff= 2 , 0
       09605.388                       0
Bank Sta=6991.294,10932.5
Exp/Cntr=0.3,0.1

Type RM Length L Ch R = 1 ,  106229,987.196900,987.196900,987.196900
XS GIS Cut Line= 6
795798.887671143824158.390643239796025.167780489824121.250651345
796317.927051187 824018.74755381796556.922727019823887.783201963
796968.749306917823631.696911067797258.354687397823485.854128367
#Sta/Elev= 30
9186.183328.39749222.517 309.1749262.885283.27959283.092280.13189303.325270.3492
9313.485269.90139348.833256.23079516.073211.35439529.695204.41829550.823202.6204
9582.513182.81589625.262180.11379636.035175.74799668.354152.15129701.235148.3936
9734.824131.233310268.24131.233310305.14135.733210327.39143.349310362.88166.4578
10410.01189.598710444.83 211.22410479.64213.514410497.83232.483110518.49242.6889
10593.82 268.33110627.44264.0267   10783329.230410793.88335.251310808.42349.4538
#Mann= 3 , 0 , 0
9186.183  0.0179       09186.183  0.0179       010808.42  0.0179       0
#XS Ineff= 2 , 0
       0                               0
Bank Sta=9186.183,10808.42
Exp/Cntr=0.3,0.1

Type RM Length L Ch R = 1 ,105241.8,1974.393800,1974.393800,1974.393800
XS GIS Cut Line= 6
795575.896279603824475.456528068796097.371650666824565.794273838
796804.138839513 824740.03432937797478.771876484824841.407296747
797671.471391588824859.427700818797863.026783397824865.860230406
#Sta/Elev= 30
8645.969264.75078685.469265.81648705.672261.65268827.137224.59128857.529224.3225
8898.057204.79358938.708203.53418959.033194.96118999.684186.43089111.711179.1322
9213.817 158.3759316.215151.70579398.418139.32799511.981137.0453 9553.31138.7619
9688.161133.85949708.911130.741210308.87130.741210349.43132.830410369.71135.5878
10480.94169.299510551.64184.542110592.02198.139410662.39205.885610742.74219.4804
 10822.9226.183210842.93231.793910902.97230.173410922.97238.579110971.01232.0909
#Mann= 3 , 0 , 0
8645.969  0.0251       08645.969  0.0251       010971.01  0.0251       0
#XS Ineff= 2 , 0
       0                               0
Bank Sta=8645.969,10971.01
Exp/Cntr=0.3,0.1

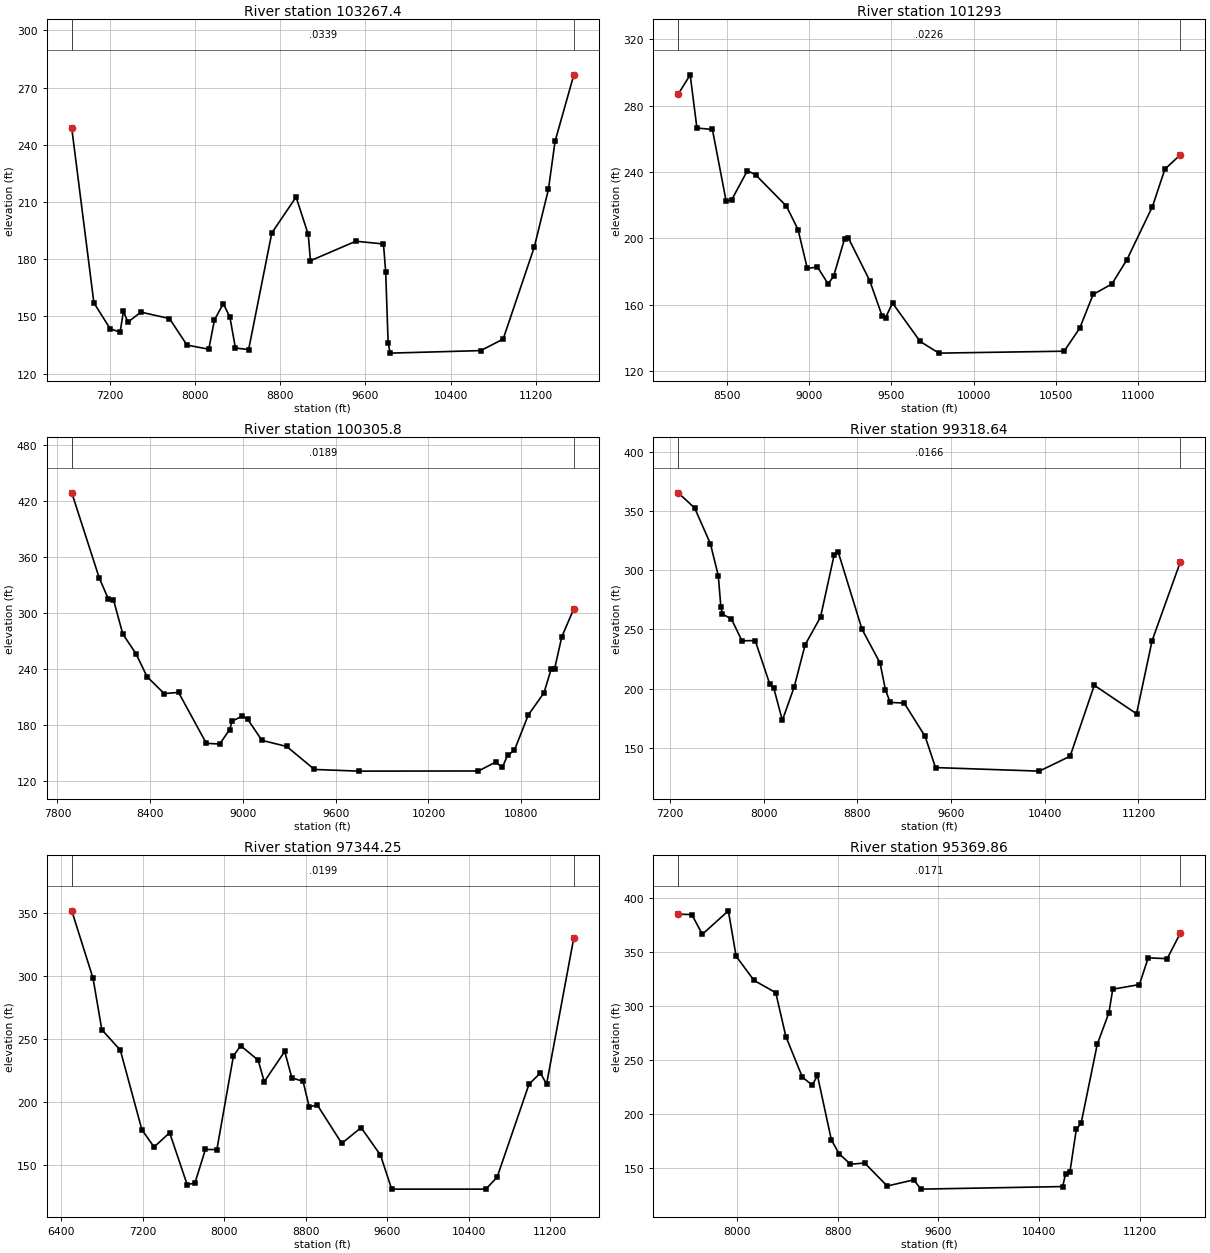
Type RM Length L Ch R = 1 ,103267.4,1974.393800,1974.393800,1974.393800
XS GIS Cut Line= 6
792862.511930943826992.125646889794245.322848767826661.330508202
796271.415771067  826119.4778658796489.646382451826081.867683738
797041.481961906826029.036321744797446.373006165825938.991143614
#Sta/Elev= 30
6844.568 248.6467051.986157.13187205.844143.43767298.297141.77257329.115152.5835
7371.681147.03977493.477152.23897760.959148.87677925.714134.95478129.805132.7974
8183.598 148.2018266.142156.67848328.169149.63538379.859133.42958503.915 132.598
8721.146193.7263    8949212.58599063.168192.96049083.926179.19479509.461189.4057
9768.934187.98979789.691173.35589812.648136.14539831.207130.741210681.22132.0621
 10891.9138.103111183.98186.369811316.27 216.55811379.02241.858611554.99276.6741
#Mann= 3 , 0 , 0
6844.568  0.0339       06844.568  0.0339       011554.99  0.0339       0
#XS Ineff= 2 , 0
       09636.583                       0
Bank Sta=6844.568,11554.99
Exp/Cntr=0.3,0.1

Type RM Length L Ch R = 1 ,  101293,987.196900,987.196900,987.196900
XS GIS Cut Line= 6
796649.517500525828807.175223725796998.066473514 828388.99598524
797220.695909798 828003.05102779797380.059430629827584.873032853
797647.853533447826556.020772114797936.671291143826093.852934882
#Sta/Elev= 30
8204.925286.91078277.525298.55588318.421266.47838412.691265.60598496.243222.2492
8530.258223.27998625.326240.79558676.168238.18048862.551219.34938932.873205.2606
8989.518181.80059051.013182.6669 9115.82  172.489149.316177.10599215.814 199.689
9237.711200.39549368.507 174.4589443.419 153.357 9464.77152.09939507.165 160.947
9674.947137.80689788.978130.741210550.21 131.90710645.33145.875410726.44166.1377
10840.77172.4616 10932.2 187.15611086.82219.104211162.47241.658311256.25250.3269
#Mann= 3 , 0 , 0
8204.925  0.0226       08204.925  0.0226       011256.25  0.0226       0
#XS Ineff= 2 , 0
       0                               0
Bank Sta=8204.925,11256.25
Exp/Cntr=0.3,0.1

Type RM Length L Ch R = 1 ,100305.8,987.196900,987.196900,987.196900
XS GIS Cut Line= 6
797212.600904295829226.775461934797652.809825033828826.689640522
797993.311595291828371.441611022 798208.46805805827967.107586563
798723.905664951826815.043320507798899.855446219826498.091583684
#Sta/Elev= 30
7892.853429.07018070.539337.80598129.133315.30648162.234314.57828222.941277.6888
8309.034256.26078379.958231.84338490.679 213.7368583.547215.01088763.332160.3684
8850.016159.65248913.489175.02478931.347184.28458994.468189.43059029.937186.4333
9123.006 163.6049283.419156.99839462.683132.36999749.318130.578610523.98130.7411
10634.13140.201210678.48134.653210711.74 147.391 10756.1 152.87510845.98 190.748
10947.64214.539210993.55239.6726 11016.5 240.50811062.83274.595411140.85304.7715
#Mann= 3 , 0 , 0
7892.853  0.0189       07892.853  0.0189       011140.85  0.0189       0
#XS Ineff= 2 , 0
       0                               0
Bank Sta=7892.853,11140.85
Exp/Cntr=0.3,0.1

Type RM Length L Ch R = 1 ,99318.64,1974.393800,1974.393800,1974.393800
XS GIS Cut Line= 6
797229.225254446829684.130305603798165.714051872829187.188916251
798663.690670639828800.089944437798985.636640161828413.009304956
799770.273327589827236.638139129800192.755766839826709.966972694
#Sta/Elev= 30
7271.008365.23787411.278352.44857545.551322.31797612.886295.42817635.332268.5992
7648.646262.96357725.113258.88677814.894240.46477928.003240.67798053.143203.7507
8087.502200.30428159.891173.36578260.831201.50928354.575237.15618485.914 260.486
8602.472313.0366 8635.84315.60648839.781250.25328994.366221.63179040.171 198.967
9081.049188.52239200.428187.94259378.463159.90249467.705133.575310353.71130.5772
10616.89143.1702   10823 202.967 11183.8178.917311316.75 240.64911557.42306.8716
#Mann= 3 , 0 , 0
7271.008  0.0166       07271.008  0.0166       011557.42  0.0166       0
#XS Ineff= 2 , 0
       0                               0
Bank Sta=7271.008,11557.42
Exp/Cntr=0.3,0.1

Type RM Length L Ch R = 1 ,97344.25,1974.393800,1974.393800,1974.393800
XS GIS Cut Line= 6
 797181.13559261829895.953816012798019.163981616829589.508889124
798795.354437917829414.281323671799462.698432177829358.249672875
800496.319238365829348.917143375802017.837623776829134.071408027
#Sta/Elev= 30
6501.007351.91686710.201298.18386796.041 257.3946977.701241.13627189.723177.7574
7309.263164.05987462.172175.44347634.373134.1029 7710.73135.48767813.323 162.145
7925.795     1628088.467236.46058159.369244.64918330.942233.16618391.279216.0182
8592.071240.07778662.205219.05828772.335216.30878832.406196.0706 8912.45197.4488
  9152.5166.96789342.502179.49479532.504157.66189642.505130.5772 10567.4130.5772
10678.17140.083110991.34214.070811102.86222.963111163.73214.057211431.49330.6182
#Mann= 3 , 0 , 0
6501.007  0.0199       06501.007  0.0199       011431.49  0.0199       0
#XS Ineff= 2 , 0
       08905.925                       0
Bank Sta=6501.007,11431.49
Exp/Cntr=0.3,0.1

Type RM Length L Ch R = 1 ,95369.86,1974.393800,1974.393800,1974.393800
XS GIS Cut Line= 6
797082.121041775830332.089337572 797845.03559646830159.162996024
798565.981831998830209.752324477799057.150550753830447.859237403
799835.961718917831142.956071869800689.304018727 831267.47921804
#Sta/Elev= 30
7535.722384.95357643.577384.61997726.666366.36387933.223388.07887994.883346.0595
 8137.41 323.651 8309.18 312.3618389.471271.78688519.694234.31738599.699226.6808
8639.752235.87288750.025176.24678810.463163.45588901.669153.63479014.428154.7338
9193.176133.43949403.548139.15669460.709130.577210585.03132.954410607.76144.6298
 10642.7146.635910693.27185.897310731.38191.5788 10859.1264.456510951.73293.8473
10982.18315.529611193.55319.8491 11263.6344.597511413.65343.790511518.09367.3295
#Mann= 3 , 0 , 0
7535.722  0.0171       07535.722  0.0171       011518.09  0.0171       0
#XS Ineff= 2 , 0
       09074.824                       0
Bank Sta=7535.722,11518.09
Exp/Cntr=0.3,0.1

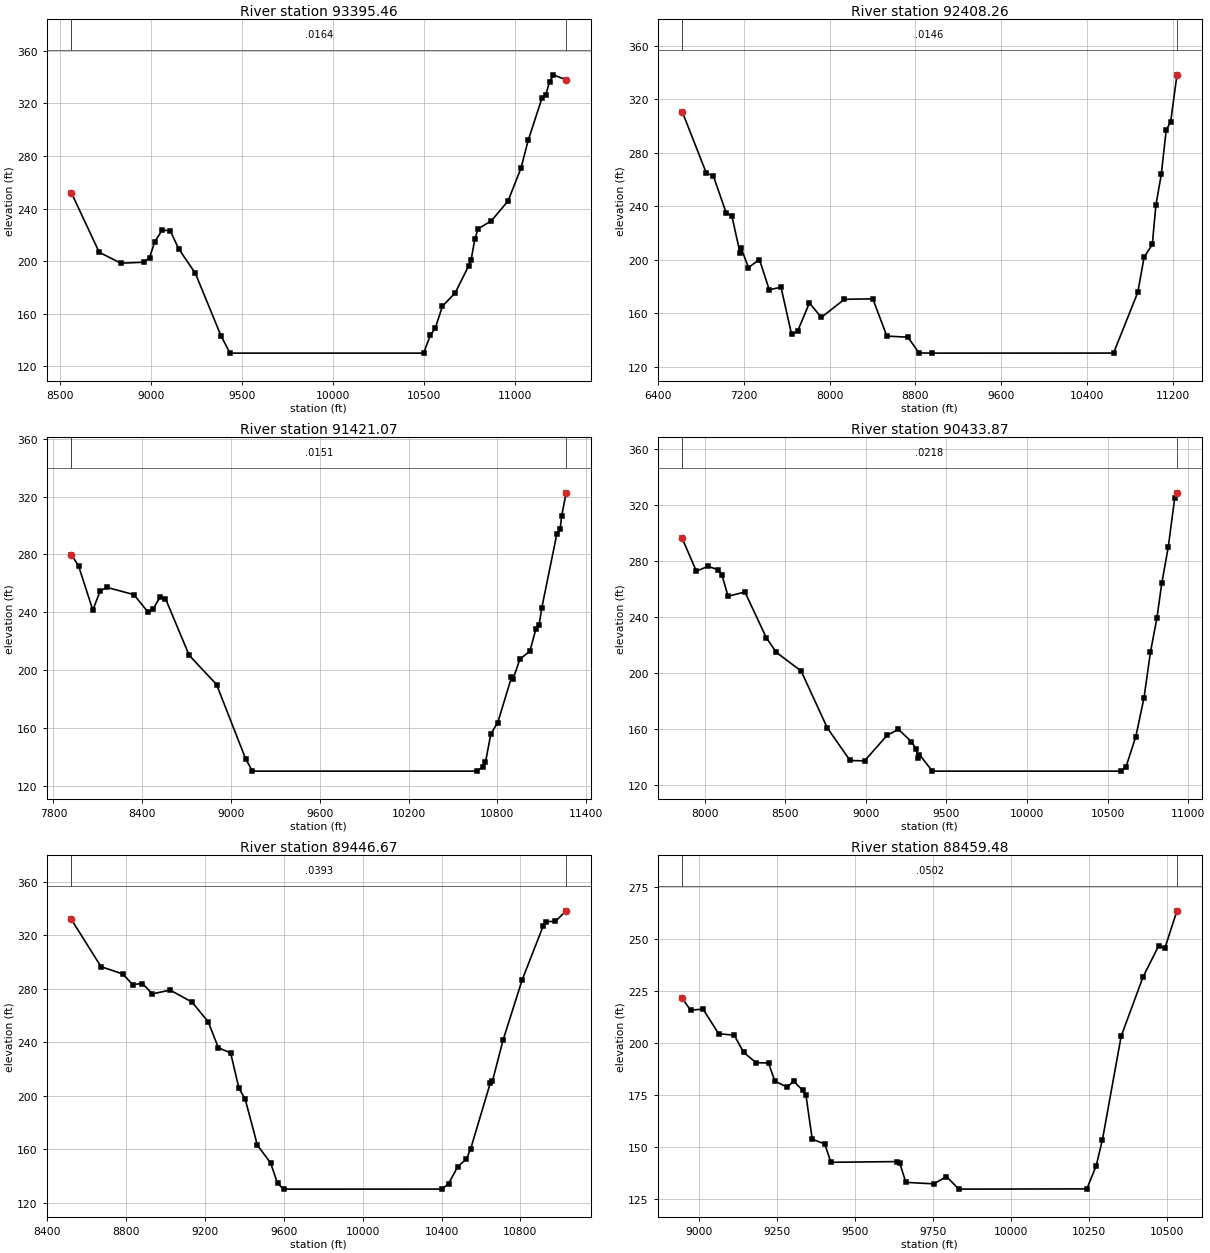
Type RM Length L Ch R = 1 ,93395.46,987.196900,987.196900,987.196900
XS GIS Cut Line= 6
798986.049486503833360.304796587799326.455413312833055.496680975
799581.291425467832747.365523025800159.425029039831736.614563376
800436.988180846831515.335413262800751.392387867831389.356387079
#Sta/Elev= 30
8560.245252.02698713.382206.75698832.588 198.5158958.591199.23618990.198202.7674
9018.281214.70419059.241223.60189103.786223.22069149.901209.57529242.131190.7867
9383.392 143.1669432.687130.085110497.55130.085110535.39143.931810561.45148.9654
10601.24165.819310671.02175.876410746.27196.668110759.27201.236910778.85216.5597
10797.17224.665310870.03230.656210962.31245.898111033.04270.731611072.74291.8797
11148.23323.900911168.15326.145911190.52336.359511211.67341.800811281.48338.0029
#Mann= 3 , 0 , 0
8560.245  0.0164       08560.245  0.0164       011281.48  0.0164       0
#XS Ineff= 2 , 0
       09055.502                       0
Bank Sta=8560.245,11281.48
Exp/Cntr=0.3,0.1

Type RM Length L Ch R = 1 ,92408.26,987.196900,987.196900,987.196900
XS GIS Cut Line= 6
798076.998151094834609.188533872799399.442878544834026.455726594
800056.522151142833599.219047949   800465.081781833151.657178864
801057.041659474832205.346724674801533.302289009831767.741371304
#Sta/Elev= 30
6629.074310.83376853.449264.79886918.172262.84657036.831235.36387091.394 232.629
7167.163205.00117178.024208.60237245.116194.12197347.597200.1441 7438.89177.5377
 7548.32179.43687647.182144.0451 7702.26146.33687812.853167.68597923.952156.8393
8137.972170.36148403.109170.75288533.646142.85078730.022142.01068832.432130.2491
8951.631130.085110643.99130.128810869.76 175.61310928.46201.912511004.96211.4632
 11038.4240.859611088.88264.1445 11134.2297.008111175.82303.361211234.54338.4502
#Mann= 3 , 0 , 0
6629.074  0.0146       06629.074  0.0146       011234.54  0.0146       0
#XS Ineff= 2 , 0
       09248.166                       0
Bank Sta=6629.074,11234.54
Exp/Cntr=0.3,0.1

Type RM Length L Ch R = 1 ,91421.07,987.196900,987.196900,987.196900
XS GIS Cut Line= 6
799659.179464408834232.595802579800537.591249019833901.511882395
800927.287484765833716.305732787801185.733470827833549.115683064
801963.267493337832978.169325173802571.642755657832632.844095841
#Sta/Elev= 30
7921.367 279.9067970.215271.94398066.162241.50468116.405254.87518162.108257.2097
8343.341252.20848439.287240.1395 8471.27241.9179 8519.73250.3162  8556.8 249.519
8717.395  210.218902.482189.98799098.499138.68929144.705130.0851 10662.7130.0851
10700.52133.102410719.69136.207510755.94155.811210802.83163.721310895.42194.9507
10906.84193.980710952.51207.611611019.78 213.03711061.22 228.75111082.68231.4803
11100.48243.131111201.54293.846111223.85297.4443   11235306.784911264.73322.6332
#Mann= 3 , 0 , 0
7921.367  0.0151       07921.367  0.0151       011264.73  0.0151       0
#XS Ineff= 2 , 0
       09262.193                       0
Bank Sta=7921.367,11264.73
Exp/Cntr=0.3,0.1

Type RM Length L Ch R = 1 ,90433.87,987.196900,987.196900,987.196900
XS GIS Cut Line= 6
799711.332440555834314.942606956800463.077364773834122.798827291
801043.938137174834068.277907267801420.683957905834102.326312959
802116.430401236 834290.63295278802719.140479435834375.069713247
#Sta/Elev= 30
7860.539296.02387947.979272.61478020.969276.19748083.405273.59898107.245269.8131
8144.628254.77758249.299257.80318383.293224.94718444.819214.71368598.086201.5122
8760.475160.96098901.606137.67828992.003137.41649132.216 155.7029202.225159.8294
9282.267151.11379312.288145.73299322.295139.16519332.302141.90119412.491130.0851
10584.27130.085110614.64 133.31610675.12154.733310725.52182.115210765.78214.8748
10805.98239.218810836.09264.041710876.19289.694810916.29324.621710930.46328.5263
#Mann= 3 , 0 , 0
7860.539  0.0218       07860.539  0.0218       010930.46  0.0218       0
#XS Ineff= 2 , 0
       09156.001                       0
Bank Sta=7860.539,10930.46
Exp/Cntr=0.3,0.1

Type RM Length L Ch R = 1 ,89446.67,987.196800,987.196800,987.196800
XS GIS Cut Line= 6
799855.252977908834662.895057231800295.686727762 834654.14820677
800679.798436791834728.581470713801040.103913099834887.731929272
 801667.42827031835265.553732321802177.097096627835463.789328194
#Sta/Elev= 30
8523.649331.60338673.881296.33158783.959290.89298833.959282.99548883.994 283.764
8934.072276.01399024.457278.85269135.585269.8109 9217.19255.14119268.707235.7546
9331.006231.85469372.984205.46389404.797 197.3179466.308163.00529533.496149.6453
9568.888134.39069599.492130.085110402.05 130.09810435.99134.240410482.81146.9864
10525.78152.495110548.03160.250910647.22209.372110658.02210.672910712.05241.4543
10808.83286.453710914.64326.393310930.87330.022410977.46330.184211031.76338.0841
#Mann= 3 , 0 , 0
8523.649  0.0393       08523.649  0.0393       011031.76  0.0393       0
#XS Ineff= 2 , 0
       09376.067                       0
Bank Sta=8523.649,11031.76
Exp/Cntr=0.3,0.1

Type RM Length L Ch R = 1 ,88459.48,130.541700,130.541700,130.541700
XS GIS Cut Line= 5
799938.357569933 835913.72339797800210.261009037 835910.72737053
800638.661068976 835930.82289575800924.405975372835938.636233017
801523.800564259835960.960053831
#Sta/Elev= 30
8945.287221.49268971.931215.83929011.933216.30099061.936204.51039111.939203.8208
9141.941195.59059181.943190.64289221.951190.45419241.973181.85019282.017178.8342
9302.039181.78429332.072177.29459342.083174.89659362.105153.91799402.149151.6309
9422.171142.84319632.402143.17189642.413 142.5929662.423133.20999752.456132.4934
9792.471135.99189832.486129.966210242.74130.085110272.76141.247110292.77153.6967
10352.81203.333410422.86231.7136 10472.9246.673410492.91 245.58310531.74263.4722
#Mann= 3 , 0 , 0
8945.287  0.0502       08945.287  0.0502       010531.74  0.0502       0
#XS Ineff= 2 , 0
       0                               0
Bank Sta=8945.287,10531.74
Exp/Cntr=0.3,0.1

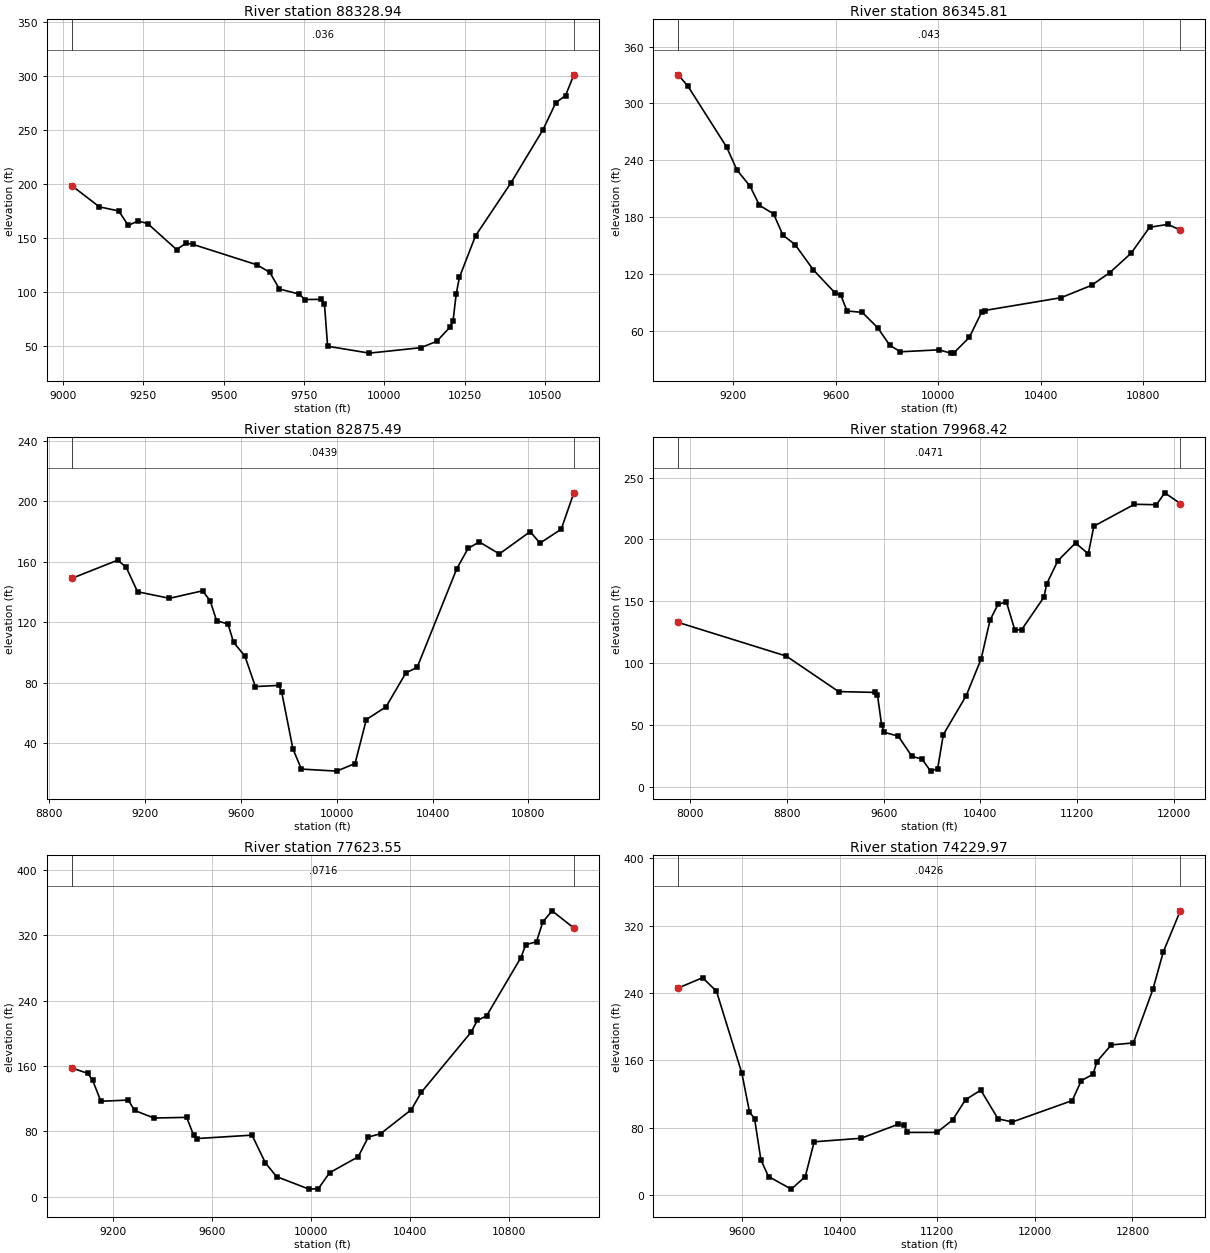
Type RM Length L Ch R = 1 ,88328.94,1983.120600,1983.120600,1983.120600
XS GIS Cut Line= 3
800019.096357942836039.080989808800431.313307762836053.220962152
801580.890862048836091.160815403
#Sta/Elev= 30
9027.086198.3326 9113.04178.69289173.075174.90919203.093161.51539233.111165.6664
9263.128163.27749353.181139.17559383.199145.09549403.211144.06239603.321125.0484
9643.343118.07549673.359102.65539733.39298.084239753.40392.93735 9803.4393.07272
9813.43589.105849823.44149.686789953.51243.31613 10113.648.3536810163.6354.34935
10203.6567.1898910213.6572.9098510223.6698.1463410233.66113.490710283.69151.8795
10393.75200.802410493.81 250.16810533.83275.176710563.84281.652210589.75300.8877
#Mann= 3 , 0 , 0
9027.086   0.036       09027.086   0.036       010589.75   0.036       0
#XS Ineff= 2 , 0
       0                               0
Bank Sta=9027.086,10589.75
Exp/Cntr=0.3,0.1

Type RM Length L Ch R = 1 ,86345.81,3470.319600,3470.319600,3470.319600
XS GIS Cut Line= 2
800612.724713594838487.888742372802255.484442294837419.492439598
#Sta/Elev= 30
 8985.67 330.2019024.171317.88899174.386253.95779215.033229.56349266.095212.4741
9302.778192.27269357.804183.26869393.966160.92169441.681150.80789513.254 123.995
9596.246100.14319620.61497.044989644.47280.657699704.11679.13487 9763.7663.03742
9811.47644.377769853.03137.5211110002.3439.5688610050.05 36.100510061.9836.56189
10121.6352.6522910169.3479.1145510181.2781.1469310479.4994.6665510598.78107.7517
10670.35121.247510753.86141.862210825.43169.1102   10897172.1681 10945.3166.1283
#Mann= 3 , 0 , 0
 8985.67   0.043       0 8985.67   0.043       0 10945.3   0.043       0
#XS Ineff= 2 , 0
       0                               0
Bank Sta=8985.67,10945.3
Exp/Cntr=0.3,0.1

Type RM Length L Ch R = 1 ,82875.49,2907.076300,2907.076300,2907.076300
XS GIS Cut Line= 2
803161.977254987840311.236401647804939.755032778839200.125290558
#Sta/Elev= 30
8893.127 149.0679085.371161.15629120.749156.30419167.919140.19829301.121135.8592
9439.146140.81859470.933134.22189498.108120.94399545.278118.93849568.863106.6744
9616.03397.634759659.613 77.44469757.54378.194559769.33574.098629816.50536.20196
9851.88222.811329999.23621.4556810075.9426.4865210123.1155.6011310205.6664.09174
 10288.286.4724110335.3790.1629310500.47155.342110547.64168.863510594.81173.2063
10678.48165.260310807.07  179.9810848.29172.428410936.79181.602510989.57205.7018
#Mann= 3 , 0 , 0
8893.127  0.0439       08893.127  0.0439       010989.57  0.0439       0
#XS Ineff= 2 , 0
       0                               0
Bank Sta=8893.127,10989.57
Exp/Cntr=0.3,0.1

Type RM Length L Ch R = 1 ,79968.42,2344.865500,2344.865500,2344.865500
XS GIS Cut Line= 6
804160.490061145842241.756943776804876.577520869842161.932975001
805208.237549152842076.191480529805515.119494574 841960.29225333
805821.878647374841804.327160964807915.688105521840594.710768402
#Sta/Elev= 30
7899.645132.99368793.968105.79859226.82577.147579525.558 76.48379548.38474.45215
9582.62350.059889605.44944.237879720.76241.116829833.36924.852449917.53222.56684
 9987.5812.8936710046.4114.9270110093.3142.4035210282.7573.8504310406.54103.6025
10480.02134.907110545.75147.494810615.03 149.66310684.08127.154110740.38126.9619
 10925.7153.374810948.65164.078111040.46182.734911187.36197.174211292.93188.3646
11338.84210.714711675.12228.423811856.52228.057511925.86237.669812054.38228.9994
#Mann= 3 , 0 , 0
7899.645  0.0471       07899.645  0.0471       012054.38  0.0471       0
#XS Ineff= 2 , 0
       0                               0
Bank Sta=7899.645,12054.38
Exp/Cntr=0.3,0.1

Type RM Length L Ch R = 1 ,77623.55,3393.585200,3393.585200,3393.585200
XS GIS Cut Line= 2
804703.643921673843123.736401662806314.755032778844352.903068319
#Sta/Elev= 30
9035.587157.63269100.183150.92419120.102142.26529153.075116.76679263.697118.2552
9288.853105.57439367.39996.25953 9499.2997.048099527.83574.869319540.41371.11542
9763.07375.276799817.129 41.27699861.992 24.48399993.2229.15352410030.969.800838
10076.3229.2479310191.7248.79935 10232.272.9084310282.5277.0979410406.04106.4754
10446.03127.606710647.28201.435910672.43215.717810710.17221.568810848.53292.8588
10867.66308.426210911.42312.280510936.57336.307510974.31350.049411062.04328.9479
#Mann= 3 , 0 , 0
9035.587  0.0716       09035.587  0.0716       011062.04  0.0716       0
#XS Ineff= 2 , 0
       0                               0
Bank Sta=9035.587,11062.04
Exp/Cntr=0.3,0.1

Type RM Length L Ch R = 1 ,74229.97,2704.737100,2704.737100,2704.737100
XS GIS Cut Line= 3
802023.088366121845950.125290558 803745.31058836845464.014179423
805925.866143882844658.458623901
#Sta/Elev= 30
9078.465246.01339277.875258.21899391.835242.17429599.987 144.7329662.33198.83039
9703.894 90.94979755.848 41.93429818.19222.1751610005.227.21816310119.5222.14401
10192.2663.4044710576.7167.6181310878.3184.0815210931.6183.3727410952.9374.57181
11198.1274.5517511326.8489.3360311432.66113.4036 11557.7124.732911699.1790.62605
11816.4486.9641912306.82112.339812381.45136.060512477.39143.543812509.37158.6605
12626.64178.449312807.87180.790112967.78244.299413053.06288.844313192.57337.6263
#Mann= 3 , 0 , 0
9078.465  0.0426       09078.465  0.0426       013192.57  0.0426       0
#XS Ineff= 2 , 0
       0                               0
Bank Sta=9078.465,13192.57
Exp/Cntr=0.3,0.1