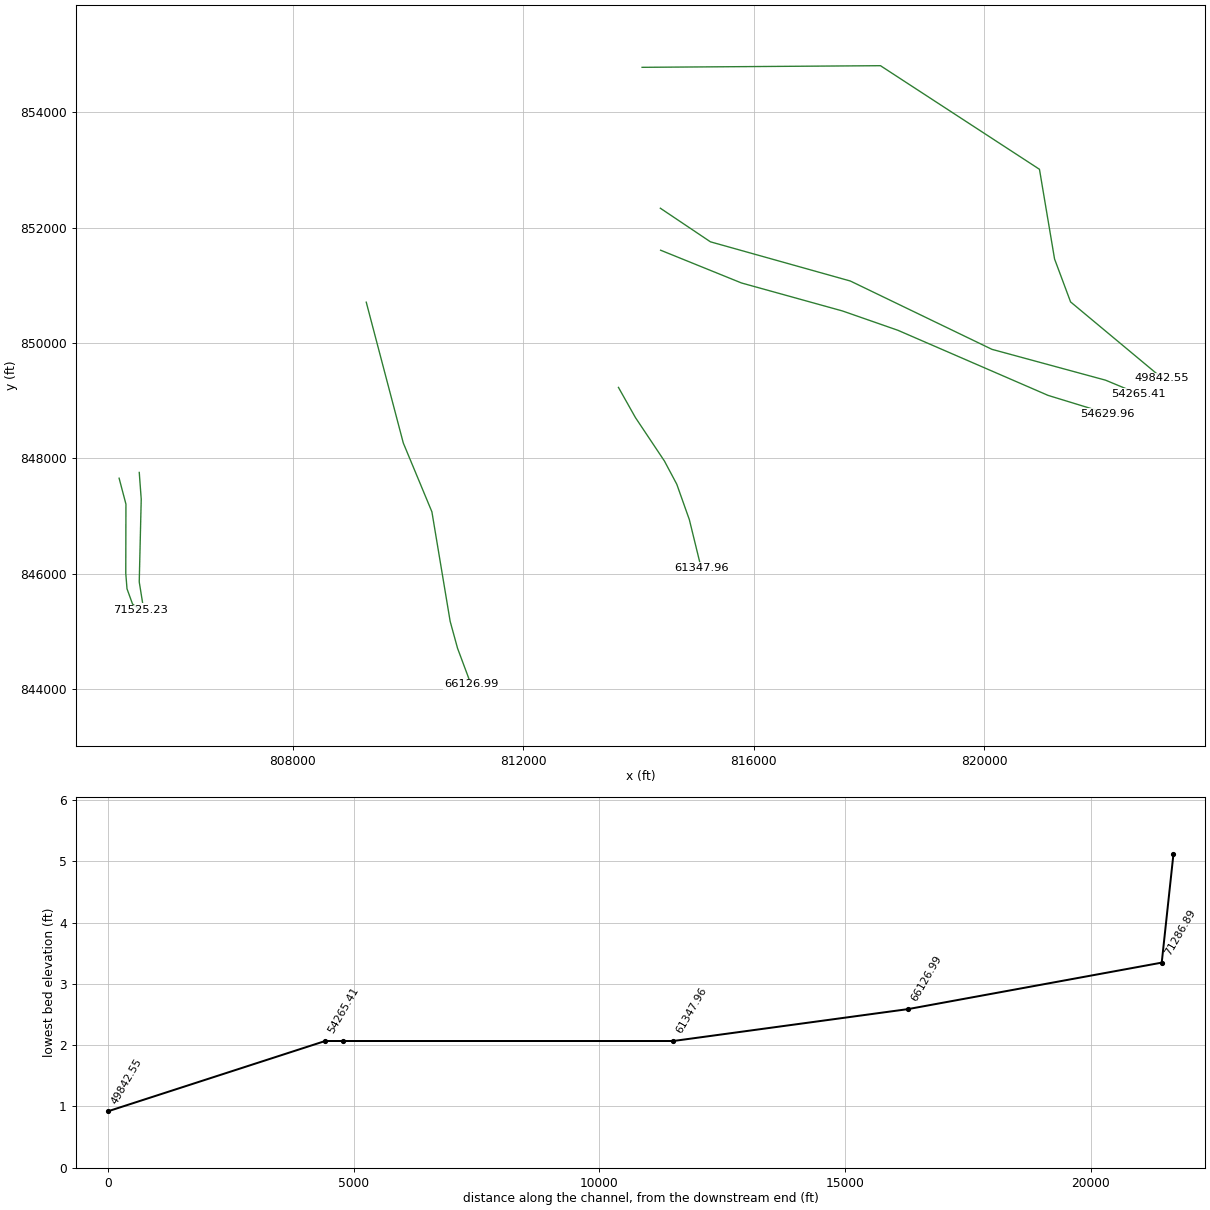
HEC-RAS study 17203_ras.prj: 17203

--- 17203_ras.g01 (geometry) --- (continued)

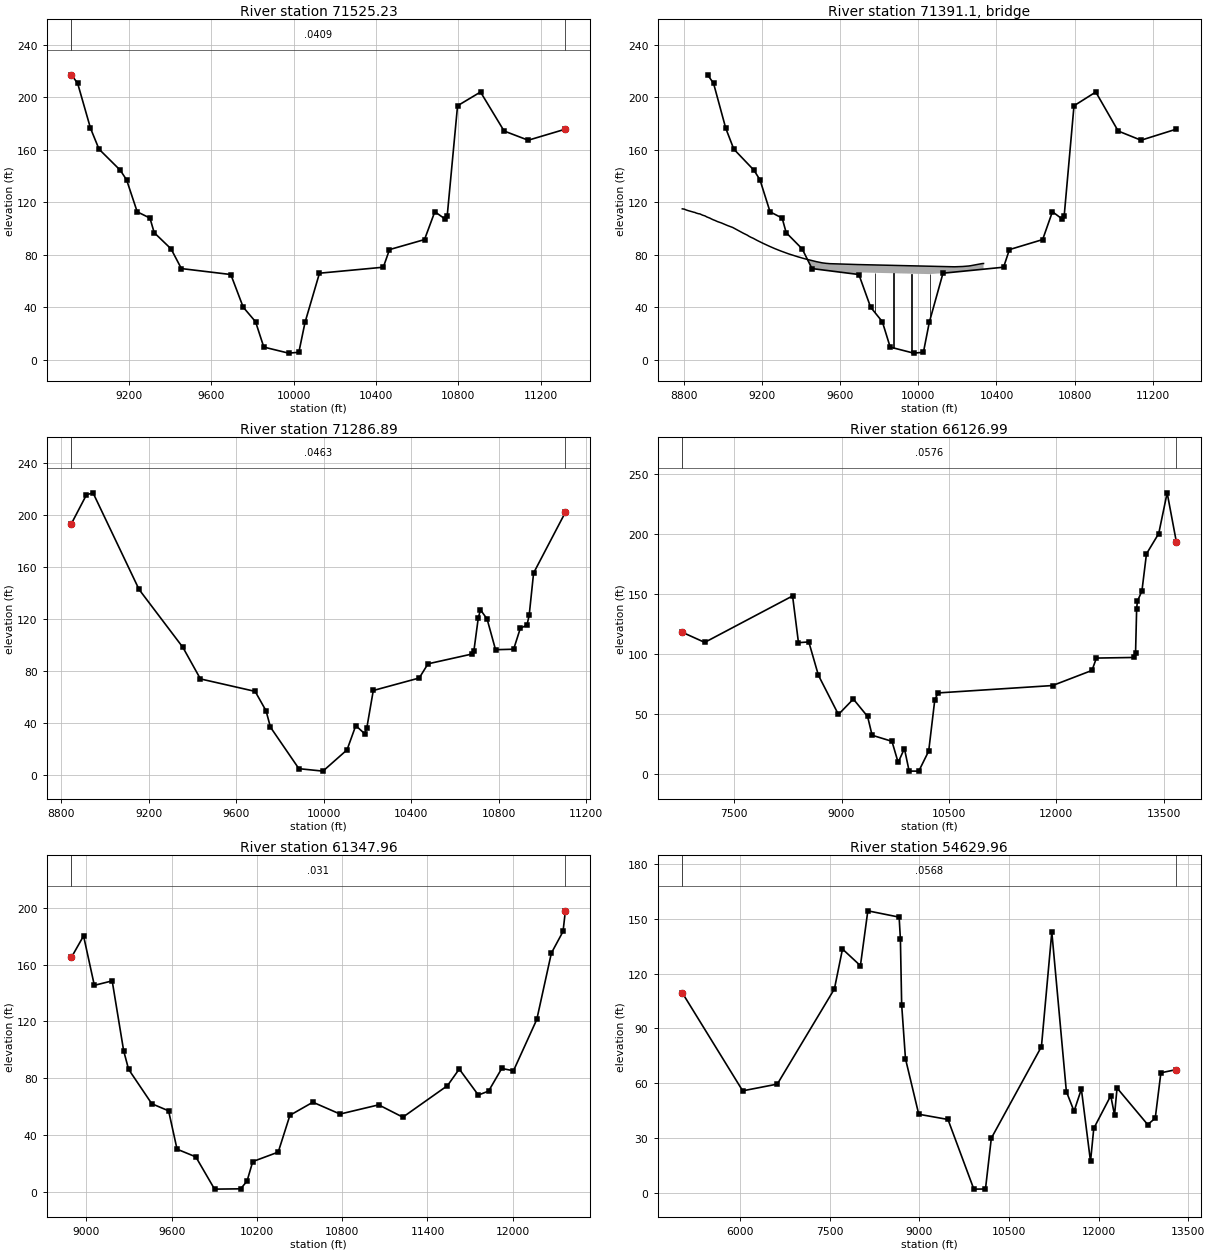
Type RM Length L Ch R = 1 ,71525.23,238.339000,238.339000,238.339000
XS GIS Cut Line= 6
 804989.40626017847653.603248445805107.888341516847204.512807369
805104.907974631846005.800122485805126.435917735845735.598425686
805222.379731297845471.547177568805363.845462248 845362.32671422
#Sta/Elev= 30
8921.152 217.0358951.494210.63499014.037176.3831 9055.29160.47099158.422144.4183
9189.362137.05629240.928112.71689302.808107.95899323.434 96.84519405.34584.48965
9455.38769.500779695.58864.970159755.63840.111339815.68829.031939855.693 9.72671
9975.791  5.118110025.915.73817110055.9828.5386310126.0965.9771310436.2170.53918
10466.2183.9500710636.2791.5848710686.32112.800310736.44107.219210746.48109.5733
10796.74 193.47710908.26203.947711022.83174.253111139.87167.237511320.49175.6709
#Mann= 3 , 0 , 0
8921.152  0.0409       08921.152  0.0409       011320.49  0.0409       0
#XS Ineff= 2 , 0
       0                               0
Bank Sta=8921.152,11320.49
Exp/Cntr=0.3,0.1

Type RM Length L Ch R = 3 , 71391.1,,,
BEGIN DESCRIPTION:
END DESCRIPTION:
Bridge Culvert--1,0,-1,-1, 0
Deck Dist Width WeirC Skew NumUp NumDn MinLoCord MaxHiCord MaxSubmerge Is_Ogee
72.669500,93.000000,2.6,0, 47, 48, , , 0.95, 0, 0,0,,
 8791.61 8803.53 8808.65 8819.47 8851.95 8855.73 8862.78 8873.61 8881.83 8895.26
 8907.93 8916.91 8934.03 8938.56 8949.39 8960.22 8971.04 8992.35 9022.94 9049.66
 9103.66 9123.85 9133.94 9144.03 9154.12 9174.30 9204.57 9234.84 9265.11 9295.38
 9335.74 9386.20 9416.47 9476.98 9506.98 9526.98 9546.99 9686.57 9686.5710151.57
10151.5710184.7610227.0410257.0610267.0610327.1110333.78
  114.99  114.71  114.30  113.73  112.35  112.27  111.79  111.30  111.13  110.18
  109.60  108.84  107.84  107.45  106.69  106.07  105.32  104.22  102.28  100.80
   96.45   94.99   94.03   93.25   92.61   90.98   88.76   86.67   84.70   82.91
   80.71   78.34   77.05   74.80   73.88   73.50   73.24   72.58   72.58   70.97
   70.97   70.86   71.09   71.46   71.66   73.33   73.37
 -885.01 -885.29 -885.70 -886.27 -887.65 -887.73 -888.21 -888.70 -888.87 -889.82
 -890.40 -891.16 -892.16 -892.55 -893.31 -893.93 -894.68 -895.78 -897.72 -899.20
 -903.55 -905.01 -905.97 -906.75 -907.39 -909.02 -911.24 -913.33 -915.30 -917.09
 -919.29 -921.66 -922.95 -925.20 -926.12 -926.50 -926.76 -927.42   66.58   64.97
 -929.03 -929.14 -928.91 -928.54 -928.34 -926.67 -926.63
 8791.61 8803.53 8808.65 8819.47 8851.95 8855.73 8862.78 8873.61 8881.83 8895.26
 8907.93 8916.91 8934.03 8938.56 8949.39 8960.22 8971.04 8992.35 9022.94 9049.66
 9103.66 9123.85 9133.94 9144.03 9154.12 9174.30 9204.57 9255.02 9285.29 9325.65
 9376.10 9406.38 9436.65 9476.98 9496.98 9516.98 9536.99 9566.99 9694.70 9694.70
10159.7010159.7010184.7610227.0410257.0610267.0610327.1110333.78
  114.99  114.71  114.30  113.73  112.35  112.27  111.79  111.30  111.13  110.18
  109.60  108.84  107.84  107.45  106.69  106.07  105.32  104.22  102.28  100.80
   96.45   94.99   94.03   93.25   92.61   90.98   88.76   85.33   83.49   81.22
   78.80   77.46   76.25   74.80   74.16   73.66   73.34   73.10   72.56   72.56
   70.94   70.94   70.86   71.09   71.46   71.66   73.33   73.37
 -885.01 -885.29 -885.70 -886.27 -887.65 -887.73 -888.21 -888.70 -888.87 -889.82
 -890.40 -891.16 -892.16 -892.55 -893.31 -893.93 -894.68 -895.78 -897.72 -899.20
 -903.55 -905.01 -905.97 -906.75 -907.39 -909.02 -911.24 -914.67 -916.51 -918.78
 -921.20 -922.54 -923.75 -925.20 -925.84 -926.34 -926.66 -926.90 -927.44   66.56
   64.94 -929.06 -929.14 -928.91 -928.54 -928.34 -926.67 -926.63
Pier Skew, UpSta & Num, DnSta & Num=  ,9778.37, 2 ,9786.50, 2 , 0 , 0 , 0 ,,
    4.00    4.00
 -927.74   72.26
    4.00    4.00
 -927.76   72.24
Pier Skew, UpSta & Num, DnSta & Num=  ,9872.17, 2 ,9880.30, 2 , 0 , 0 , 0 ,,
    4.00    4.00
 -928.06   71.94
    4.00    4.00
 -928.09   71.91
Pier Skew, UpSta & Num, DnSta & Num=  ,9965.97, 2 ,9974.10, 2 , 0 , 0 , 0 ,,
    4.00    4.00
 -928.39   71.61
    4.00    4.00
 -928.41   71.59
Pier Skew, UpSta & Num, DnSta & Num=  ,10059.77, 2 ,10067.90, 2 , 0 , 0 , 0 ,,
    4.00    4.00
 -928.71   71.29
    4.00    4.00
 -928.74   71.26
BR Coef=-1 , 0 , 0 ,, 0 ,,,0.8,0,1,0,
WSPro=,,,, 1 ,,,, 0 ,,,, 0 ,,,,-1 ,-1 ,-1 , 0 , 0 , 0 , 0 , 0
BC Design=,, 0 ,, 0 ,,,,,,

Type RM Length L Ch R = 1 ,71286.89,5159.905900,5159.905900,5159.905900
XS GIS Cut Line= 4
 805339.02709321847753.695924827805373.217919379847290.565643415
805338.800524414845855.360274136805395.593498051845501.429723158
#Sta/Elev= 30
8846.126193.36838915.008215.5576 8945.09217.12059155.662142.87279356.09598.37089
9436.118 74.1751 9686.1964.600869736.20449.65298 9756.2137.106719886.2475.234818
9996.279 3.3464510106.3119.6790410146.3238.2964510186.3332.1853210196.3436.13874
10226.3565.2816110436.4174.8748110476.4285.7686810676.4793.2526410686.4895.95818
10706.48121.194310716.49127.2058 10746.5120.239610785.2696.6132210868.0396.98811
10898.42 113.036 10928.8115.540310938.93122.893410959.19155.505811104.59 202.202
#Mann= 3 , 0 , 0
8846.126  0.0463       08846.126  0.0463       011104.59  0.0463       0
#XS Ineff= 2 , 0
       0                               0
Bank Sta=8846.126,11104.59
Exp/Cntr=0.3,0.1

Type RM Length L Ch R = 1 ,66126.99,4779.022800,4779.022800,4779.022800
XS GIS Cut Line= 6
809278.463433388850707.153428967809921.507897438848264.371018223
810417.736886351847071.460026874810734.830827778845170.694955225
810863.172483008 844703.65425919811096.802421017844077.269265396
#Sta/Elev= 30
6774.785118.04017088.202109.64638315.679148.26838398.088109.40818542.328110.0355
  8676.682.309468956.307 49.68559164.54262.529579363.65448.033869426.85832.42587
9704.17127.374779790.7299.7924779878.07821.360599944.3612.61123410079.092.588051
10217.5119.2631510303.0162.0578710349.6767.6197511948.4573.7655812498.8986.34533
12560.6396.6112513080.6897.1006713107.76101.1737 13122.9137.682413133.45143.8809
13196.77152.4705 13260.1183.262913431.25200.151213549.18234.020213677.06193.4264
#Mann= 3 , 0 , 0
6774.785  0.0576       06774.785  0.0576       013677.06  0.0576       0
#XS Ineff= 2 , 0
       0                               0
Bank Sta=6774.785,13677.06
Exp/Cntr=0.3,0.1

Type RM Length L Ch R = 1 ,61347.96,6717.999900,6717.999900,6717.999900
XS GIS Cut Line= 6
813655.694985604849228.536305305813949.986578238848705.786062625
814453.128875425847952.296389879814667.637144036847549.709614074
814886.431702744 846933.29080363815090.662626108846098.801903727
#Sta/Elev= 30
8893.922164.9851 8979.73180.12159055.641145.36849181.125 148.5149261.76299.43535
9296.42286.346599459.82762.112899578.193  57.1279637.64230.163089769.69224.75519
9901.5072.06692510085.252.27841710130.137.72796610170.2621.4351210349.65 28.0998
10431.91 53.986510593.5463.1887510784.6854.8571611056.6461.3307711226.7652.65782
11540.6574.8390111623.6186.50173 11757.868.2247811829.9770.9966311922.7586.93654
12005.0485.2744412169.21121.360112271.82168.038312353.91183.255612370.53197.7658
#Mann= 3 , 0 , 0
8893.922   0.031       08893.922   0.031       012370.53   0.031       0
#XS Ineff= 2 , 0
       0                10712.27       0
Bank Sta=8893.922,12370.53
Exp/Cntr=0.3,0.1

Type RM Length L Ch R = 1 ,54629.96,364.552600,364.552600,364.552600
XS GIS Cut Line= 6
814387.597848326851608.306814328815791.055501729851040.124996141
817544.163504869850554.499510512818505.701966375850219.417925447
821111.321247011849090.469108552822143.390895557 848774.63092999
#Sta/Elev= 30
 5029.87109.45036041.17955.836646620.82859.520967576.962111.60477712.068133.4036
8012.263 124.2928136.415154.30758660.561150.8593 8681.74138.8137 8702.92102.9329
8766.45973.436268988.84543.028179478.08340.174149911.1122.06692510105.982.129501
10204.0929.9305311042.9180.0097711216.73142.694511460.4855.4462211589.1944.69018
11711.76 56.775811864.7117.1918311919.3335.3007912203.3953.1344412267.0142.57587
12308.9457.3834812822.6637.3458412948.4640.8993613042.8265.6958813301.1967.45857
#Mann= 3 , 0 , 0
 5029.87  0.0568       0 5029.87  0.0568       013301.19  0.0568       0
#XS Ineff= 2 , 0
       09219.593        10465.96       0
Bank Sta=5029.87,13301.19
Exp/Cntr=0.3,0.1

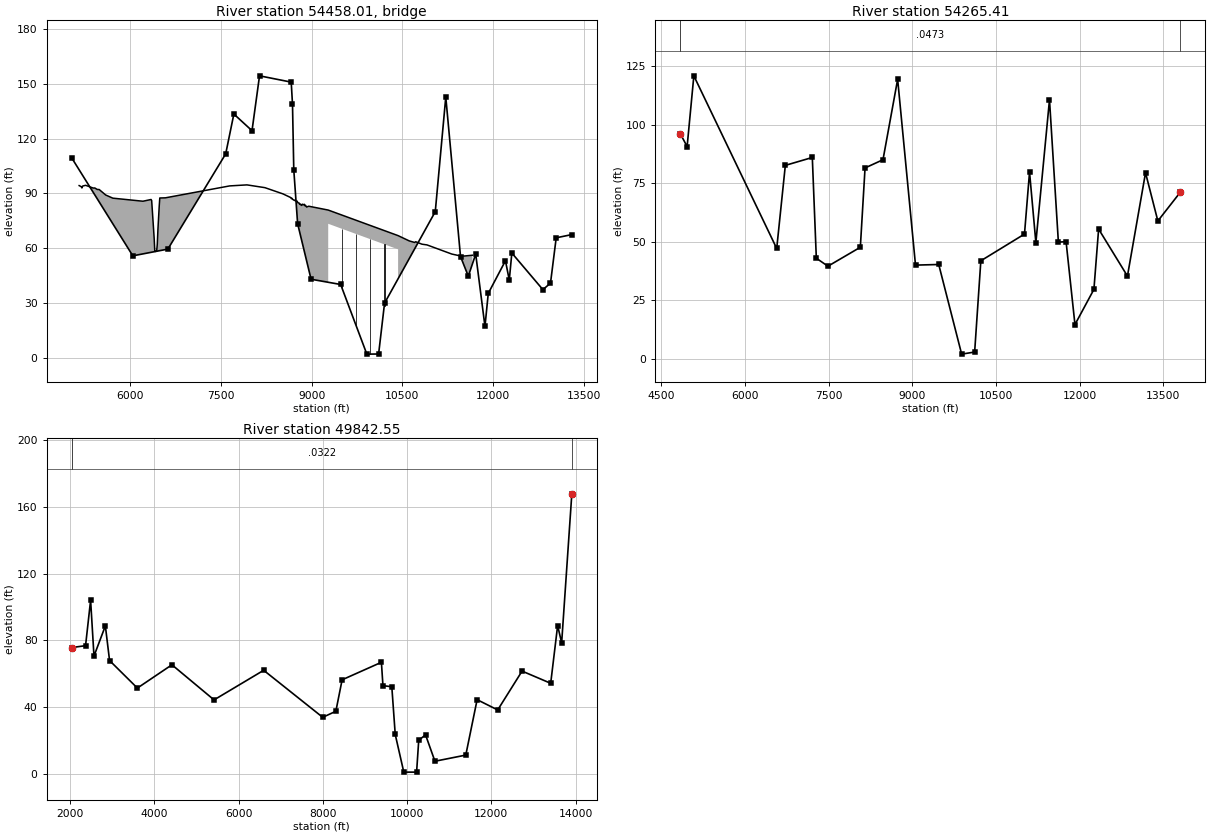
Type RM Length L Ch R = 3 ,54458.01,,,
BEGIN DESCRIPTION:
END DESCRIPTION:
Bridge Culvert--1,0,-1,-1, 0
Deck Dist Width WeirC Skew NumUp NumDn MinLoCord MaxHiCord MaxSubmerge Is_Ogee
115.776300,133.000000,2.6,0, 60, 60, , , 0.95, 0, 0,0,,
 5153.54 5185.54 5199.14 5212.48 5261.08 5385.91 5412.60 5452.62 5484.66 5592.76
 5710.28 6208.55 6342.61 6352.93 6394.18 6404.49 6414.80 6435.43 6445.74 6456.06
 6476.68 6486.99 6579.81 7643.39 7928.63 8225.46 8523.64 8651.74 8662.42 8673.09
 8685.87 8715.79 8726.47 8743.02 8758.49 8771.59 8790.52 8800.17 8811.87 8828.74
 8843.90 8857.32 8875.92 8885.89 8897.27 8914.46 8950.65 9272.39 9272.3910428.39
10428.3910612.2510700.7310719.0210822.3810906.3311316.4111458.6011524.2311656.28
   94.26   93.73   92.98   94.04   94.41   92.92   92.96   92.15   92.12   89.11
   87.39   85.71   86.66   86.09   65.48   58.31   58.25   58.46   62.22   70.16
   82.47   87.48   87.57   94.09   94.65   93.13   89.73   87.72   87.13   87.31
   86.71   86.10   86.31   85.63   85.76   84.83   84.76   84.01   84.12   83.42
   84.10   83.72   84.06   83.24   83.48   82.55   82.98   80.88   80.88   66.89
   66.89   64.01   63.16   63.55   62.21   61.81   56.81   55.78   55.75   56.16
 -905.74 -906.27 -907.02 -905.96 -905.59 -907.08 -907.04 -907.85 -907.88 -910.89
 -912.61 -914.29 -913.34 -913.91 -934.52 -941.69 -941.75 -941.54 -937.78 -929.84
 -917.53 -912.52 -912.43 -905.91 -905.35 -906.87 -910.27 -912.28 -912.87 -912.69
 -913.29 -913.90 -913.69 -914.37 -914.24 -915.17 -915.24 -915.99 -915.88 -916.58
 -915.90 -916.28 -915.94 -916.76 -916.52 -917.45 -917.02 -919.12   73.38   59.39
 -933.11 -935.99 -936.84 -936.45 -937.79 -938.19 -943.19 -944.22 -944.25 -943.84
 5153.54 5185.54 5199.14 5212.48 5261.08 5412.60 5452.62 5484.66 5592.76 5710.28
 6208.55 6342.61 6352.93 6394.18 6404.49 6414.80 6435.43 6445.74 6456.06 6476.68
 6486.99 6579.81 7675.06 7890.85 8023.74 8225.46 8523.64 8651.74 8662.42 8673.09
 8743.02 8758.49 8771.59 8790.52 8800.17 8811.87 8828.74 8843.90 8857.32 8875.92
 8885.89 8897.27 8914.46 8950.65 9057.40 9143.06 9343.75 9343.7510499.7510499.75
10634.3710645.4310700.7310719.0210822.3810906.3311316.4111458.6011524.2311656.28
   94.26   93.73   92.98   94.04   94.41   92.96   92.15   92.12   89.11   87.39
   85.71   86.66   86.09   65.48   58.31   58.25   58.46   62.22   70.16   82.47
   87.48   87.57   94.24   94.70   94.42   93.13   89.73   87.72   87.13   87.31
   85.63   85.76   84.83   84.76   84.01   84.12   83.42   84.10   83.72   84.06
   83.24   83.48   82.55   82.98   82.07   82.00   80.02   80.02   65.86   65.86
   63.76   63.97   63.16   63.55   62.21   61.81   56.81   55.78   55.75   56.16
 -905.74 -906.27 -907.02 -905.96 -905.59 -907.04 -907.85 -907.88 -910.89 -912.61
 -914.29 -913.34 -913.91 -934.52 -941.69 -941.75 -941.54 -937.78 -929.84 -917.53
 -912.52 -912.43 -905.76 -905.30 -905.58 -906.87 -910.27 -912.28 -912.87 -912.69
 -914.37 -914.24 -915.17 -915.24 -915.99 -915.88 -916.58 -915.90 -916.28 -915.94
 -916.76 -916.52 -917.45 -917.02 -917.93 -918.00 -919.98   72.52   58.36 -934.14
 -936.24 -936.03 -936.84 -936.45 -937.79 -938.19 -943.19 -944.22 -944.25 -943.84
Pier Skew, UpSta & Num, DnSta & Num=  ,9501.19, 2 ,9572.55, 2 , 0 , 0 , 0 ,,
    8.00    8.00
 -921.89   78.11
    8.00    8.00
 -922.75   77.25
Pier Skew, UpSta & Num, DnSta & Num=  ,9733.99, 2 ,9805.35, 2 , 0 , 0 , 0 ,,
    8.00    8.00
 -924.70   75.30
    8.00    8.00
 -925.57   74.43
Pier Skew, UpSta & Num, DnSta & Num=  ,9966.79, 2 ,10038.15, 2 , 0 , 0 , 0 ,,
    8.00    8.00
 -927.52   72.48
    8.00    8.00
 -928.38   71.62
Pier Skew, UpSta & Num, DnSta & Num=  ,10199.59, 2 ,10270.95, 2 , 0 , 0 , 0 ,,
    8.00    8.00
 -930.34   69.66
    8.00    8.00
 -931.20   68.80
BR Coef=-1 , 0 , 0 ,, 0 ,,,0.8,0,1,0,
WSPro=,,,, 1 ,,,, 0 ,,,, 0 ,,,,-1 ,-1 ,-1 , 0 , 0 , 0 , 0 , 0
BC Design=,, 0 ,, 0 ,,,,,,

Type RM Length L Ch R = 1 ,54265.41,4422.856100,4422.856100,4422.856100
XS GIS Cut Line= 6
814382.741593421852336.745042771815252.011212707851753.994460016
817680.138640821851074.118780121 820137.40359813849889.192595199
822109.445004553849354.094188467822673.128649384 849119.88760367
#Sta/Elev= 30
4841.89396.124624965.00490.617475085.396120.79096570.50747.133726724.82782.59115
7208.36385.963097280.37942.980357488.46339.574228069.09847.660418153.55481.49826
8475.02984.993748737.813119.29879057.72540.03869 9474.0140.305699884.6082.066925
10117.652.95324910228.6241.8835911010.8853.2821511101.2979.7361711214.8549.67253
11458.99110.576811618.2149.85258 11756.250.0424511915.4214.6812312255.0829.69264
12339.3955.4161412855.9835.3604813180.11  79.43713400.8858.8749613805.1571.18761
#Mann= 3 , 0 , 0
4841.893  0.0473       04841.893  0.0473       013805.15  0.0473       0
#XS Ineff= 2 , 0
       09254.193        10580.41       0
Bank Sta=4841.893,13805.15
Exp/Cntr=0.3,0.1

Type RM Length L Ch R = 1 ,49842.55,3238.233400,3238.233400,3238.233400
XS GIS Cut Line= 6
814065.522928089854780.787683696818202.777893931854809.094741672
820962.191263109853012.136214972  821224.1571244851456.730855703
 821502.24070093850711.539282322 823090.55298157849389.446234221
#Sta/Elev= 30
2039.74575.63681 2369.2376.772072489.232104.02712569.23470.523512839.24188.64866
2939.24367.854523599.25851.339364419.27865.312415419.30144.246816597.41962.00537
 7998.7833.798728310.306 37.43078459.03956.301619391.48466.808429428.13452.79234
9638.597 52.13499719.87523.502929923.0690.91863310226.860.91863310277.4720.04254
10439.4123.2776210662.087.45070511394.4311.13809 11663.544.3843912152.0438.21973
12730.38 61.525413409.7454.2093613574.4688.8319413669.9678.5035113911.39167.8647
#Mann= 3 , 0 , 0
2039.745  0.0322       02039.745  0.0322       013911.39  0.0322       0
#XS Ineff= 2 , 0
       09388.768        11369.34       0
Bank Sta=2039.745,13911.39
Exp/Cntr=0.3,0.1