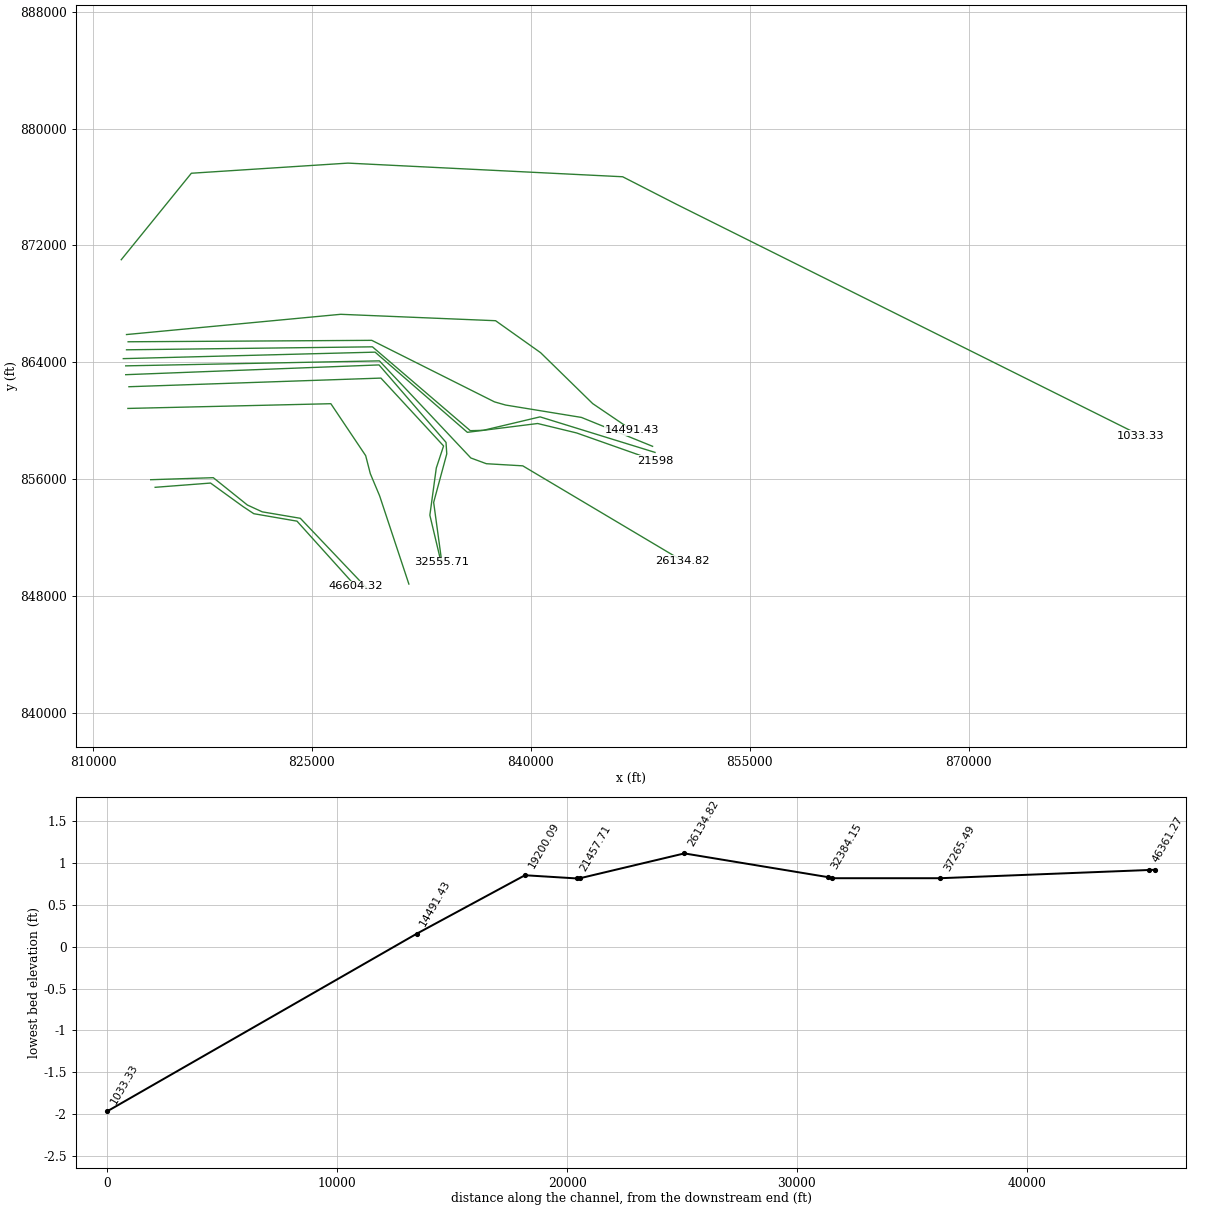
HEC-RAS study 17203_ras.prj: 17203

--- 17203_ras.g01 (geometry) --- (continued)

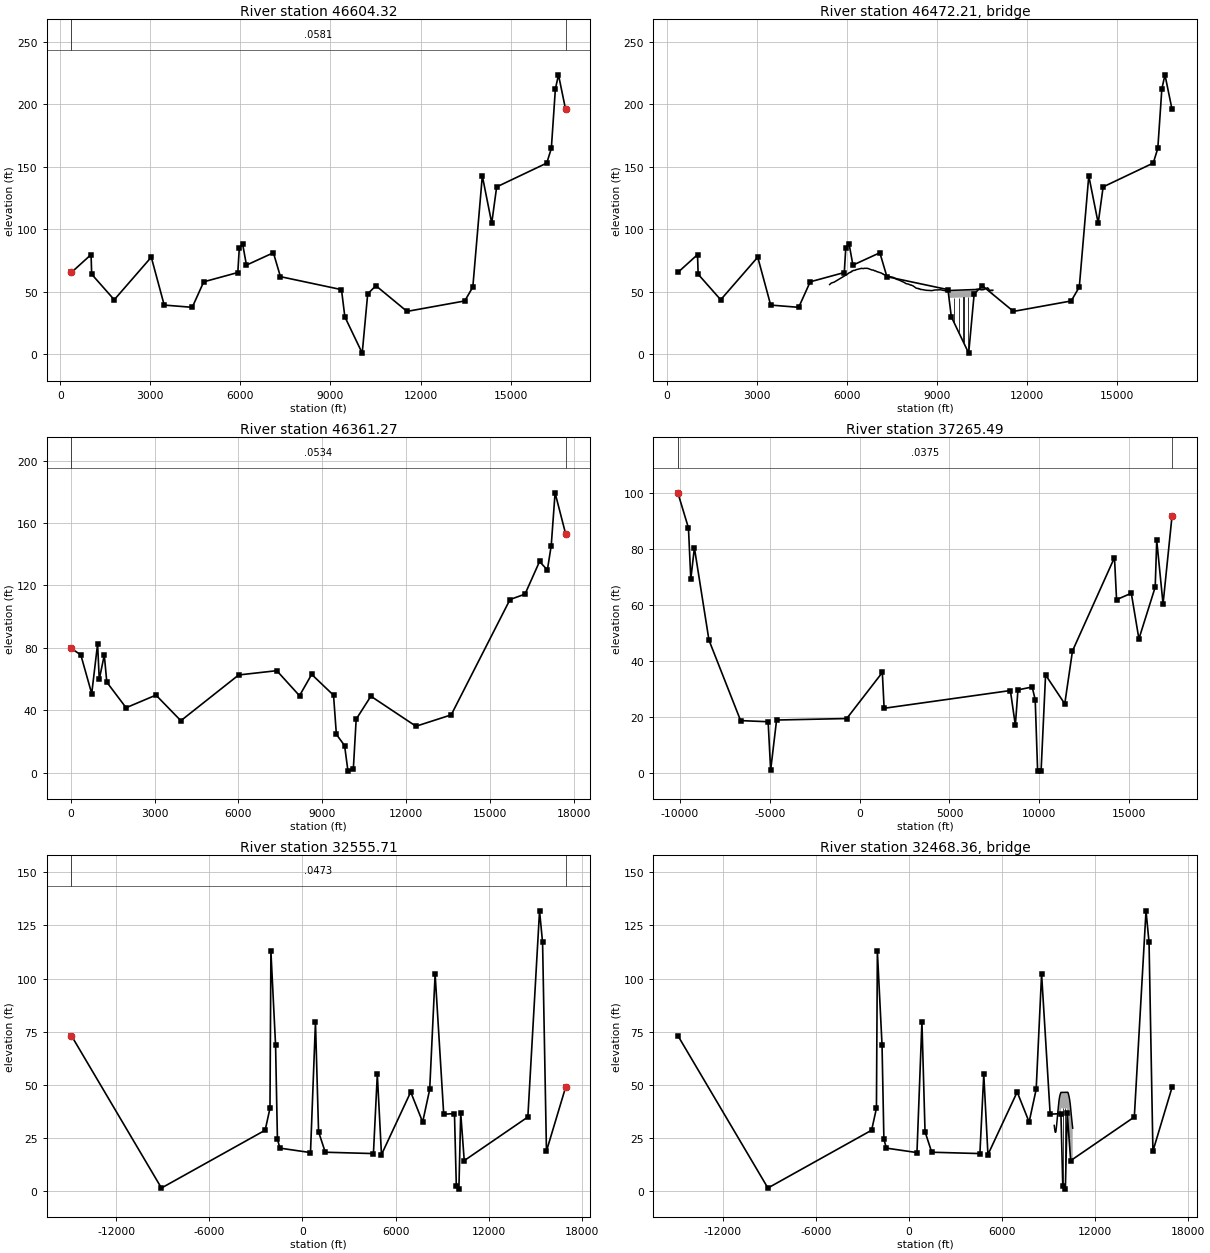
Type RM Length L Ch R = 1 ,46604.32,243.049200,243.049200,243.049200
XS GIS Cut Line= 6
814260.835428119855431.829350367818056.521365881 855723.25602603
820275.253154904854116.958677545821021.993393838853622.713339552
823979.718975127853113.119414464828012.838633209848639.294628158
#Sta/Elev= 30
367.113865.411671023.20479.691511043.26364.00577 1795.4743.58369 3029.0977.64601
3460.356 39.33574394.31337.543744777.02657.93344 5912.8265.366435961.51984.76519
6073.31288.133216200.25671.283897097.85681.16053 7332.5462.059439367.14151.69166
9478.97229.9507510057.570.92093610240.23 48.269310513.0954.8197211550.0834.28119
13473.6542.6344413742.9253.7534814059.12142.647614372.75104.839914537.27133.8176
16206.76 152.87416359.08164.6401 16493.5 212.10916597.21 223.42316833.77195.7766
#Mann= 3 , 0 , 0
367.1138  0.0581       0367.1138  0.0581       016833.77  0.0581       0
#XS Ineff= 2 , 0
       08929.573         10468.4       0
Bank Sta=367.1138,16833.77
Exp/Cntr=0.3,0.1

Type RM Length L Ch R = 3 ,46472.21,,,
BEGIN DESCRIPTION:
END DESCRIPTION:
Bridge Culvert--1,0,-1,-1, 0
Deck Dist Width WeirC Skew NumUp NumDn MinLoCord MaxHiCord MaxSubmerge Is_Ogee
71.524600,100.000000,2.6,0, 60, 60, , , 0.95, 0, 0,0,,
 5425.36 5481.62 5574.28 6011.58 6085.85 6114.48 6153.07 6165.93 6178.79 6217.38
 6268.82 6307.41 6487.48 6551.79 6578.77 6692.38 6829.99 6892.79 6917.91 6955.59
 6980.71 7156.55 7194.23 7206.79 7231.91 7257.03 7336.92 7545.92 7665.98 7730.51
 7905.59 7970.93 8058.07 8123.41 8134.36 8210.54 8301.33 8351.76 8371.93 8392.10
 8412.27 8452.62 8462.71 8644.26 8835.90 8916.58 9118.31 9279.69 9414.74 9414.74
10201.7410201.7410305.0110335.3710487.1910558.0410683.8210715.2810746.7410862.68
   55.78   56.97   57.68   63.98   65.35   65.43   66.25   66.11   66.55   67.01
   67.14   67.63   68.71   68.50   68.73   68.70   67.42   67.24   66.72   66.69
   66.24   64.85   64.16   64.27   63.63   63.61   62.59   61.48   59.87   59.41
   57.48   56.50   56.04   55.27   55.41   54.60   52.97   52.60   52.74   52.29
   52.40   51.78   51.92   51.16   50.91   51.36   51.57   50.81   51.03   51.03
   51.74   51.74   51.84   52.15   51.53   51.71   53.14   52.56   51.17   51.25
 -944.22 -943.03 -942.32 -936.02 -934.65 -934.57 -933.75 -933.89 -933.45 -932.99
 -932.86 -932.37 -931.29 -931.50 -931.27 -931.30 -932.58 -932.76 -933.28 -933.31
 -933.76 -935.15 -935.84 -935.73 -936.37 -936.39 -937.41 -938.52 -940.13 -940.59
 -942.52 -943.50 -943.96 -944.73 -944.59 -945.40 -947.03 -947.40 -947.26 -947.71
 -947.60 -948.22 -948.08 -948.84 -949.09 -948.64 -948.43 -949.19 -948.97   45.03
   45.74 -948.26 -948.16 -947.85 -948.47 -948.29 -946.86 -947.44 -948.83 -948.75
 5425.36 5481.62 5574.28 6011.58 6085.85 6114.48 6153.07 6165.93 6178.79 6217.38
 6268.82 6307.41 6487.48 6551.79 6578.77 6692.38 6829.99 6892.79 6917.91 6955.59
 6980.71 7156.55 7194.23 7206.79 7231.91 7257.03 7336.92 7545.92 7665.98 7730.51
 7905.59 7970.93 8058.07 8123.41 8134.36 8210.54 8301.33 8351.76 8371.93 8392.10
 8412.27 8452.62 8462.71 8644.26 8835.90 8916.58 9118.31 9279.69 9445.91 9445.91
10232.9110232.9110305.0110335.3710487.1910558.0410683.8210715.2810746.7410862.68
   55.78   56.97   57.68   63.98   65.35   65.43   66.25   66.11   66.55   67.01
   67.14   67.63   68.71   68.50   68.73   68.70   67.42   67.24   66.72   66.69
   66.24   64.85   64.16   64.27   63.63   63.61   62.59   61.48   59.87   59.41
   57.48   56.50   56.04   55.27   55.41   54.60   52.97   52.60   52.74   52.29
   52.40   51.78   51.92   51.16   50.91   51.36   51.57   50.81   51.06   51.06
   51.77   51.77   51.84   52.15   51.53   51.71   53.14   52.56   51.17   51.25
 -944.22 -943.03 -942.32 -936.02 -934.65 -934.57 -933.75 -933.89 -933.45 -932.99
 -932.86 -932.37 -931.29 -931.50 -931.27 -931.30 -932.58 -932.76 -933.28 -933.31
 -933.76 -935.15 -935.84 -935.73 -936.37 -936.39 -937.41 -938.52 -940.13 -940.59
 -942.52 -943.50 -943.96 -944.73 -944.59 -945.40 -947.03 -947.40 -947.26 -947.71
 -947.60 -948.22 -948.08 -948.84 -949.09 -948.64 -948.43 -949.19 -948.94   45.06
   45.77 -948.23 -948.16 -947.85 -948.47 -948.29 -946.86 -947.44 -948.83 -948.75
Pier Skew, UpSta & Num, DnSta & Num=  ,9570.04, 2 ,9601.21, 2 , 0 , 0 , 0 ,,
    7.00    7.00
 -948.82   51.18
    7.00    7.00
 -948.79   51.21
Pier Skew, UpSta & Num, DnSta & Num=  ,9728.84, 2 ,9760.01, 2 , 0 , 0 , 0 ,,
    7.00    7.00
 -948.67   51.33
    7.00    7.00
 -948.64   51.36
Pier Skew, UpSta & Num, DnSta & Num=  ,9887.64, 2 ,9918.81, 2 , 0 , 0 , 0 ,,
    7.00    7.00
 -948.52   51.48
    7.00    7.00
 -948.49   51.51
Pier Skew, UpSta & Num, DnSta & Num=  ,10046.44, 2 ,10077.61, 2 , 0 , 0 , 0 ,,
    7.00    7.00
 -948.37   51.63
    7.00    7.00
 -948.34   51.66
BR Coef=-1 , 0 , 0 ,, 0 ,,,0.8,0,1,0,
WSPro=,,,, 1 ,,,, 0 ,,,, 0 ,,,,-1 ,-1 ,-1 , 0 , 0 , 0 , 0 , 0
BC Design=,, 0 ,, 0 ,,,,,,

Type RM Length L Ch R = 1 ,46361.27,9095.778600,9095.778600,9095.778600
XS GIS Cut Line= 6
813957.015983641855952.662683696 818245.00000003856091.303722262
 820580.14110586854218.501099855821599.047898382853751.002689198
824208.219731629 853308.62200813828787.411282837848492.392918736
#Sta/Elev= 30
18.1961679.59021356.356875.47133746.5606 50.6164956.670382.505031016.70259.78722
1196.79675.381491286.84357.990161977.20341.586483047.76249.690453938.22833.25464
 6008.0962.601367373.237 65.35688187.41249.28768 8622.3762.988899405.93349.60392
9507.26724.517319801.13517.299369922.7350.91863310115.272.399127 10216.634.22849
10742.8148.97757 12357.929.7170713619.2236.9998215724.74110.997216262.88114.4701
16783.01135.4038 17063.2 129.93617201.18145.643817339.17179.449217715.32153.2443
#Mann= 3 , 0 , 0
18.19616  0.0534       018.19616  0.0534       017715.32  0.0534       0
#XS Ineff= 2 , 0
       08981.473        10476.65       0
Bank Sta=18.19616,17715.32
Exp/Cntr=0.3,0.1

Type RM Length L Ch R = 1 ,37265.49,4709.780000,4709.780000,4709.780000
XS GIS Cut Line= 6
812394.515983671 860835.47518371826299.224842966861159.924392387
828685.281823128857599.466129124829002.722866565856366.761423141
829641.733011574854843.846749097 831643.98783949848804.219628677
#Sta/Elev= 30
-10107.3100.0036-9516.6587.48793-9386.6169.24002-9186.5680.41191-8376.3447.50144
-6615.8618.82005-5085.44 18.4268 -4945.41.151265-4615.3119.03487-714.25119.56009
1266.28835.985021366.315 23.22058388.16429.542578665.38417.181888809.97629.78094
 9601.9230.80235 9769.7126.250629902.7131.02517310096.340.82020810346.1935.10382
11413.6924.8000411842.9243.6433814179.3176.9445614294.6261.9331715115.0364.21685
 15538.247.9453616443.8266.3998416529.5983.0578816880.3760.3946617381.4991.82272
#Mann= 3 , 0 , 0
-10107.3  0.0375       0-10107.3  0.0375       017381.49  0.0375       0
#XS Ineff= 2 , 0
       07928.588        11880.69       0
Bank Sta=-10107.3,17381.49
Exp/Cntr=0.3,0.1

Type RM Length L Ch R = 1 ,32555.71,171.561800,171.561800,171.561800
XS GIS Cut Line= 6
812464.654872537862322.905739248829729.717265606 862914.53353624
 834022.64848718858265.401184782833523.280035049856755.284408107
 833082.13736546853520.858472228 833851.37111941850290.824694738
#Sta/Elev= 30
-14888.273.12018 -9084.41.343193-2400.4828.56977 -2090.338.91593-2030.26112.7949
-1730.0968.70001-1610.0224.31573-1449.9220.12937521.233218.03296841.421179.58189
1041.538 27.84051471.79118.197614576.43117.56463 4827.0254.894455095.03117.05879
6979.13746.566787749.20732.420588202.60147.787268552.266102.08579105.46436.12158
9798.75836.370959918.6042.19444110083.840.82020810201.8736.5795710428.1614.24818
14527.6934.7873815281.38131.887515476.55     11715726.8918.7219316959.5548.75288
#Mann= 3 , 0 , 0
-14888.2  0.0473       0-14888.2  0.0473       016959.55  0.0473       0
#XS Ineff= 2 , 0
       08098.529         12708.3       0
Bank Sta=-14888.2,16959.55
Exp/Cntr=0.3,0.1

Type RM Length L Ch R = 3 ,32468.36,,,
BEGIN DESCRIPTION:
END DESCRIPTION:
Bridge Culvert--1,0,-1,-1, 0
Deck Dist Width WeirC Skew NumUp NumDn MinLoCord MaxHiCord MaxSubmerge Is_Ogee
62.780900,46.000000,2.6,0, 40, 42, , , 0.95, 0, 0,0,,
 9368.48 9378.17 9382.66 9393.94 9399.78 9416.50 9427.78 9439.06 9450.34 9461.63
 9472.91 9486.19 9518.03 9551.88 9563.16 9574.44 9611.30 9667.98 9686.87 9705.77
 9727.42 9762.78 9798.14 9803.13 9803.1310178.1310178.1310230.7410253.6810272.57
10316.7310351.4310372.4410393.4610403.9710414.7910467.0210519.5610530.0710558.28
   30.83   30.17   29.95   29.16   28.98   28.10   27.73   27.77   27.59   27.69
   27.96   28.64   30.64   33.27   34.18   35.19   38.04   42.06   43.08   43.96
   44.76   45.69   46.38   46.37   46.37   46.42   46.42   46.43   46.31   45.86
   44.58   43.32   42.31   41.13   40.46   39.71   35.69   31.93   31.19   29.54
 -969.17 -969.83 -970.05 -970.84 -971.02 -971.90 -972.27 -972.23 -972.41 -972.31
 -972.04 -971.36 -969.36 -966.73 -965.82 -964.81 -961.96 -957.94 -956.92 -956.04
 -955.24 -954.31 -953.62 -953.63   38.87   38.92 -953.58 -953.57 -953.69 -954.14
 -955.42 -956.68 -957.69 -958.87 -959.54 -960.29 -964.31 -968.07 -968.81 -970.46
 9368.48 9378.17 9382.66 9393.94 9399.78 9416.50 9427.78 9439.06 9450.34 9461.63
 9472.91 9486.19 9518.03 9551.88 9563.16 9574.44 9611.30 9667.98 9692.06 9705.77
 9724.66 9762.78 9800.23 9806.04 9829.54 9829.5410204.5410204.5410230.7410253.68
10257.8010291.4710316.7310349.7110361.9410393.4610403.9710414.7910467.0210519.56
10530.0710558.28
   30.83   30.17   29.95   29.16   28.98   28.10   27.73   27.77   27.59   27.69
   27.96   28.64   30.64   33.27   34.18   35.19   38.04   42.06   43.34   43.96
   44.68   45.69   46.41   46.34   46.34   46.34   46.42   46.42   46.43   46.31
   46.22   45.34   44.58   43.39   42.83   41.13   40.46   39.71   35.69   31.93
   31.19   29.54
 -969.17 -969.83 -970.05 -970.84 -971.02 -971.90 -972.27 -972.23 -972.41 -972.31
 -972.04 -971.36 -969.36 -966.73 -965.82 -964.81 -961.96 -957.94 -956.66 -956.04
 -955.32 -954.31 -953.59 -953.66 -953.66   38.84   38.92 -953.58 -953.57 -953.69
 -953.78 -954.66 -955.42 -956.61 -957.17 -958.87 -959.54 -960.29 -964.31 -968.07
 -968.81 -970.46
Pier Skew, UpSta & Num, DnSta & Num=  ,9927.46, 2 ,9953.88, 2 , 0 , 0 , 0 ,,
    4.00    4.00
 -953.64   46.36
    4.00    4.00
 -953.63   46.37
Pier Skew, UpSta & Num, DnSta & Num=  ,10053.79, 2 ,10080.21, 2 , 0 , 0 , 0 ,,
    4.00    4.00
 -953.61   46.39
    4.00    4.00
 -953.60   46.40
BR Coef=-1 , 0 , 0 ,, 0 ,,,0.8,0,1,0,
WSPro=,,,, 1 ,,,, 0 ,,,, 0 ,,,,-1 ,-1 ,-1 , 0 , 0 , 0 , 0 , 0
BC Design=,, 0 ,, 0 ,,,,,,

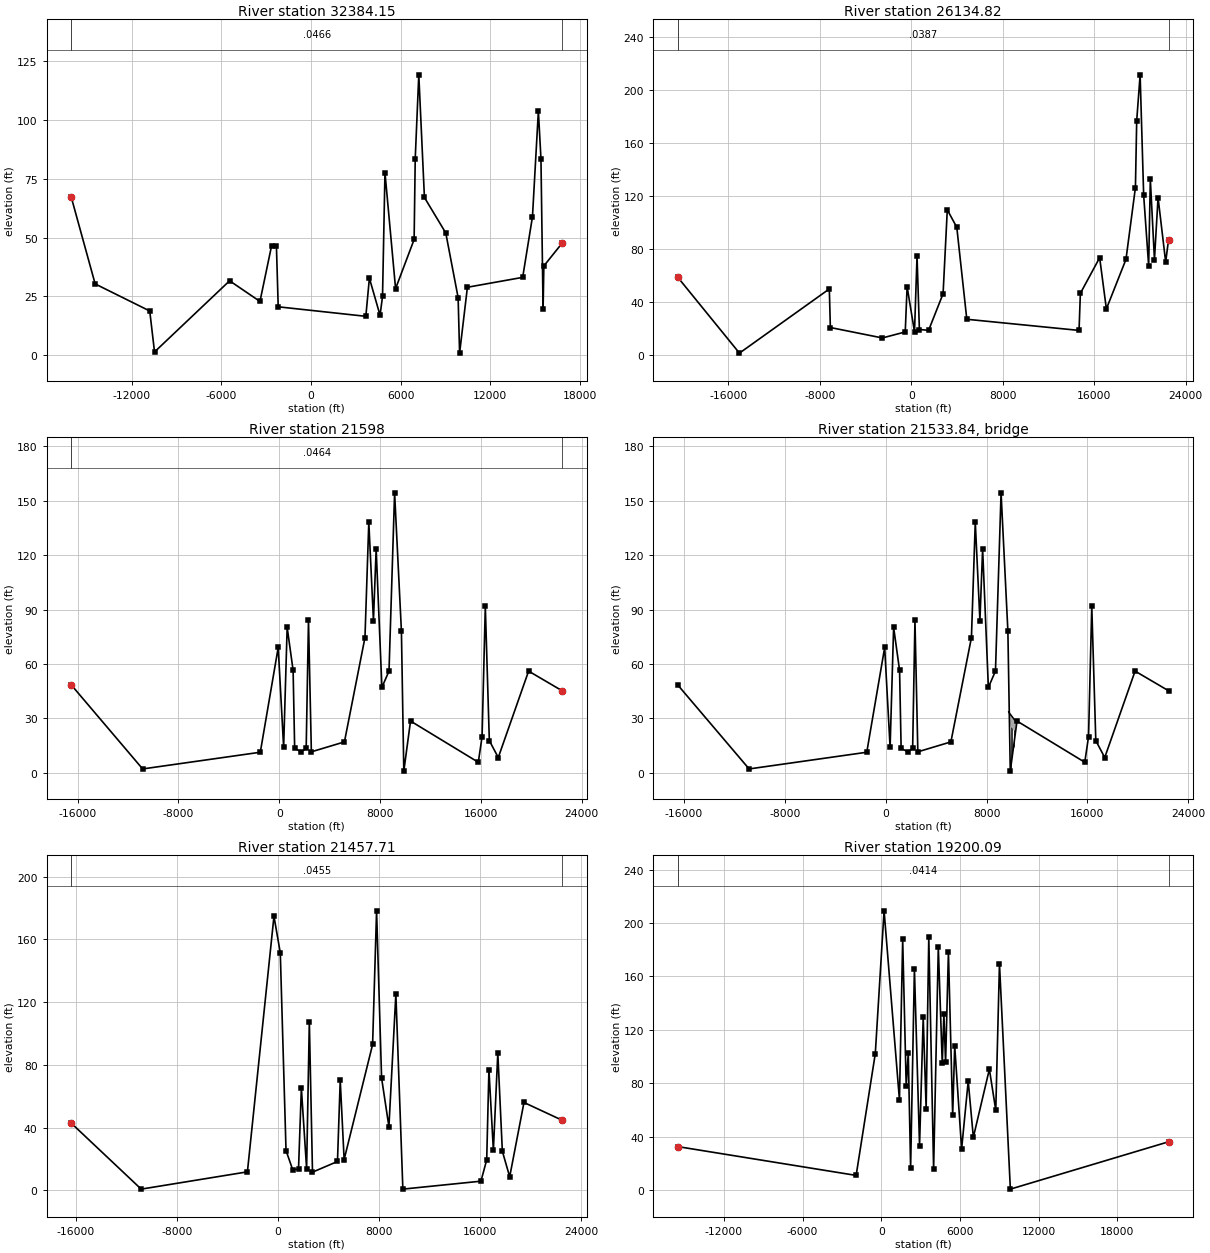
Type RM Length L Ch R = 1 ,32384.15,6249.328400,6249.328400,6249.328400
XS GIS Cut Line= 6
812244.654872537863147.905739263829600.056913614 863816.97759071
  834188.7992028858511.966898277834240.857423156857723.322328493
833342.210848242854397.660896271 833898.60994193850322.638595611
#Sta/Elev= 30
-16038.567.23444  -1443730.26604-10784.218.75569  -104641.329775-5440.2731.59385
-3408.7722.81594-2628.1946.59359-2307.9546.34861-2187.8620.528683674.69816.48809
3912.91732.727864625.90616.917444791.35224.918664955.12877.611775665.22628.25062
6905.55149.154936979.99583.548687218.214119.18337595.39167.023819023.97651.92671
9849.90624.452759948.4480.83308310470.8628.8476714168.9333.0513614823.9658.81414
15219.24103.732915392.03 83.5253 15534.819.4172115585.8937.9037916804.5747.57069
#Mann= 3 , 0 , 0
-16038.5  0.0466       0-16038.5  0.0466       016804.57  0.0466       0
#XS Ineff= 2 , 0
       07571.956        12618.42       0
Bank Sta=-16038.5,16804.57
Exp/Cntr=0.3,0.1

Type RM Length L Ch R = 1 ,26134.82,4536.818700,4536.818700,4536.818700
XS GIS Cut Line= 6
812244.654872537863752.905739248829625.334497184864094.377092466
835889.729343951857441.678776428836953.035441428857048.832964927
839446.953453392856902.981982723850394.723505646850392.856230274
#Sta/Elev= 30
-20428.158.44754-15026.81.117024-7165.24 49.5573-7075.2220.43751-2527.4412.57202
-525.66917.10289-362.01551.27236284.514217.19625505.473274.24123711.701618.94196
1517.40618.324432783.97245.959823151.685109.25913982.44496.080674858.08326.66956
14674.6318.2610214790.1946.2285516477.7873.1307517065.0234.4729618779.3671.88197
19605.84126.087819716.55176.451920016.46211.1398 20326.6120.237120763.1467.07693
20909.32132.304321269.9871.7435321584.56118.553222250.2469.8255122500.9686.65163
#Mann= 3 , 0 , 0
-20428.1  0.0387       0-20428.1  0.0387       022500.96  0.0387       0
#XS Ineff= 2 , 0
       03255.965        11716.05       0
Bank Sta=-20428.1,22500.96
Exp/Cntr=0.3,0.1

Type RM Length L Ch R = 1 ,   21598,140.297800,140.297800,140.297800
XS GIS Cut Line= 6
812079.654872537864247.905739263829330.750639439864692.115748733
835651.743708402859199.308427393 840466.45633018859803.225717843
843133.122996837859157.392384499848508.122996807857261.559051156
#Sta/Elev= 30
-16505.548.43402-10838.32.028534-1505.2311.24464-84.756669.05709 345.38614.00549
625.478880.195061097.52356.436631220.58413.386171750.50911.491342134.22413.31273
2317.17284.143772545.85611.473225168.52116.953696798.03874.555337102.744138.3133
7470.18883.945417685.661123.43358140.99547.016618705.08256.051819148.664154.4257
9688.83778.201419878.8620.820208   1041228.4691215788.935.71360416087.3119.84376
16344.5491.74715 16663.517.6706517371.818.32018319778.8756.0274222433.1445.18903
#Mann= 3 , 0 , 0
-16505.5  0.0464       0-16505.5  0.0464       022433.14  0.0464       0
#XS Ineff= 2 , 0
       0 7296.87        15154.04       0
Bank Sta=-16505.5,22433.14
Exp/Cntr=0.3,0.1

Type RM Length L Ch R = 3 ,21533.84,,,
BEGIN DESCRIPTION:
END DESCRIPTION:
Bridge Culvert--1,0,-1,-1, 0
Deck Dist Width WeirC Skew NumUp NumDn MinLoCord MaxHiCord MaxSubmerge Is_Ogee
49.148900,42.000000,2.6,0, 27, 27, , , 0.95, 0, 0,0,,
 9754.79 9756.31 9766.32 9772.55 9805.00 9805.0010250.0010250.0010262.6210266.38
10276.3810278.6410286.6410296.9810307.3110311.2410317.6410327.9710338.3110348.64
10350.9410358.9710369.3110379.6410389.9710390.6410391.22
   33.52   33.48   33.19   33.22   32.92   32.92   28.84   28.84   28.72   28.67
   28.61   28.60   28.53   28.53   28.30   28.34   28.38   28.18   28.27   28.28
   28.31   28.33   28.24   28.23   28.41   28.41   28.40
 -966.48 -966.52 -966.81 -966.78 -967.08   26.42   22.34 -971.16 -971.28 -971.33
 -971.39 -971.40 -971.47 -971.47 -971.70 -971.66 -971.62 -971.82 -971.73 -971.72
 -971.69 -971.67 -971.76 -971.77 -971.59 -971.59 -971.60
 9754.79 9756.31 9766.32 9772.55 9793.64 9793.6410238.6410238.6410262.6210266.38
10276.3810278.6410286.6410296.9810307.3110311.2410317.6410327.9710338.3110348.64
10350.9410358.9710369.3110379.6410389.9710390.6410391.22
   33.52   33.48   33.19   33.22   33.02   33.02   28.94   28.94   28.72   28.67
   28.61   28.60   28.53   28.53   28.30   28.34   28.38   28.18   28.27   28.28
   28.31   28.33   28.24   28.23   28.41   28.41   28.40
 -966.48 -966.52 -966.81 -966.78 -966.98   26.52   22.44 -971.06 -971.28 -971.33
 -971.39 -971.40 -971.47 -971.47 -971.70 -971.66 -971.62 -971.82 -971.73 -971.72
 -971.69 -971.67 -971.76 -971.77 -971.59 -971.59 -971.60
Pier Skew, UpSta & Num, DnSta & Num=  ,9915.25, 2 ,9903.89, 2 , 0 , 0 , 0 ,,
    4.00    4.00
 -968.09   31.91
    4.00    4.00
 -967.99   32.01
Pier Skew, UpSta & Num, DnSta & Num=  ,10027.50, 2 ,10016.14, 2 , 0 , 0 , 0 ,,
    4.00    4.00
 -969.12   30.88
    4.00    4.00
 -969.02   30.98
Pier Skew, UpSta & Num, DnSta & Num=  ,10139.75, 2 ,10128.39, 2 , 0 , 0 , 0 ,,
    4.00    4.00
 -970.15   29.85
    4.00    4.00
 -970.05   29.95
BR Coef=-1 , 0 , 0 ,, 0 ,,,0.8,0,1,0,
WSPro=,,,, 1 ,,,, 0 ,,,, 0 ,,,,-1 ,-1 ,-1 , 0 , 0 , 0 , 0 , 0
BC Design=,, 0 ,, 0 ,,,,,,

Type RM Length L Ch R = 1 ,21457.71,2257.616600,2257.616600,2257.616600
XS GIS Cut Line= 6
812299.654872537864852.905739248829146.962812841 865056.78215237
835852.661339939859312.325430542836743.916949183859336.564653665
840632.213118136860257.999559864848508.122996807857824.059051171
#Sta/Elev= 30
-16352.942.90158-10817.20.817404-2416.5611.83438-316.406174.7765183.6304 151.484
 637.87525.412161159.30713.316831625.44413.511571851.00165.112292266.01713.79731
2481.338107.59462731.52211.62996 4706.6618.444014925.19670.187755233.36419.67165
7485.02293.024367799.568178.24318196.07271.656728775.44640.654319325.405125.1827
9878.5520.82020816054.955.88429516509.8319.4615716685.5877.0465817037.0825.59666
17388.5887.5588717747.1324.9794118327.898.68453819457.7556.0592922470.4844.76162
#Mann= 3 , 0 , 0
-16352.9  0.0455       0-16352.9  0.0455       022470.48  0.0455       0
#XS Ineff= 2 , 0
       07348.033        15282.25       0
Bank Sta=-16352.9,22470.48
Exp/Cntr=0.3,0.1

Type RM Length L Ch R = 1 ,19200.09,4708.656100,4708.656100,4708.656100
XS GIS Cut Line= 6
812409.654872537865402.905739263829102.072387457865500.826441526
837510.537358195861284.974715248838272.846035093861068.049887776
 843466.45633015860219.892384499 848341.45633015858240.725717828
#Sta/Elev= 30
-15517.332.69318-1911.6911.11602-451.668102.2596218.3435209.11991390.11467.58165
1636.881187.68741905.08277.862272061.533  102.612241.43316.837112530.885165.6117
2922.012 33.34943201.388129.44613424.88961.15927 3626.04189.70753994.81715.93775
4352.419181.74834654.14594.879994777.071 131.8834907.40695.686025123.497178.4349
5447.57456.263485601.903 108.1076129.25230.888096632.12981.736557023.25639.63547
8245.47490.592188733.03959.897989015.013 169.4319845.3770.85563521903.6736.27252
#Mann= 3 , 0 , 0
-15517.3  0.0414       0-15517.3  0.0414       021903.67  0.0414       0
#XS Ineff= 2 , 0
       07903.187        14876.79       0
Bank Sta=-15517.3,21903.67
Exp/Cntr=0.3,0.1

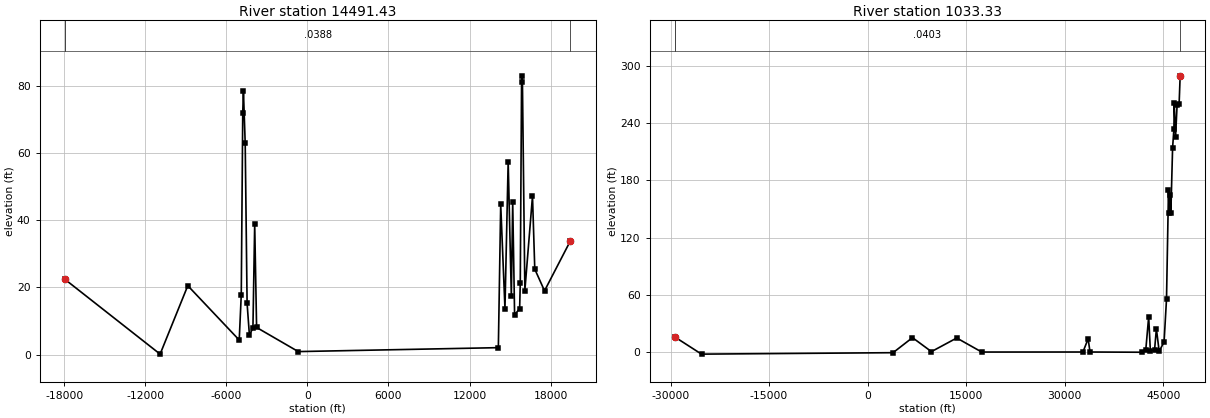
Type RM Length L Ch R = 1 ,14491.43,13458.104000,13458.104000,13458.104000
XS GIS Cut Line= 6
812299.654872537865897.905739248826972.215589255867285.276270375
837585.077384621866845.846124515840671.138048351864653.983844832
844238.397489935861166.601210445846938.452949435859336.410012752
#Sta/Elev= 30
-17938.5 22.3734-10901.9 0.15584 -8852.820.51902-5045.89 4.34087-4895.2217.83208
-4784.73 72.0343-4734.5178.43373-4603.93 62.9198-4463.3115.24301-4292.555.845858
-4031.397.921632-3900.8138.87318-3760.188.092519-675.537  0.911814134.912.081788
14309.4444.7121914624.3813.7162214862.1257.4050715096.2217.4508215197.7545.38358
 15337.611.8349715711.3413.7151715757.1421.2347215854.3981.2019915911.6182.95321
16097.5719.0744316662.4647.1569416831.5925.4453317552.7918.99302 19457.333.77381
#Mann= 3 , 0 , 0
-17938.5  0.0388       0-17938.5  0.0388       0 19457.3  0.0388       0
#XS Ineff= 2 , 0
       06784.822        13202.97       0
Bank Sta=-17938.5,19457.3
Exp/Cntr=0.3,0.1

Type RM Length L Ch R = 1 , 1033.33,0.000000,0.000000,0.000000
XS GIS Cut Line= 6
811938.765699834871025.149610952816742.361986548876949.585031226
827470.393693596877643.437828198846291.072447628876708.568110421
849993.922948986874814.653348267881804.405025452858962.785602108
#Sta/Elev= 30
-29329.815.89677-25287.6 -1.96853880.629-0.460096834.26615.285499722.1780.656167
13574.5714.9165317381.380.21784732788.730.25098433582.0114.0830133865.520.250984
41760.530.01082742352.692.023516 42799.637.0983843056.581.25231143693.432.362791
43972.7524.4879944397.32 0.9915345143.2410.8004545514.6155.5972645815.87169.8326
45916.83145.647946039.73164.7602 46173.8145.415546441.95 214.12146643.06234.0056
46690.29 260.44446892.08225.4435 47123.5258.525247436.34260.315547592.09289.3352
#Mann= 3 , 0 , 0
-29329.8  0.0403       0-29329.8  0.0403       047592.09  0.0403       0
#XS Ineff= 2 , 0
       07065.657        12527.17       0
Bank Sta=-29329.8,47592.09
Exp/Cntr=0.3,0.1